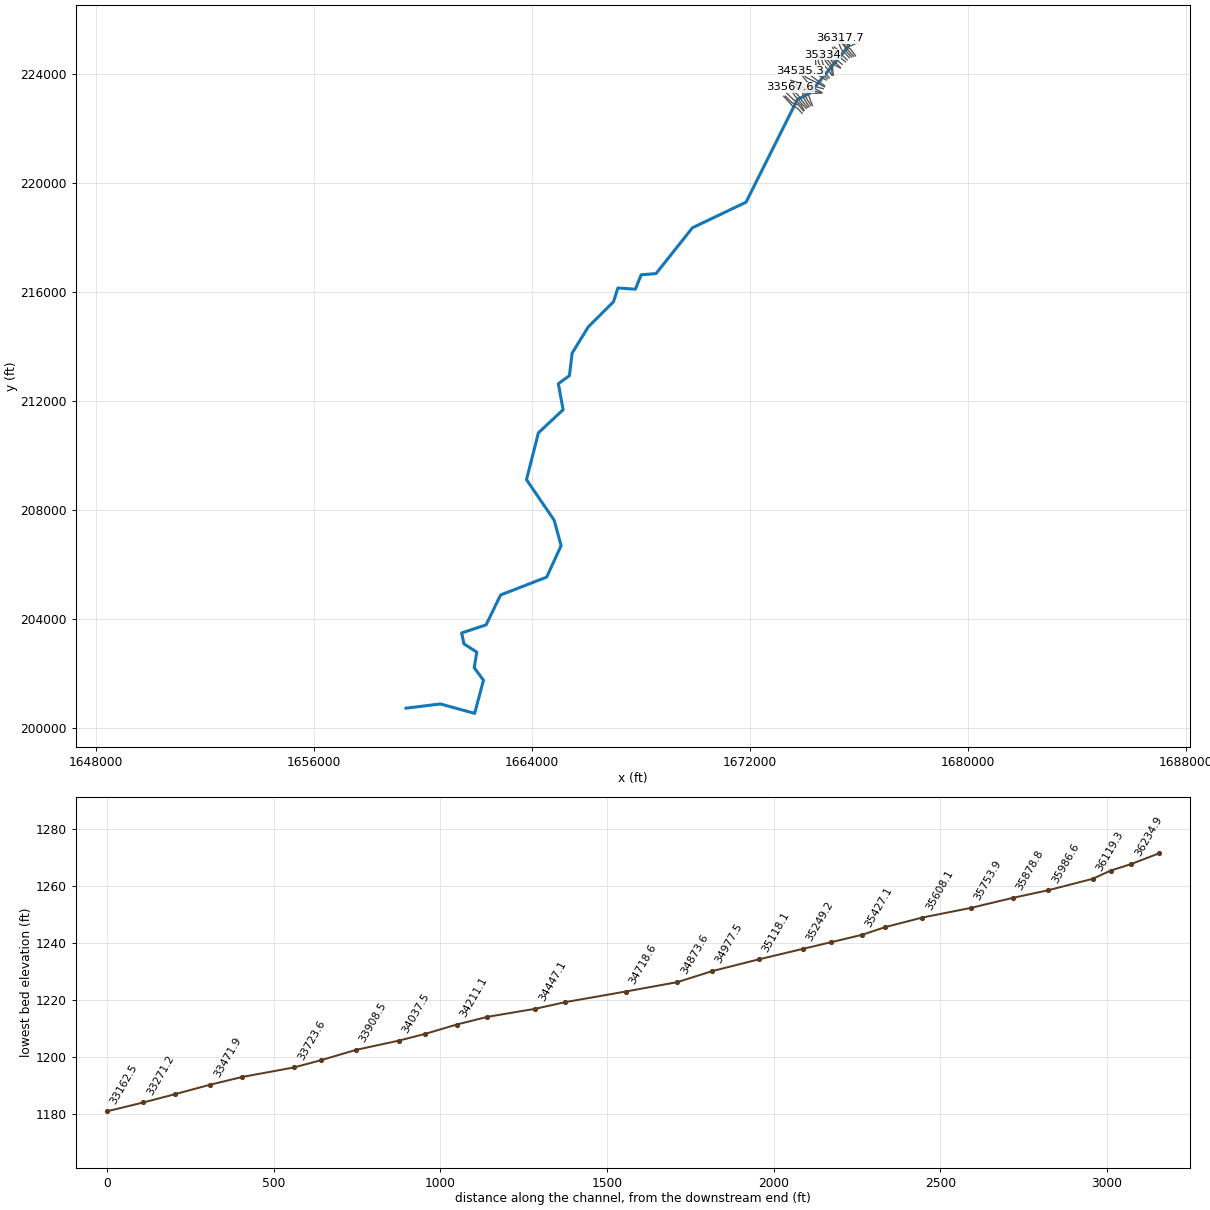
--- bchcrk.prj (project) ---

Proj Title=bchcrk
Current Plan=p01
Default Exp/Contr=0,0
English Units
Geom File=g01
Flow File=f01
Plan File=p01
BEGIN DESCRIPTION:
END DESCRIPTION:
DSS Export Rating Curves= 0
DSS Export Rating Curve Sorted= 0
DSS Export Volume Flow Curves= 0
DXF OffsetX= 0
DXF OffsetY= 0
DXF ScaleX= 0
DXF ScaleY= 0

--- bchcrk.p01 (plan) ---

Plan Title=Approximate Study - 100 yr
Program Version=4.00
Short Identifier=100 yr
Geom File=g01
Flow File=f01
Subcritical Flow
K Sum by GR= 0
Std Step Tol= 0.01
Critical Tol= 0.01
Num of Std Step Trials= 20
Max Error Tol= 0.3
Flow Tol Ratio= 0.001
Split Flow NTrial= 30
Split Flow Tol= 0.02
Split Flow Ratio= 0.02
Log Output Level= 0
Friction Slope Method= 1
Unsteady Friction Slope Method= 2
Unsteady Bridges Friction Slope Method= 1
Parabolic Critical Depth
Global Vel Dist= 0 , 0 , 0
Global Log Level= 0
CheckData=True
Encroach Param=-1 ,0,0, 0
Run HTab= 0
Run UNet= 0
Run PostProcess= 0
Run WQNet= 0
UNET Theta= 0
UNET Theta Warmup= 0
UNET ZTol= 0
UNET ZSATol= 0
UNET MxIter= 0
UNET MaxInSteps= 0
UNET DtIC= 0
UNET DtMin= 0
UNET MaxCRTS= 0
UNET WFStab= 0
UNET SFStab= 0
UNET WFX= 1
UNET SFX= 1
UNET DSS MLevel= 1
UNET DZMax Abort= 0
UNET Convert EG Bridges= 0
UNET Use Existing IB Tables= 0
UNET Froude Reduction=False
UNET Froude Limit= 0
UNET Froude Power= 0
UNET Time Slicing=0,0, 5
Write IC File= 0
Echo Input=False
Echo Output=False
Write Detailed= 0
Detailed Automatic Start=False, 0
WQ ULTIMATE=-1
WQ Max Comp Step=1HOUR
WQ Output Interval=15MIN
WQ Output Selected Increments= 0
WQ Output face flow=0
WQ Output face velocity=0
WQ Output face area=0
WQ Output face dispersion=0
WQ Output cell volume=0
WQ Output cell surface area=0
WQ Output cell continuity=0
WQ Output face conc=0
WQ Output face dconc_dx=0
WQ Output face courant=0
WQ Output face peclet=0
WQ Output face adv mass=0
WQ Output face disp mass=0
WQ Output cell mass=0
WQ Output cell source sink temp=0
WQ Output cell source sink nsm=0
WQ Output MaxMinRange=-1
WQ Daily Max Min Mean=-1
WQ Daily Range=0
WQ Daily Time=0
WQ Create Restart=0
WQ Fixed Restart=0
WQ System Summary=False
Sorting and Armoring Iterations= 10
XS Update Threshold= 0.02
Hydraulics Update Threshold= 0.02
Energy Slope Method= 1
Volume Change Method= 0
XS Weighting Method= 0
Number of US Weighted Cross Sections= 1
Number of DS Weighted Cross Sections= 1
Upstream XS Weight=0.25
Main XS Weight=0.5
Downstream XS Weight=0.25
Number of DS XS's Weighted with US Boundary= 1
Upstream Boundary Weight= 1
Weight of XSs Associated with US Boundary= 0
Number of US XS's Weighted with DS Boundary= 1
Downstream Boundary Weight= 0.5
Weight of XSs Associated with DS Boundary= 0.5
Sediment Output Level= 4
Mass or Volume Output= 0
Output Increment Type= 1
Profile and TS Output Increment= 10
XS Output Flag= 0
XS Output Increment= 10
Disregard all LS=0
Disregard all Conn=0
Disregard all Breaches=0
Disregard all Pumps=0

--- bchcrk.f01 (steady flow) ---

Flow Title=USGS Regression Equation
Program Version=4.00
Number of Profiles= 1
Profile Names=P100yr
River Rch & RM=bchcrk,Main            ,36317.7
     371
River Rch & RM=bchcrk,Main            ,34718.6
     399
River Rch & RM=bchcrk,Main            ,34447.1
     457
River Rch & RM=bchcrk,Main            ,32657.8
     498
River Rch & RM=bchcrk,Main            ,32301.1
     559
River Rch & RM=bchcrk,Main            ,29951.7
     595
River Rch & RM=bchcrk,Main            ,29515.6
     798
River Rch & RM=bchcrk,Main            ,27826.8
     852
River Rch & RM=bchcrk,Main            ,25760.5
     935
River Rch & RM=bchcrk,Main            ,25467.3
    1178
River Rch & RM=bchcrk,Main            ,21256.7
    1251
River Rch & RM=bchcrk,Main            ,20932.2
    1419
River Rch & RM=bchcrk,Main            ,16167.3
    1524
River Rch & RM=bchcrk,Main            ,15592.8
    1804
River Rch & RM=bchcrk,Main            ,11340
    1884
River Rch & RM=bchcrk,Main            ,10701.6
    2305
Boundary for River Rch & Prof#=bchcrk,Main            , 1
Up Type= 0
Dn Type= 3
Dn Slope=0.0106
DSS Import GetInterval= 0
DSS Import GetPeak= 0
DSS Import FillOption= 0

--- bchcrk.g01 (geometry) ---

Geom Title=USGS 3m DEM
Program Version=4.00

River Reach=bchcrk          ,Main
Reach XY= 30
     1675641.023      225059.641     1674199.393       223301.55
     1673751.831      223081.202      1671866.45      219309.825
     1669899.543      218371.442     1668562.524      216690.011
     1668017.643      216646.777     1667805.445      216116.225
     1667162.588       216161.34     1667001.591       215654.15
     1666076.197      214733.427     1665483.521      213769.299
     1665383.772      212941.975     1664976.928      212649.094
     1665153.392      211694.728     1664245.206      210843.768
      1663809.24      209126.917     1664826.348      207636.447
     1665079.929      206706.607      1664549.59      205551.754
     1662858.381      204895.105     1662326.073      203798.071
     1661430.836      203502.815     1661513.152      203101.841
     1661984.435      202798.924     1661890.534      202227.997
     1662230.149      201765.487     1661907.023      200550.883
      1660649.35      200896.538     1659387.905      200741.158

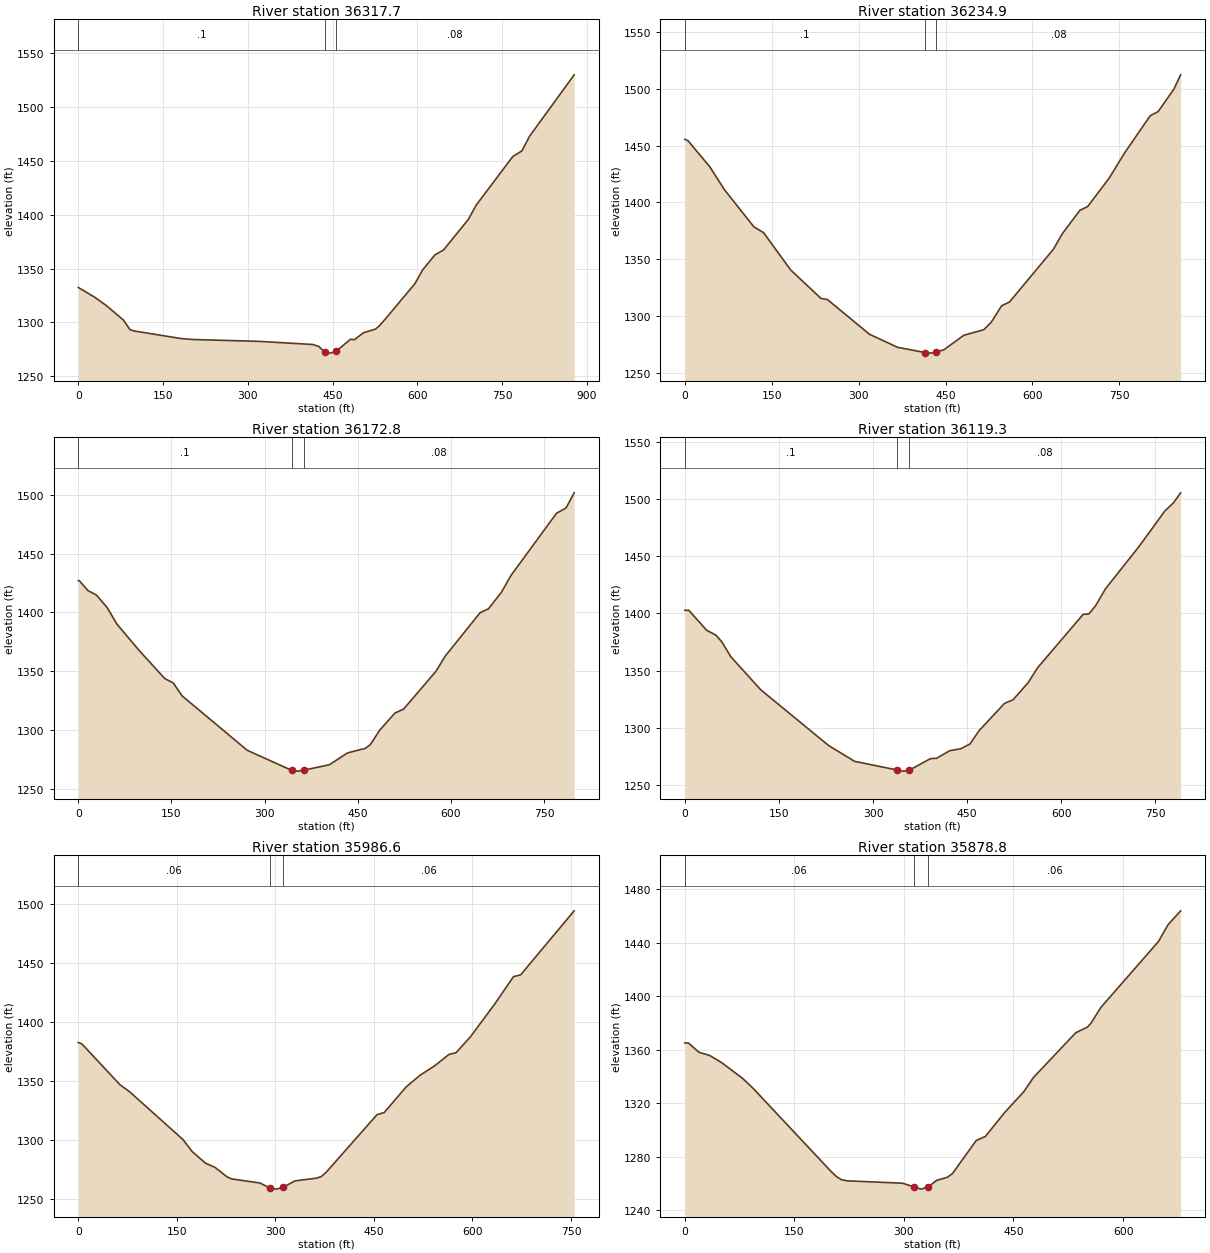
Type RM Length L Ch R = 1 ,36317.7 ,88.8,82.8,76.8
XS GIS Cut Line= 4
     1676048.586      225208.626     1675701.126      225041.196
     1675598.711      225067.682      1675309.14       225323.03
#Sta/Elev= 30
       0 1332.41    28.5 1323.51    50.2 1315.33      80 1302.05    91.2 1293.36
      98 1292.04   181.2 1284.96   203.7 1284.01   318.2 1282.34   414.8 1279.42
   425.7 1277.56   436.6 1272.04   446.6 1271.37   456.6 1273.23   481.7 1284.28
   488.5 1283.86   504.6 1290.26   526.1 1293.76   533.3 1297.05   545.6 1304.51
   595.8 1336.05   609.3 1348.74     631 1362.68   646.3 1367.28   690.4 1395.83
   703.9 1408.82   768.9 1454.19     785  1459.4   798.5 1472.99   877.5 1530.16
#Mann= 3 , 0 , 0
       0      .1       0   436.6    .045       0   456.6     .08       0
Bank Sta=436.6,456.6
XS Rating Curve= 0 ,0
Exp/Cntr=0.3,0.1

Type RM Length L Ch R = 1 ,36234.9 ,72.9,62.1,50
XS GIS Cut Line= 4
     1675885.929      224679.474     1675694.324      224934.327
      1675513.88       225031.06     1675294.372      225280.332
#Sta/Elev= 30
       0  1455.5     5.2 1454.49    43.2 1431.35    68.5  1411.2   119.3 1378.54
     136 1373.48   182.7 1340.73     235 1315.74   246.1 1314.74   318.8 1284.22
   366.9 1272.83   414.1  1268.2   424.1 1267.65   434.1 1268.59   447.1 1270.59
   481.6 1283.35   516.1 1288.25     529 1294.94   546.8 1309.27   560.3 1312.53
   636.4 1359.06   651.7  1372.7   681.9 1393.18   695.4 1396.47   732.4  1421.4
   759.1 1443.62   803.4 1476.32   816.9 1479.86     844 1499.57   855.7 1512.16
#Mann= 3 , 0 , 0
       0      .1       0   414.1    .045       0   434.1     .08       0
Bank Sta=414.1,434.1
XS Rating Curve= 0 ,0
Exp/Cntr=0.3,0.1

Type RM Length L Ch R = 1 ,36172.8 ,62.9,53.6,44.8
XS GIS Cut Line= 4
     1675815.664      224662.153     1675631.501      224863.059
     1675511.515      225017.924     1675289.681      225262.081
#Sta/Elev= 30
       0 1426.94     1.6 1426.94    15.4 1418.57    29.1 1414.82    46.9 1403.76
    61.9 1390.26    97.9 1367.75   139.1 1343.92   152.9 1340.14   166.9  1329.3
   271.9 1283.03   343.3 1266.07   353.3 1265.34   363.3 1266.17   404.2 1270.75
   433.3 1280.78   462.2 1284.71   470.3  1287.9   485.3 1300.15   509.8 1314.62
   523.5 1317.87   575.8 1350.05   590.8 1362.98   646.7 1399.68   660.4  1403.1
   681.3 1417.21   696.3 1431.17     770 1484.22   785.2 1488.59   798.3 1501.49
#Mann= 3 , 0 , 0
       0      .1       0   343.3    .045       0   363.3     .08       0
Bank Sta=343.3,363.3
XS Rating Curve= 0 ,0
Exp/Cntr=0.3,0.1

Type RM Length L Ch R = 1 ,36119.3 ,120.4,132.7,145
XS GIS Cut Line= 4
      1675744.55      224638.549     1675562.168      224821.102
      1675503.57      225003.173      1675279.49       225259.87
#Sta/Elev= 30
       0 1402.77     6.4 1402.77    35.1 1385.22    49.4 1381.22      59 1375.29
    73.3 1362.34     121 1333.45   229.3 1284.76   270.6 1270.99   337.9 1263.51
   347.9 1262.47   357.9 1263.34   391.4 1273.34   401.1 1273.68   422.4 1280.35
   439.7 1281.97   454.5  1286.2   469.1 1297.88   509.5 1321.58     523 1324.65
     547 1339.57   562.4 1352.81   634.7 1399.19     644 1399.59   654.9 1407.06
   670.3 1421.45   724.8 1459.14   765.1 1489.52   778.6 1496.47   790.1 1505.26
#Mann= 3 , 0 , 0
       0      .1       0   337.9    .045       0   357.9     .08       0
Bank Sta=337.9,357.9
XS Rating Curve= 0 ,0
Exp/Cntr=0.3,0.1

Type RM Length L Ch R = 1 ,35986.6 ,111.7,107.8,103.9
XS GIS Cut Line= 4
      1675664.56      224608.785     1675567.827      224703.657
     1675370.642      224897.122     1675242.285      225215.224
#Sta/Elev= 30
       0 1382.68     5.6  1381.4    63.5 1346.84    77.9 1341.05   159.3 1300.49
   173.5 1290.19   193.7 1280.44   208.2 1276.84   226.5 1268.84   233.7  1267.1
   276.7 1263.68   291.3  1259.4   301.3 1258.49   311.3 1259.91   329.7 1265.44
   362.7 1267.78   369.9 1269.19     377  1272.6   454.8  1321.6   465.7 1323.37
     499 1345.04   520.3 1354.98   542.2 1362.83   564.1  1372.5     575 1374.05
   596.8 1387.42   634.4 1415.65   662.4 1438.43   673.4 1440.01   754.8 1494.19
#Mann= 3 , 0 , 0
       0     .06       0   291.3    .045       0   311.3     .06       0
Bank Sta=291.3,311.3
XS Rating Curve= 0 ,0
Exp/Cntr=0.3,0.1

Type RM Length L Ch R = 1 ,35878.8 ,121,124.9,128.7
XS GIS Cut Line= 4
     1675576.817      224528.114      1675416.72      224685.072
     1675297.432      224846.216     1675101.758      225008.405
#Sta/Elev= 30
       0 1364.95       5 1364.95    19.4 1358.01    33.9 1355.69    50.6 1350.24
      79 1338.58    93.2 1331.26     200 1269.13   207.2 1265.35   214.3 1262.83
   222.1 1261.99   298.1  1260.2   313.3 1257.51   323.3 1255.78   333.3 1257.48
   344.7  1262.3   359.2 1264.58   366.4 1267.37   398.9 1292.07   411.6 1295.18
   437.8 1312.94   464.2 1328.62   477.3 1339.15   535.2 1372.58   551.1  1376.8
   556.3 1379.88   569.5 1391.43   648.5 1440.78   661.6 1453.28   678.8 1463.67
#Mann= 3 , 0 , 0
       0     .06       0   313.3    .045       0   333.3     .06       0
Bank Sta=313.3,333.3
XS Rating Curve= 0 ,0
Exp/Cntr=0.3,0.1

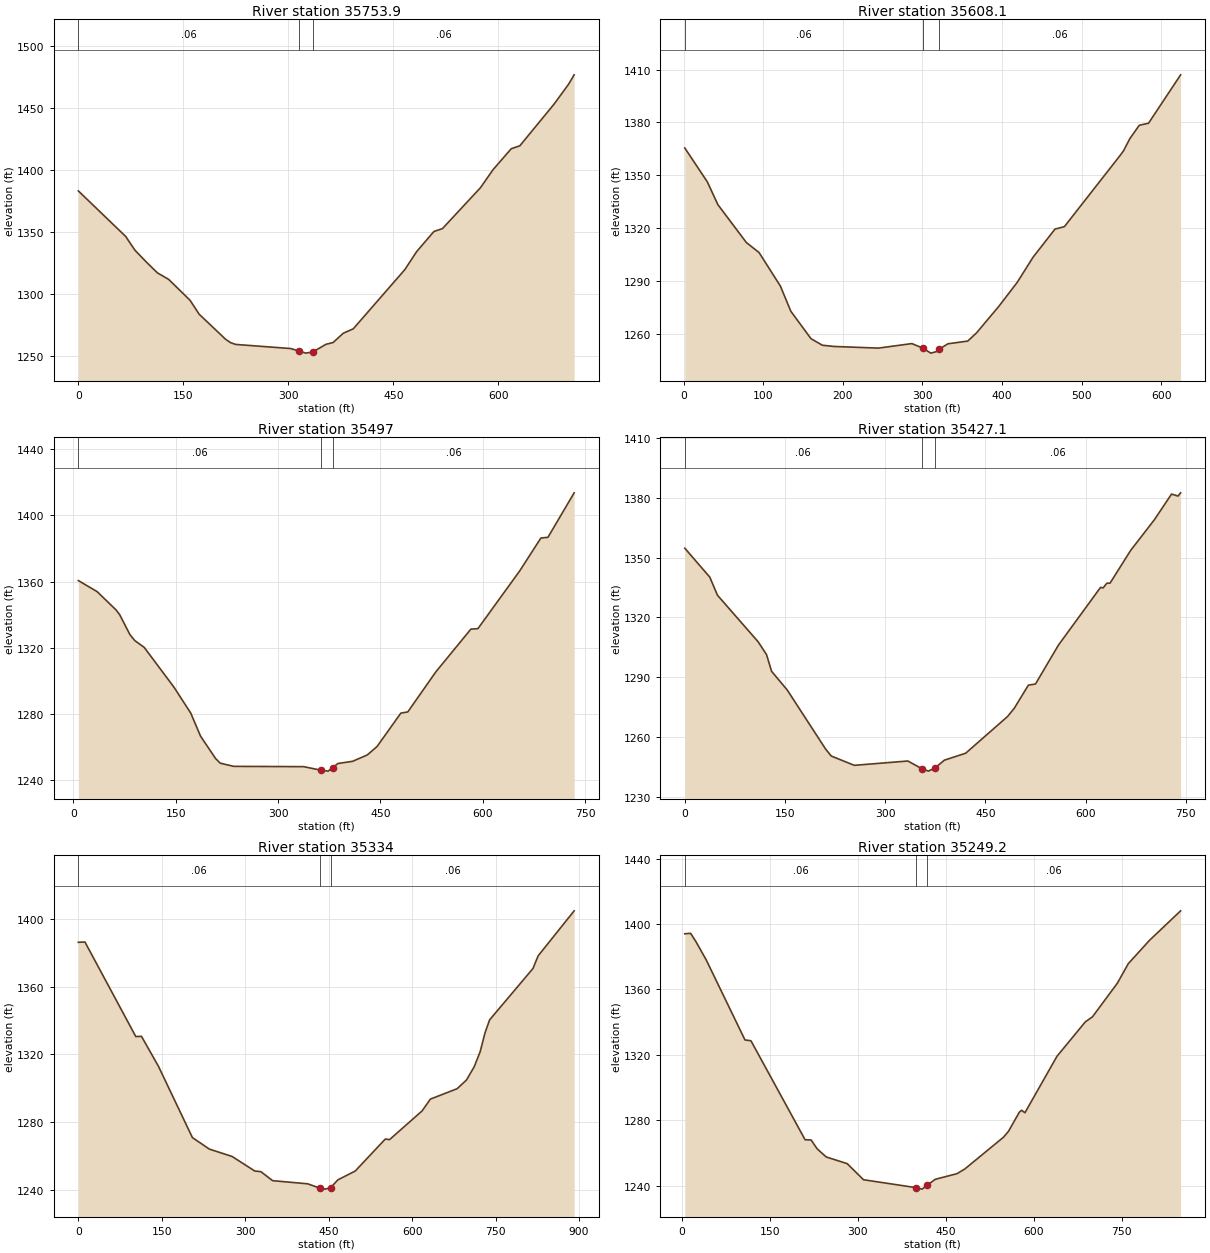
Type RM Length L Ch R = 1 ,35753.9 ,146.5,145.8,145.1
XS GIS Cut Line= 4
      1675512.02      224459.966     1675378.083       224569.72
       1675199.5      224746.443     1675039.519      224980.833
#Sta/Elev= 30
       0 1383.12    67.7 1346.35    80.9 1335.25      97 1325.83     113    1317
     129 1311.77   159.5 1294.96   172.6 1283.66   210.4 1263.44   217.6  1260.7
   224.7 1259.31   303.6 1255.97   315.1 1253.94   325.1 1252.29   335.1 1253.27
   353.7  1259.4   363.9 1260.82   378.3  1268.3   392.7 1271.89   466.4 1319.66
   483.3 1334.22   507.9 1350.37   520.1 1352.71   574.3 1385.63   592.3 1400.18
   618.3 1417.11   630.6 1419.48   679.7 1453.21   700.1 1469.02   708.2 1476.71
#Mann= 3 , 0 , 0
       0     .06       0   315.1    .045       0   335.1     .06       0
Bank Sta=315.1,335.1
XS Rating Curve= 0 ,0
Exp/Cntr=0.3,0.1

Type RM Length L Ch R = 1 ,35608.1 ,110.7,111.2,111.6
XS GIS Cut Line= 4
     1675391.607       224370.11     1675258.716      224478.934
     1675114.315      224629.614     1674990.841      224839.937
#Sta/Elev= 30
     1.6  1365.5      30 1346.18    43.1 1333.33    78.9 1311.78    94.9 1306.06
   121.7 1287.01   134.8 1272.69   160.1 1257.13   174.4 1253.39     189  1252.7
   244.7 1251.76   286.8 1254.33   300.6 1251.76   310.6 1248.91   317.8 1249.77
   320.6 1251.05   332.2 1254.22     357 1255.76     368  1260.4   396.1 1275.52
   419.1  1289.1   439.2 1303.51   466.6  1319.4   478.4 1320.79   548.9 1361.54
   552.7  1363.9   560.6 1370.77   572.4 1378.37   584.1 1379.57   624.4 1407.07
#Mann= 3 , 0 , 0
     1.6     .06       0   300.6    .045       0   320.6     .06       0
#XS Ineff= 2 , 0
       0     286                       0
Permanent Ineff=
       F       F
Bank Sta=300.6,320.6
XS Rating Curve= 0 ,0
Exp/Cntr=0.3,0.1

Type RM Length L Ch R = 1 ,35497   ,71.5,69.9,68.2
XS GIS Cut Line= 4
     1675333.437      224242.318     1675224.185      224360.693
     1675013.862      224572.063      1674970.69      224843.175
#Sta/Elev= 30
     7.5 1360.68      35 1354.01    62.6 1343.02      68 1340.15      83 1328.08
    90.2 1324.42     104 1320.32   147.7 1296.21   172.2  1280.6   186.5 1266.71
   208.6 1253.16   215.3 1250.38   235.1 1248.44   337.6 1248.26   363.4 1246.08
   373.4 1245.56  380.12 1247.68   387.7 1250.16   409.3 1251.49   430.8 1255.34
   445.1 1260.44   479.9 1280.59   490.1 1281.33   531.2 1305.53   582.5 1331.34
   592.8 1331.62     654 1366.48   685.1  1386.4   695.4 1386.79   733.8 1413.68
#Mann= 3 , 0 , 0
     7.5     .06       0   363.4    .045       0  380.12     .06       0
#XS Ineff= 2 , 0
       0     323                       0
Permanent Ineff=
       F       F
Bank Sta=363.4,380.12
XS Rating Curve= 0 ,0
Exp/Cntr=0.3,0.1

Type RM Length L Ch R = 1 ,35427.1 ,95.2,93.1,91
XS GIS Cut Line= 4
     1675320.453      224237.219     1675139.428       224332.44
     1674983.517      224510.326     1674942.708      224808.546
#Sta/Elev= 30
       0 1354.75    37.4 1340.24    48.9 1331.15   109.8 1307.77   122.4  1301.3
   129.9 1292.96   153.3 1283.59   210.8 1253.91   219.3 1250.41   253.7 1245.76
   333.9 1247.93   354.6 1244.08   364.6 1242.85   374.6 1244.48   388.5 1248.35
   420.4 1251.84     483 1270.24   493.2 1274.44   514.2    1286   524.9  1286.6
   559.2 1306.09   622.2 1335.06   626.2 1334.84   631.6 1337.16   636.5 1337.22
   667.4 1353.69   702.7 1368.98   728.5 1381.92   738.2 1380.94   742.1 1382.55
#Mann= 3 , 0 , 0
       0     .06       0   354.6    .045       0   374.6     .06       0
Bank Sta=354.6,374.6
XS Rating Curve= 0 ,0
Exp/Cntr=0.3,0.1

Type RM Length L Ch R = 1 ,35334   ,81,84.9,88.7
XS GIS Cut Line= 4
     1675065.562      223972.583     1675035.836       224294.77
     1674928.058      224441.264      1674665.61       224724.12
#Sta/Elev= 30
       0 1386.36    11.9 1386.53   103.3 1330.57   113.5  1330.7   144.1 1312.91
   205.1 1270.76   235.5 1263.96   276.4 1259.59   317.1    1251   328.2 1250.59
   349.3 1245.26   412.3 1243.41   433.6 1240.91   443.6 1240.26   453.6 1241.16
   466.6 1245.75   497.8 1250.98   551.8  1269.9   559.5 1269.57     618 1286.57
   632.9 1293.55   680.9 1299.69   697.8 1304.87   711.6 1312.68   722.3 1321.54
   731.1 1332.81   739.3 1340.43   817.2 1370.82   826.6 1378.35   891.3 1404.98
#Mann= 3 , 0 , 0
       0     .06       0   433.6    .045       0   453.6     .06       0
Bank Sta=433.6,453.6
XS Rating Curve= 0 ,0
Exp/Cntr=0.3,0.1

Type RM Length L Ch R = 1 ,35249.2 ,131.5,131,130.5
XS GIS Cut Line= 4
     1675035.798      223968.862     1674992.934      224247.683
     1674854.811       224384.76     1674650.728      224698.077
#Sta/Elev= 30
     5.3 1394.04    15.2 1394.33      24 1389.42    41.8  1378.1   107.9 1329.13
   118.1 1328.63   210.4 1268.11   220.7 1267.97   230.9 1262.58   246.4 1257.58
   282.1 1253.52     310 1243.66     400  1238.8     410 1237.92     418 1240.15
   432.4 1243.94   469.3 1247.36   482.7 1250.24   548.6 1269.66   557.1 1273.25
   575.7 1284.99   579.4 1286.13   585.2 1284.64   639.8 1319.14   688.2 1340.22
   700.3 1343.26   742.8 1363.86   761.4 1375.77   797.6 1390.06   850.6 1408.08
#Mann= 3 , 0 , 0
     5.3     .06       0     400    .045       0     418     .06       0
Bank Sta=400,418
XS Rating Curve= 0 ,0
Exp/Cntr=0.3,0.1

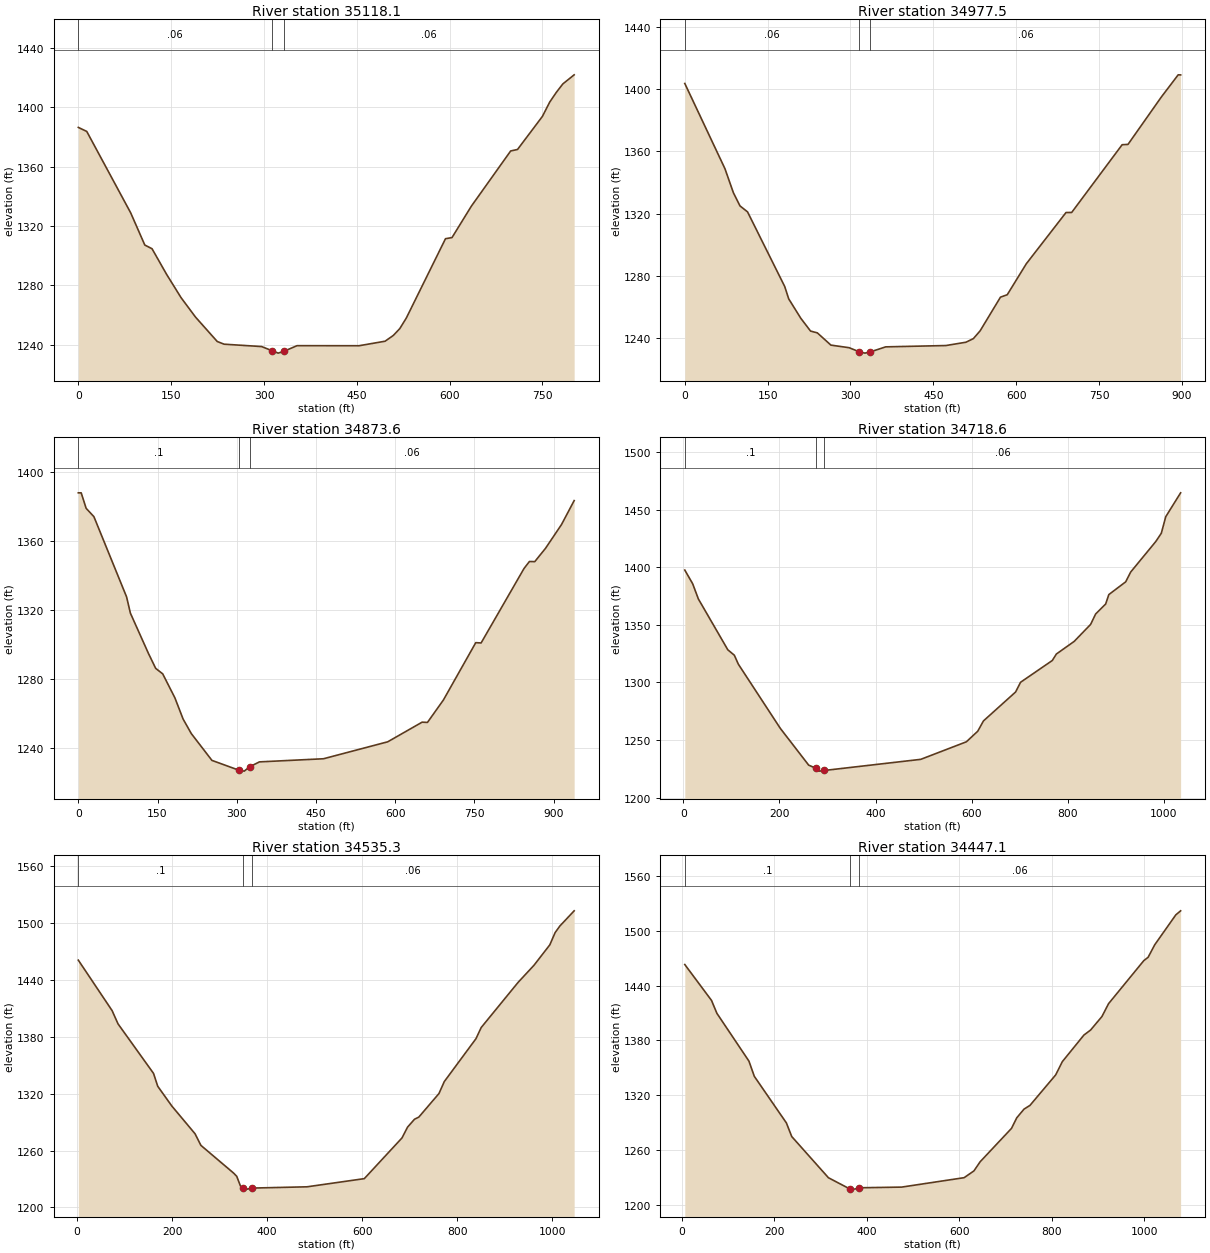
Type RM Length L Ch R = 1 ,35118.1 ,144.9,140.6,136.3
XS GIS Cut Line= 4
     1675005.491      223972.484     1674900.852      224152.462
     1674693.668      224366.971     1674613.096      224650.541
#Sta/Elev= 30
       0 1386.46    13.6 1383.76    84.6 1328.86   107.4 1307.17   119.1 1304.66
   142.6 1287.42     166 1271.68   189.5  1258.5   224.5 1242.11   235.5 1240.31
   296.2  1238.7     313 1235.91     323 1234.28     333 1235.65   353.5 1239.31
   453.5 1239.26   495.7 1242.31     509 1246.21   519.5 1250.84     530 1257.95
   593.3 1311.43   603.8 1312.18     635 1333.31   698.6 1370.58   709.7 1371.59
   749.9 1393.89   761.8  1403.6   772.4 1410.11   782.9 1415.78   801.2 1421.92
#Mann= 3 , 0 , 0
       0     .06       0     313    .045       0     333     .06       0
Bank Sta=313,333
XS Rating Curve= 0 ,0
Exp/Cntr=0.3,0.1

Type RM Length L Ch R = 1 ,34977.5 ,101.8,104,106
XS GIS Cut Line= 4
     1674920.463      223879.571      1674820.01      223991.185
     1674526.092      224420.901      1674511.21       224647.85
#Sta/Elev= 30
       0 1403.76    72.7 1348.89      88 1333.41    99.9 1324.94   113.6 1321.09
   180.9 1273.06   188.2 1265.06   210.1 1252.57   227.7 1244.35     240 1243.19
   264.6  1235.3   297.6 1233.64     316 1230.99     326 1230.15     336 1230.94
   363.7 1234.18   472.6 1235.03     509 1237.16   522.5 1239.48   534.7 1244.47
   571.6 1266.18   583.9 1267.76   618.4 1287.69   690.3 1320.68   700.5 1320.69
   791.9 1364.32   802.5 1364.53     863  1395.1   893.4 1409.32   897.8 1409.27
#Mann= 3 , 0 , 0
       0     .06       0     316    .045       0     336     .06       0
Bank Sta=316,336
XS Rating Curve= 0 ,0
Exp/Cntr=0.3,0.1

Type RM Length L Ch R = 1 ,34873.6 ,146.4,154.9,163.6
XS GIS Cut Line= 4
     1674859.076      223842.366     1674760.483      223935.378
      1674429.36      224324.168     1674408.897      224616.226
#Sta/Elev= 30
       0 1388.09     5.4 1388.09    14.8 1379.08    29.5 1374.23    91.4 1327.57
    98.6 1318.13   132.9 1294.64   146.5 1286.03   159.8 1282.84   182.8 1268.94
   198.4 1256.58     214  1248.1     253 1232.54   304.2 1226.82   314.2  1226.3
   324.2  1228.8   342.9 1231.67   464.2 1233.49   585.9 1243.35     651 1254.76
   661.1 1254.61   691.2  1267.6   752.6 1300.99   762.7 1300.81     844 1344.11
   854.2 1348.17   864.3 1348.08   884.6  1355.8   915.1 1369.72   938.9 1383.57
#Mann= 3 , 0 , 0
       0      .1       0   304.2    .045       0   324.2     .06       0
Bank Sta=304.2,324.2
XS Rating Curve= 0 ,0
Exp/Cntr=0.3,0.1

Type RM Length L Ch R = 1 ,34718.6 ,185.9,183.4,180.8
XS GIS Cut Line= 4
     1674806.989      223793.999     1674676.772       223873.99
     1674243.336      224138.144     1673878.728      224225.575
#Sta/Elev= 30
     2.8 1397.66    19.2 1385.76    31.1 1372.53    92.4  1328.4     106 1323.67
   114.3 1315.92   201.8  1260.1   260.8 1228.22  275.89 1225.46   282.9 1223.01
   292.9 1223.56   494.2 1233.24   589.2 1248.48   612.9 1257.67   624.8 1266.62
   691.7 1291.73   702.1  1300.2   768.2 1319.11   776.6 1324.71   813.7 1335.68
     848 1350.47   858.4  1359.5   879.3 1368.18   885.9 1376.36     921 1387.43
   931.4 1395.94   983.5 1422.35   995.2 1429.64  1004.4 1443.99  1035.4 1464.74
#Mann= 3 , 0 , 0
     2.8      .1       0  275.89    .045       0   292.9     .06       0
Bank Sta=275.89,292.9
XS Rating Curve= 0 ,0
Exp/Cntr=0.3,0.1

Type RM Length L Ch R = 1 ,34535.3 ,83.6,88.2,92.9
XS GIS Cut Line= 4
     1674749.126      223584.449     1674501.743      223761.506
     1674240.408      223958.488      1673862.14      224128.395
#Sta/Elev= 30
     2.5 1461.05    73.6 1407.75      86 1393.82   160.8 1341.45   169.6 1327.91
   199.3 1307.01   248.1 1277.76   260.5 1265.46   329.3  1236.2   335.9 1232.78
   343.8 1222.47   348.3 1220.75   358.3 1219.25   368.3 1220.36   483.8 1221.69
   604.4 1230.32   683.8 1273.34   695.4  1284.7   710.1 1293.07   719.1 1295.29
   761.6 1320.23   772.7 1332.77   839.4 1378.09   850.5 1389.95   928.3  1437.7
   961.6 1455.67   994.9 1477.25    1006 1490.12    1016  1497.1  1046.1 1513.15
#Mann= 3 , 0 , 0
     2.5      .1       0   348.3    .045       0   368.3     .06       0
#XS Ineff= 2 , 0
       0                     388       0
Permanent Ineff=
       F       F
Bank Sta=348.3,368.3
XS Rating Curve= 0 ,0
Exp/Cntr=0.3,0.1

Type RM Length L Ch R = 1 ,34447.1 ,146.3,144.1,141.9
XS GIS Cut Line= 4
     1674745.601      223542.867     1674535.393      223658.202
     1674096.377       223875.85     1673848.965      224121.402
#Sta/Elev= 30
     6.4 1463.26    64.2  1423.9    75.8 1409.77   145.1 1357.34   156.7 1340.67
   226.1 1289.52   237.6 1274.64   316.9 1229.48   363.4  1217.1   373.4 1216.96
   383.4 1218.44   475.2 1219.18   610.3 1229.51   631.6 1236.98   644.9 1246.93
   712.8 1283.61   724.1 1295.16   739.8 1304.68   752.7 1308.81   808.3 1342.25
   822.6 1356.74   869.3 1385.92   883.7 1391.41   908.3 1406.26   922.6 1420.33
   998.8 1467.55  1008.2 1471.28  1022.5    1485    1068 1517.74  1078.4 1522.17
#Mann= 3 , 0 , 0
     6.4      .1       0   363.4    .045       0   383.4     .06       0
#XS Ineff= 2 , 0
       0                     398       0
Permanent Ineff=
       F       F
Bank Sta=363.4,383.4
XS Rating Curve= 0 ,0
Exp/Cntr=0.3,0.1

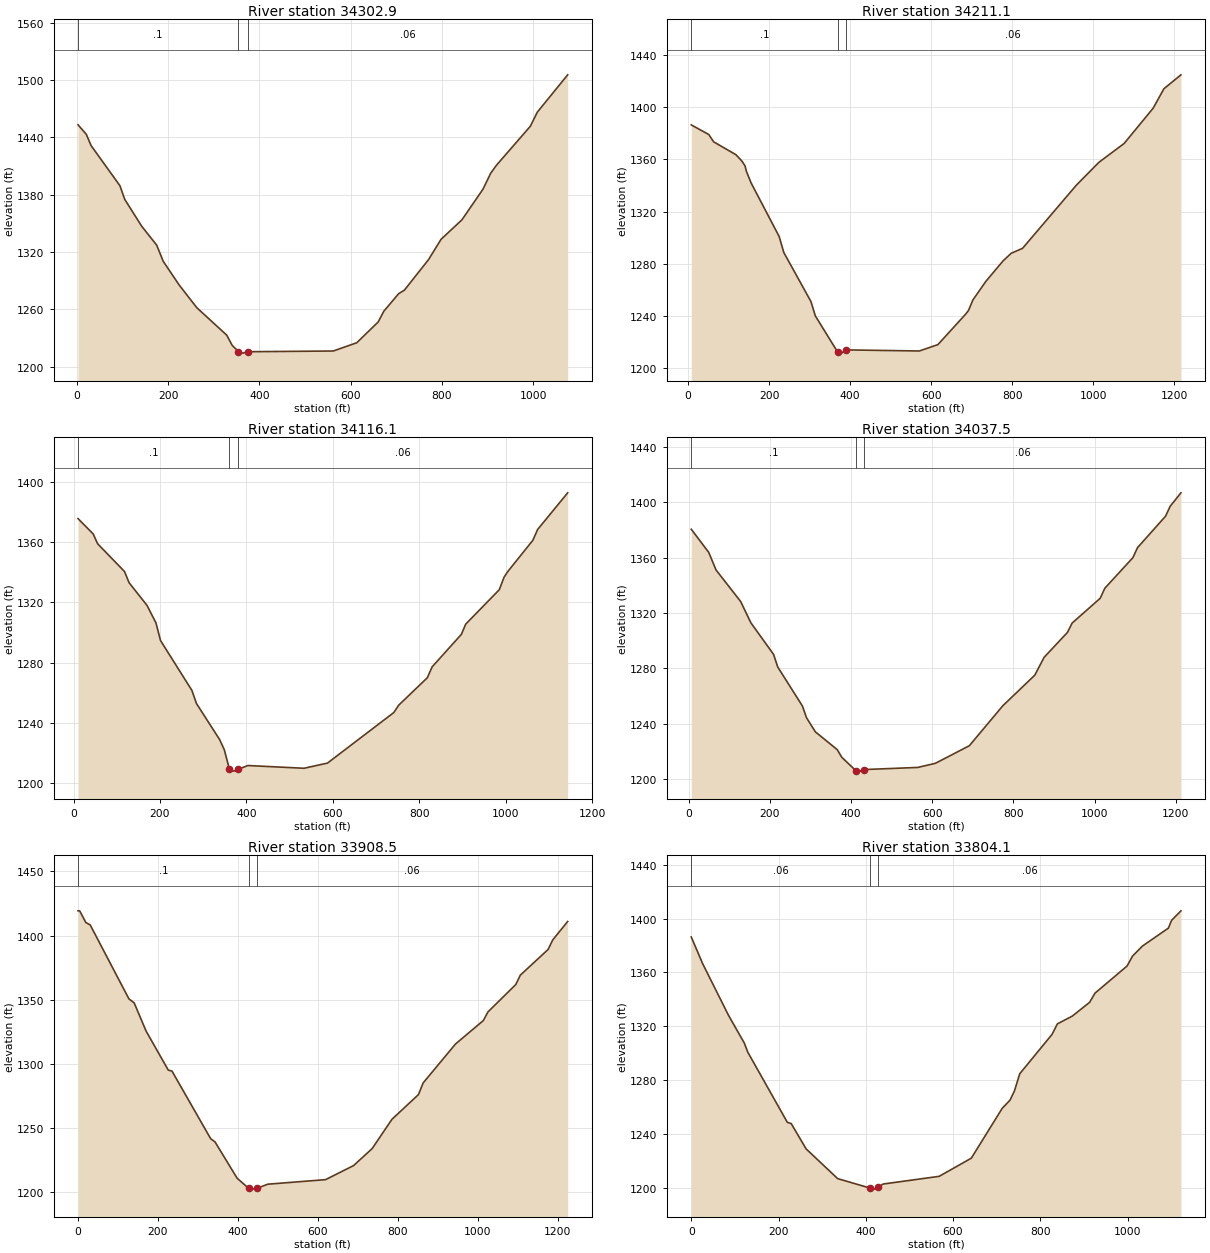
Type RM Length L Ch R = 1 ,34302.9 ,87,91.8,96.6
XS GIS Cut Line= 4
      1674699.12      223473.898     1674403.341      223557.609
      1674083.38      223752.934     1673848.989      224069.175
#Sta/Elev= 30
     2.6 1453.06    20.7 1443.13    31.3 1431.27    94.5 1389.29     105 1375.04
   142.2 1346.89   175.1  1327.1   189.3 1310.26   224.3 1285.44     263 1261.66
   328.6 1232.92   340.5 1222.29   354.2 1215.78   364.2 1214.13   374.2  1215.6
   562.1 1216.35   613.6 1224.99   660.5 1246.71     673 1258.04   705.3  1276.3
   717.9 1279.98   771.1  1312.1   798.5 1333.33   844.1 1353.61   890.2 1385.66
   907.1  1402.3   919.7 1410.67   994.1 1451.56  1009.4 1466.32  1075.9 1505.35
#Mann= 3 , 0 , 0
     2.6      .1       0   354.2    .045       0   374.2     .06       0
#XS Ineff= 2 , 0
       0                     395       0
Permanent Ineff=
       F       F
Bank Sta=354.2,374.2
XS Rating Curve= 0 ,0
Exp/Cntr=0.3,0.1

Type RM Length L Ch R = 1 ,34211.1 ,95.2,95.1,94.9
XS GIS Cut Line= 4
     1674643.288      223341.961     1674408.457       223470.41
     1674030.363      223611.323     1673512.261      223782.838
#Sta/Elev= 30
     7.8  1386.4      51 1379.03    63.1 1373.41   118.2 1363.53   133.2 1358.52
   140.6 1354.94   143.9 1350.82   155.5 1341.92   224.8 1300.86   236.4 1288.51
   303.3 1250.99   314.1 1240.01     369 1212.37     379 1211.44     389 1213.92
     571 1213.08   616.9 1217.98   685.5 1241.39   692.4 1244.16   703.1 1252.15
   735.1 1266.41   777.8 1282.18   797.8 1287.98   825.8 1291.77   958.2 1340.03
  1014.3 1357.69  1076.7 1372.17  1148.3 1399.19  1174.8 1414.07  1216.9 1424.78
#Mann= 3 , 0 , 0
     7.8      .1       0     369    .045       0     389     .06       0
#XS Ineff= 2 , 0
       0                     400       0
Permanent Ineff=
       F       F
Bank Sta=369,389
XS Rating Curve= 0 ,0
Exp/Cntr=0.3,0.1

Type RM Length L Ch R = 1 ,34116.1 ,80.5,78.6,76.7
XS GIS Cut Line= 4
     1674632.151      223326.939     1674348.464      223390.885
     1673999.669      223523.427     1673561.582      223718.752
#Sta/Elev= 30
    10.3 1375.57    45.3 1365.43    55.7 1358.89     118 1340.45   128.4 1333.12
     170 1318.03   190.8 1306.35   201.2 1294.75   273.9 1261.66   284.3 1253.04
   338.2 1229.01     349 1222.22   360.7 1209.38   370.7 1208.15   380.7 1209.32
   403.3 1211.86   533.4 1210.05   587.6 1213.47   741.2 1246.99   752.3 1251.81
   818.8 1270.08   829.9 1277.28   897.5 1298.81   907.6 1305.59   985.3 1328.43
   996.4 1336.74  1004.9 1340.44    1063  1361.2  1074.1 1368.37  1143.6 1392.66
#Mann= 3 , 0 , 0
    10.3      .1       0   360.7    .045       0   380.7     .06       0
#XS Ineff= 2 , 0
       0                     403       0
Permanent Ineff=
       F       F
Bank Sta=360.7,380.7
XS Rating Curve= 0 ,0
Exp/Cntr=0.3,0.1

Type RM Length L Ch R = 1 ,34037.5 ,146.7,129,111.2
XS GIS Cut Line= 4
     1674645.148      223314.057     1674328.907      223306.616
     1674005.225      223459.156     1673530.863      223714.009
#Sta/Elev= 30
     6.5 1380.41    49.5 1363.71    67.4 1351.07   128.2 1328.21   153.3 1312.88
   209.3 1290.03   219.4 1281.02   280.3 1252.79   290.4 1244.33   312.2 1234.15
   366.1 1221.31   377.3 1215.77   412.1 1206.11   422.1 1205.81   432.1 1206.94
   564.5 1208.48     608 1211.47   691.5 1224.16   773.8 1252.97   852.6 1275.06
   875.6 1287.95   933.1 1305.94   944.6 1312.67  1013.7 1330.56  1025.2 1337.83
  1094.2 1359.87  1105.7 1367.13  1174.7 1389.82  1186.2 1397.03  1212.6 1406.69
#Mann= 3 , 0 , 0
     6.5      .1       0   412.1    .045       0   432.1     .06       0
#XS Ineff= 2 , 0
       0                     455       0
Permanent Ineff=
       F       F
Bank Sta=412.1,432.1
XS Rating Curve= 0 ,0
Exp/Cntr=0.3,0.1

Type RM Length L Ch R = 1 ,33908.5 ,109,104.4,99.8
XS GIS Cut Line= 4
     1674301.003      222850.857     1674184.427      223175.138
     1674090.252      223385.461     1673521.562      223700.987
#Sta/Elev= 30
       0 1419.34     4.1 1419.34    19.6  1410.2    30.4  1408.4   127.4 1350.74
   140.5 1347.64   170.4 1325.64   225.9 1295.24   235.1 1294.52     332 1241.81
   342.8 1239.35   398.2 1211.04   426.8 1203.25   436.8 1202.55   446.8  1203.1
   475.1  1206.4   619.6 1209.94   689.7 1220.91   736.1 1234.14   785.6 1256.94
     852  1276.2   863.6 1285.24   944.7  1315.6  1014.3 1333.87  1025.9 1340.59
  1095.4 1361.89    1107 1369.26  1176.5 1389.27  1188.1 1396.73  1225.4 1411.05
#Mann= 3 , 0 , 0
       0      .1       0   426.8    .045       0   446.8     .06       0
Bank Sta=426.8,446.8
XS Rating Curve= 0 ,0
Exp/Cntr=0.3,0.1

Type RM Length L Ch R = 1 ,33804.1 ,80.4,80.5,80.7
XS GIS Cut Line= 4
     1674241.035      222867.692     1674066.637      223146.728
     1674019.201      223344.844     1673533.678      223679.687
#Sta/Elev= 30
       0 1386.35    25.9 1366.64    85.6 1327.98   121.5 1307.56   129.5 1300.77
   220.2  1248.6     229 1247.69   263.4  1228.8   335.6 1206.77     409 1199.81
     419 1198.96     429 1200.55   439.9 1202.75   568.3 1208.47   641.9 1221.95
   712.8 1259.04   730.7 1265.12   740.7  1271.9     753 1284.73   826.9 1313.94
   839.2 1321.77   873.5 1327.58     913 1337.76   925.4  1344.6   998.9 1364.76
  1011.5 1372.16  1034.2 1379.61  1093.7 1392.95  1100.9 1398.68  1122.4 1405.79
#Mann= 3 , 0 , 0
       0     .06       0     409    .045       0     429     .06       0
Bank Sta=409,429
XS Rating Curve= 0 ,0
Exp/Cntr=0.3,0.1

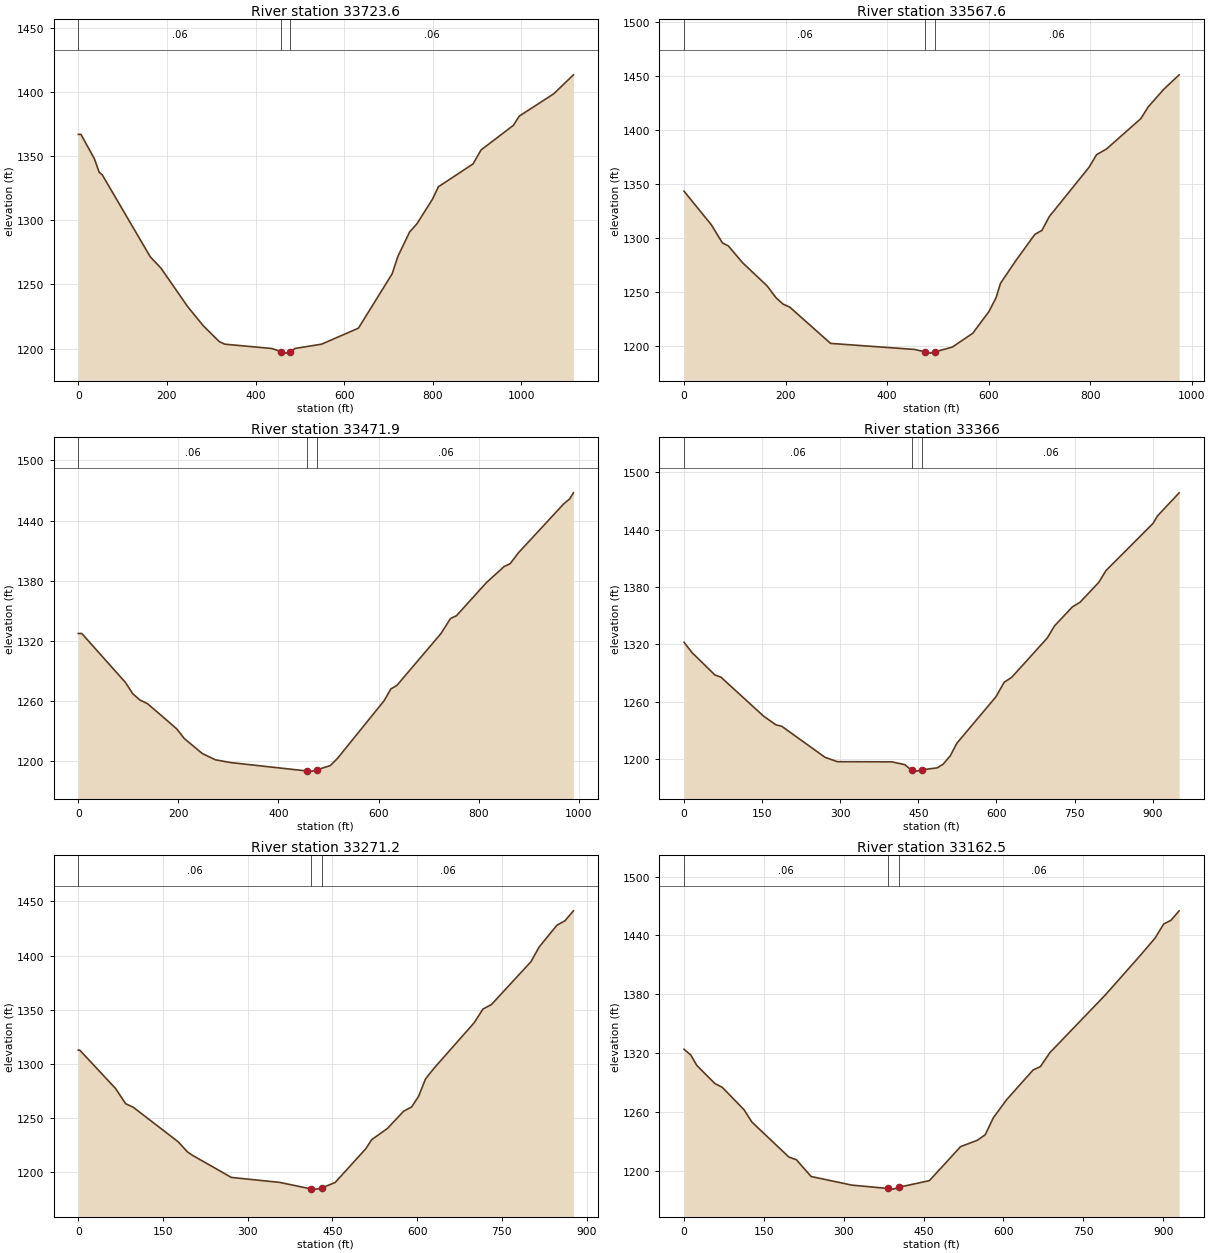
Type RM Length L Ch R = 1 ,33723.6 ,147,156,164.9
XS GIS Cut Line= 4
     1674181.948      222813.652     1673996.077      223103.984
     1673939.573      223330.003     1673519.702      223669.363
#Sta/Elev= 30
       0 1366.89       6 1366.89    36.5 1347.76    47.2 1337.33    54.1 1335.36
   162.4 1271.52   186.5 1262.72   246.7 1232.77     282  1217.8   318.5 1205.33
   330.9 1203.41   437.2 1200.03   458.5 1197.43   468.5 1196.44   478.5 1197.47
   489.4  1200.1   549.1 1203.41   632.3 1215.88   708.4 1258.23   721.5  1271.9
   747.8 1290.82     764 1297.06   799.6 1316.46   812.7 1326.03   890.9 1343.84
   909.1 1354.74   982.1 1373.93   995.1 1381.05  1073.3 1398.53  1117.6 1413.28
#Mann= 3 , 0 , 0
       0     .06       0   458.5    .045       0   478.5     .06       0
Bank Sta=458.5,478.5
XS Rating Curve= 0 ,0
Exp/Cntr=0.3,0.1

Type RM Length L Ch R = 1 ,33567.6 ,92.9,95.8,98.7
XS GIS Cut Line= 4
     1674126.178      222791.289     1673887.602      223073.115
     1673774.593      223237.746     1673491.371      223529.339
#Sta/Elev= 30
       0 1343.21      54 1311.95    75.7 1295.26    87.3 1292.49   115.5 1276.84
   163.8 1255.38   180.8 1244.68   195.2 1238.49   208.5 1235.68   288.7 1202.11
   454.8 1196.47   474.4 1194.29   484.4 1193.08   494.4 1194.21   528.7 1198.73
   568.9 1211.52   600.5 1231.46   614.8  1244.5   623.5 1257.78   652.6 1278.08
   691.2 1303.16   705.3 1306.94   719.5 1319.57   798.1 1365.46   812.6 1376.97
   832.5 1382.38   899.9 1410.45   914.5 1421.34   945.5 1437.84   975.4 1451.04
#Mann= 3 , 0 , 0
       0     .06       0   474.4    .045       0   494.4     .06       0
Bank Sta=474.4,494.4
XS Rating Curve= 0 ,0
Exp/Cntr=0.3,0.1

Type RM Length L Ch R = 1 ,33471.9 ,100.1,105.9,111.6
XS GIS Cut Line= 4
     1674075.914      222750.404     1673945.697      222884.341
      1673661.08      223208.024     1673465.755      223524.264
#Sta/Elev= 30
       0 1327.51       7 1327.51    94.2 1278.76   108.8 1267.48   123.5 1261.11
   137.9 1257.75   165.9 1245.83   196.5 1232.56   211.9 1222.87   247.8 1207.94
   274.1 1201.68     304 1198.94     458 1190.48     468 1190.39     478 1191.92
   503.5 1195.86   517.7 1202.92     611 1260.46   624.8 1272.32   636.7 1275.76
   724.9 1327.53   743.9 1342.49   755.8 1345.23   815.4 1378.11   851.1 1394.26
   863.1 1397.04   879.2 1407.69   970.3 1456.79   982.2 1461.67   989.5 1467.65
#Mann= 3 , 0 , 0
       0     .06       0     458    .045       0     478     .06       0
Bank Sta=458,478
XS Rating Curve= 0 ,0
Exp/Cntr=0.3,0.1

Type RM Length L Ch R = 1 ,33366   ,88.1,94.8,101.5
XS GIS Cut Line= 4
     1673997.784      222675.994     1673882.449      222876.901
      1673582.95      223092.689     1673331.818       223336.38
#Sta/Elev= 30
       0  1322.1    15.7 1311.09    59.3 1287.86      71 1285.47   152.8 1244.68
   176.2 1235.64   187.9 1233.99   270.7 1201.56   294.5 1196.95     399 1196.79
     424 1193.82   436.9 1188.01   446.9 1187.05   456.9 1188.39   486.4 1190.52
   497.8 1194.45   511.4 1203.22   523.9 1216.27   598.9 1264.92   614.8 1280.22
   629.4 1285.41   697.5 1326.57   711.6 1339.34   745.8 1359.21   760.4 1363.97
   796.3 1384.79   810.5 1397.36   900.5 1446.58   909.3 1454.59   950.7 1478.67
#Mann= 3 , 0 , 0
       0     .06       0   436.9    .045       0   456.9     .06       0
Bank Sta=436.9,456.9
XS Rating Curve= 0 ,0
Exp/Cntr=0.3,0.1

Type RM Length L Ch R = 1 ,33271.2 ,110.8,108.7,106.6
XS GIS Cut Line= 4
     1673971.313      222662.932     1673799.706      222869.419
     1673548.573      222962.896     1673308.602      223204.262
#Sta/Elev= 30
       0 1312.59     2.6 1312.59      66 1277.14    83.9 1263.06    97.1  1259.9
     177 1227.86   192.9 1218.71   202.5 1215.33     271 1194.98   356.9 1190.36
   412.4 1184.33   422.4 1184.16   432.4 1185.54   454.8 1190.28   508.9 1221.38
   519.7 1229.92   547.4  1240.2     576 1256.09   590.3 1260.12   602.5 1269.79
   614.8 1285.86   629.2 1295.41   701.1 1337.93   716.6 1350.53   731.6 1354.67
   801.7 1394.35   816.1 1407.86   847.6    1428   861.9 1432.14   876.8 1441.28
#Mann= 3 , 0 , 0
       0     .06       0   412.4    .045       0   432.4     .06       0
Bank Sta=412.4,432.4
XS Rating Curve= 0 ,0
Exp/Cntr=0.3,0.1

Type RM Length L Ch R = 1 ,33162.5 ,120.6,116.7,112.8
XS GIS Cut Line= 4
     1673925.234      222573.681     1673750.874        222759.2
      1673561.13      222848.491     1673249.967      223195.002
#Sta/Elev= 30
       0 1323.85    12.8 1317.91    23.9 1307.49    37.6 1299.91      58 1288.87
    71.9 1284.98   112.7 1262.17   127.5 1249.57   197.1 1213.75     211 1211.13
   238.8 1193.96   315.2 1185.18   383.6 1181.73   393.6 1181.08   403.6    1183
   460.9 1189.74   519.6 1224.49   550.6 1230.85   565.8 1236.59     581 1253.87
     606 1272.38   655.8 1302.74   669.4 1306.11   687.2 1320.36     792 1379.64
   852.7  1416.9   884.4 1436.98     901 1451.67   914.6 1455.45     930 1465.12
#Mann= 3 , 0 , 0
       0     .06       0   383.6    .045       0   403.6     .06       0
Bank Sta=383.6,403.6
XS Rating Curve= 0 ,0
Exp/Cntr=0.3,0.1