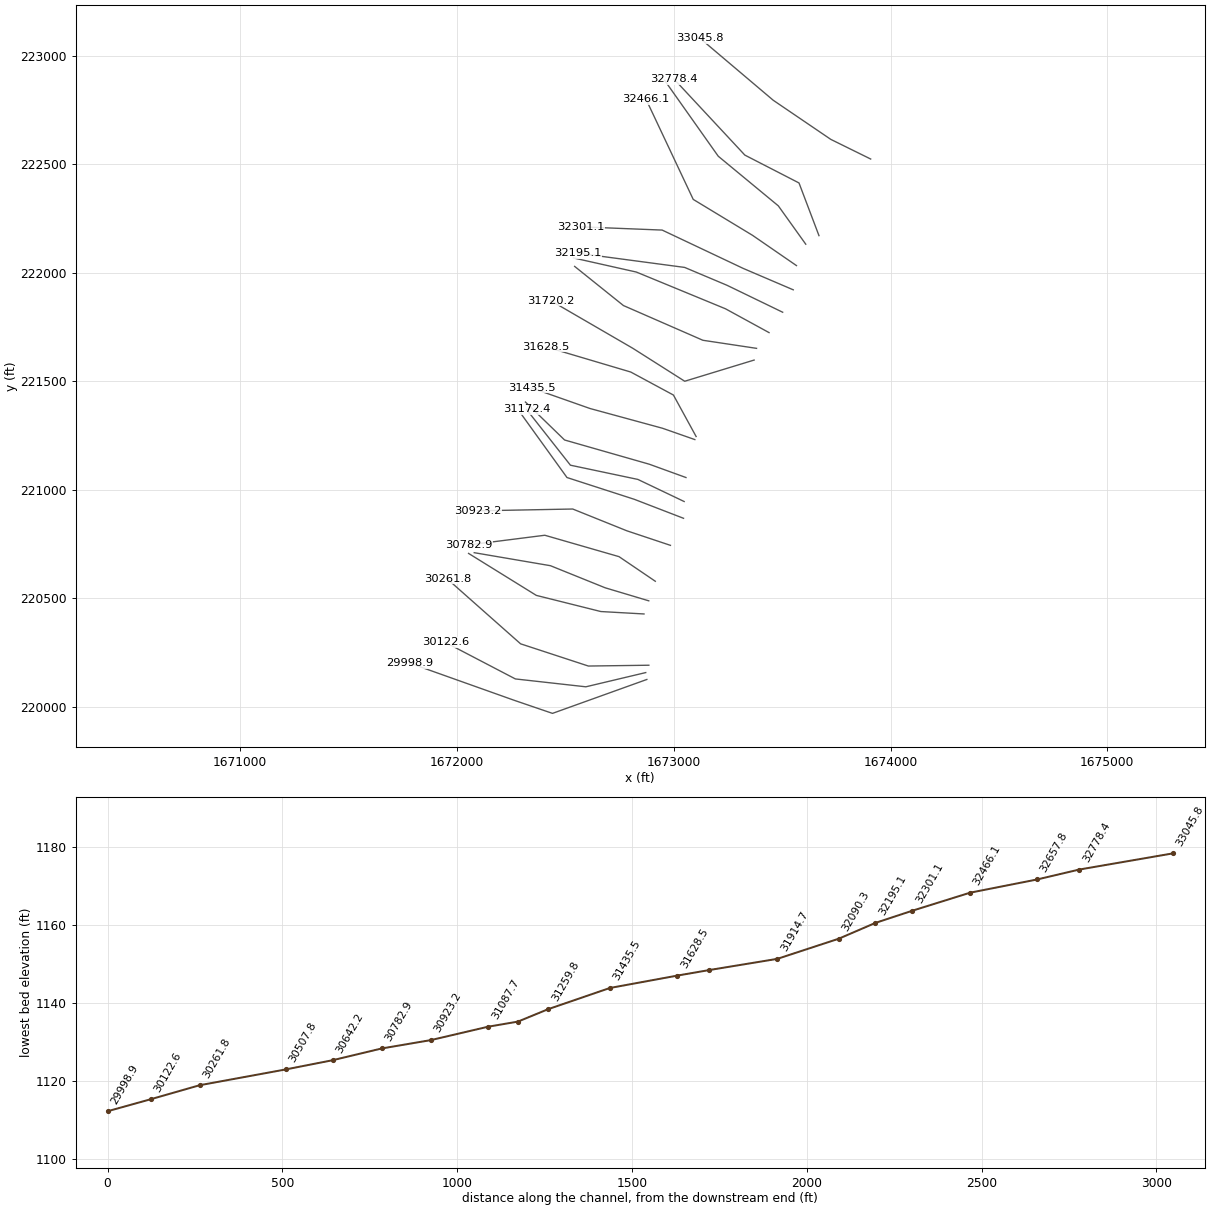
HEC-RAS study bchcrk.prj: bchcrk

--- bchcrk.g01 (geometry) --- (continued)

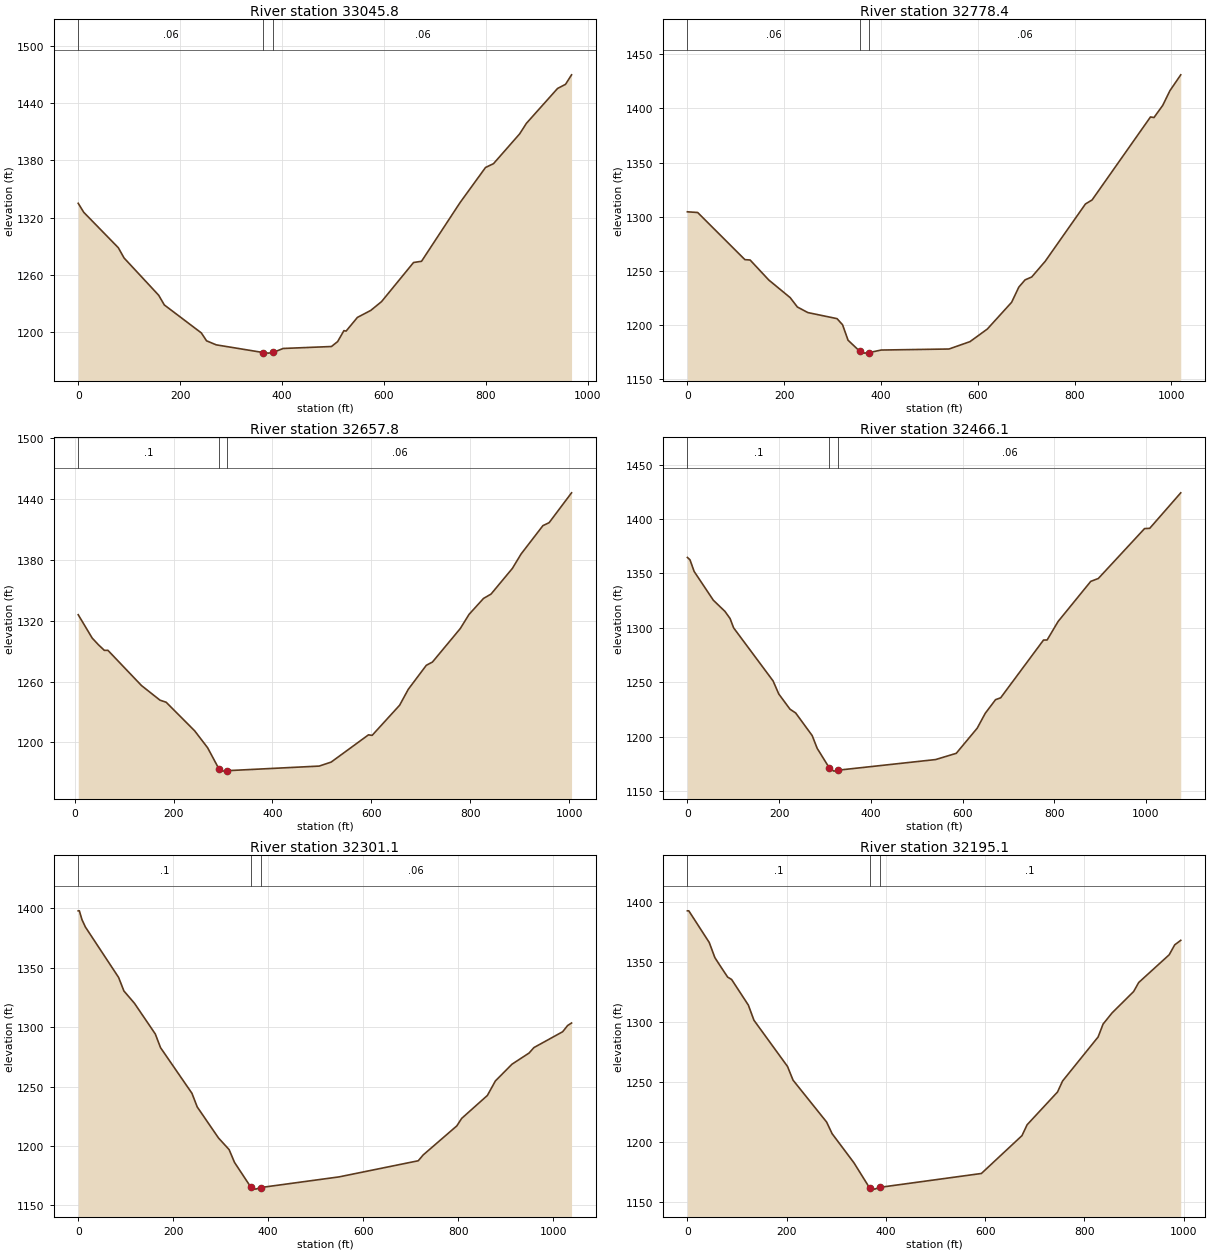
Type RM Length L Ch R = 1 ,33045.8 ,264.3,267.4,270.5
XS GIS Cut Line= 4
     1673908.492      222523.455     1673724.366      222614.101
     1673459.282      222794.079      1673121.61      223079.667
#Sta/Elev= 30
       0 1335.06    10.9 1325.62    78.7  1288.6      90 1277.85   157.8 1238.96
     169 1228.74   241.6 1199.49   251.8 1191.25   270.8 1187.03   362.9 1178.99
   372.9 1178.37   382.9 1179.18   402.1 1183.24   496.8 1185.28     509 1190.44
   521.3  1201.9   525.6 1201.43   547.7 1215.69     574 1223.04   595.1 1232.23
   657.9 1273.13   673.6 1274.42   749.1 1335.74   799.1 1372.49   814.8 1376.51
     866  1407.6   879.3 1418.66   940.4 1455.12   956.1 1459.48   967.9  1469.4
#Mann= 3 , 0 , 0
       0     .06       0   362.9    .045       0   382.9     .06       0
Bank Sta=362.9,382.9
XS Rating Curve= 0 ,0
Exp/Cntr=0.3,0.1

Type RM Length L Ch R = 1 ,32778.4 ,126,120.6,115.2
XS GIS Cut Line= 4
     1673669.954      222170.433     1673577.872      222413.195
     1673328.135      222541.551     1673001.662      222891.742
#Sta/Elev= 30
       0 1304.58    21.2 1303.94   118.8 1260.46   129.6 1260.11   168.1 1241.68
   212.3 1225.44   227.2 1216.77   248.8 1211.64   309.1 1206.04   320.5 1200.43
   331.9 1186.14   356.1 1175.95   366.1 1174.23   376.1 1174.78   400.3 1177.08
   540.4 1178.03   583.8 1184.83   619.6 1196.44   669.8 1221.11   684.7 1235.14
   697.6  1241.8   711.4 1244.49   739.2 1258.94   822.3 1311.79   836.1 1315.55
   956.7 1392.08   963.9 1391.55     982 1402.75   996.8 1416.28  1019.2 1430.93
#Mann= 3 , 0 , 0
       0     .06       0   356.1    .045       0   376.1     .06       0
Bank Sta=356.1,376.1
XS Rating Curve= 0 ,0
Exp/Cntr=0.3,0.1

Type RM Length L Ch R = 1 ,32657.8 ,188,191.7,195.3
XS GIS Cut Line= 4
     1673608.993      222130.944     1673482.497      222307.667
     1673205.321      222536.477     1672957.909      222886.202
#Sta/Elev= 30
     7.2 1325.82    35.5  1302.8      48 1296.27    60.1 1290.69    67.3 1290.72
   135.3 1255.97   172.7 1241.59   185.1 1239.57   242.8 1211.39     269  1194.7
  291.74    1174   295.3 1171.68   308.5 1172.12   494.6 1176.65   518.8 1180.57
   594.4 1207.45   601.7  1206.9   657.3 1236.61   674.8 1252.27   711.3 1275.96
   723.8 1279.21   780.1 1312.23   797.7  1326.1   827.1  1341.9   842.2 1346.14
   885.4 1371.45     903 1385.64   947.2 1413.61   959.7 1416.52  1005.1 1445.94
#Mann= 3 , 0 , 0
     7.2      .1       0  291.74    .045       0   308.5     .06       0
Bank Sta=291.74,308.5
XS Rating Curve= 0 ,0
Exp/Cntr=0.3,0.1

Type RM Length L Ch R = 1 ,32466.1 ,162.4,165,167.6
XS GIS Cut Line= 4
     1673566.208      222032.351     1673363.442      222171.869
     1673089.986      222337.431     1672872.338      222798.771
#Sta/Elev= 30
       0 1364.71     5.6 1362.57    14.7 1351.86    56.6 1325.37    81.9 1315.13
    93.1 1308.54   100.8 1299.99   186.9 1251.19   199.2 1239.23   223.8 1225.21
   236.1 1221.77   272.1 1200.99     283 1189.26   309.4 1171.32   319.4 1168.29
   329.4 1169.19   541.4 1178.93   586.3 1184.65     632 1207.76   649.6 1221.47
     672 1233.97   683.2 1235.71   776.6 1288.79   784.5 1288.84   808.3 1305.77
   879.6 1342.71   896.2 1345.39     997 1391.25  1008.2 1391.47  1075.9 1424.12
#Mann= 3 , 0 , 0
       0      .1       0   309.4    .045       0   329.4     .06       0
Bank Sta=309.4,329.4
XS Rating Curve= 0 ,0
Exp/Cntr=0.3,0.1

Type RM Length L Ch R = 1 ,32301.1 ,104.9,106,107.1
XS GIS Cut Line= 4
     1673551.326      221920.737     1673320.656      222019.329
     1672946.748      222196.052     1672572.839      222210.934
#Sta/Elev= 30
       0 1397.83     2.4 1397.83       8 1390.33    15.2 1384.17    85.1 1341.76
    96.2 1330.41   118.4 1320.05   162.3 1294.22   173.3 1282.72   239.5 1244.28
   250.5 1232.87   295.3 1206.73   317.7 1196.92     329  1186.2   363.8 1165.11
   373.8 1163.67   383.8 1164.98   549.2 1173.97   715.9 1187.54   726.1 1192.38
   797.1  1216.9   807.2 1223.15   861.4 1242.49   878.2 1254.67   913.2 1268.78
   949.2 1278.18   959.4 1282.77  1019.9  1296.1  1030.4 1301.35  1038.6 1303.44
#Mann= 3 , 0 , 0
       0      .1       0   363.8    .045       0   383.8     .06       0
Bank Sta=363.8,383.8
XS Rating Curve= 0 ,0
Exp/Cntr=0.3,0.1

Type RM Length L Ch R = 1 ,32195.1 ,104.4,104.7,105.1
XS GIS Cut Line= 4
     1673502.532      221817.452     1673245.819      221941.623
     1673050.494      222023.939     1672557.995      222089.513
#Sta/Elev= 30
       0 1392.59     2.8 1392.59      44 1366.21    55.3 1353.63    64.7 1347.59
    81.1 1337.32    89.1 1335.33   122.8 1313.99   134.1 1301.34   201.7 1262.83
   212.9 1251.37   280.5 1216.47   291.6 1206.74   335.6 1182.45   367.3 1161.41
   377.3 1160.53   387.3 1161.99   592.3 1173.57   674.1 1205.13   684.4 1214.17
   745.7 1241.52   755.9 1250.68   827.5 1287.41   837.5 1298.15   855.6 1307.45
   899.1 1325.31   909.3 1332.81   970.7 1355.94   981.9 1364.26     994 1367.97
#Mann= 3 , 0 , 0
       0      .1       0   367.3    .045       0   387.3      .1       0
Bank Sta=367.3,387.3
XS Rating Curve= 0 ,0
Exp/Cntr=0.3,0.1

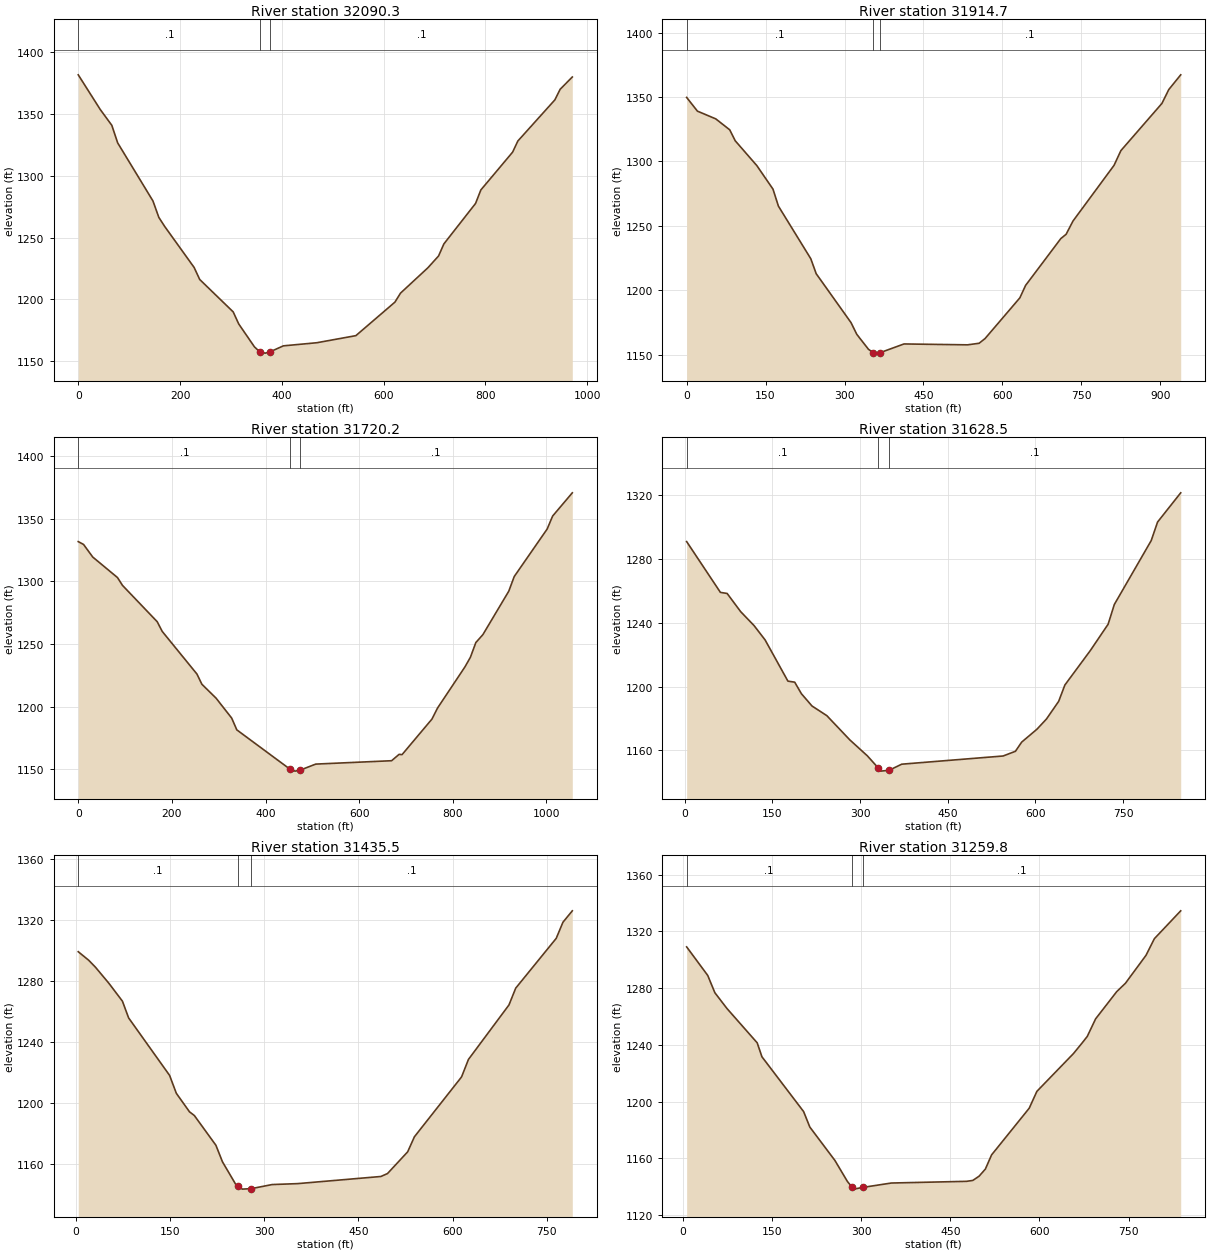
Type RM Length L Ch R = 1 ,32090.3 ,176.6,175.6,174.6
XS GIS Cut Line= 4
     1673439.711      221723.551     1673238.805      221833.305
     1672827.692      222002.587     1672537.495      222067.696
#Sta/Elev= 30
       0 1381.85    43.3 1353.74      66 1340.95    77.5 1326.73   146.8 1279.72
   158.4 1266.38   169.9 1259.05   227.7 1225.88   238.7 1216.12   304.5 1189.87
   315.4 1180.09   346.2  1161.6   357.8 1157.06   367.8 1156.48   377.8  1157.7
   403.1 1162.37   468.9  1164.9   545.6 1170.64   622.3 1197.77   633.3 1205.06
   687.3 1225.68   708.1 1235.16   718.5 1244.91   780.8 1277.71   791.2 1288.63
   853.6 1319.24   863.9 1328.25   936.7  1361.6     947 1370.15   970.9 1380.09
#Mann= 3 , 0 , 0
       0      .1       0   357.8    .045       0   377.8      .1       0
Bank Sta=357.8,377.8
XS Rating Curve= 0 ,0
Exp/Cntr=0.3,0.1

Type RM Length L Ch R = 1 ,31914.7 ,198,194.5,190.9
XS GIS Cut Line= 4
     1673382.044      221651.002     1673134.632      221688.206
     1672768.164      221848.187     1672543.075      222028.631
#Sta/Elev= 30
      .2 1349.69    20.7 1339.05    55.5 1333.06      82 1324.57    92.5 1316.05
   133.5  1296.8   164.2 1278.53   174.5 1265.35     236 1224.54   246.2 1212.96
   312.3 1175.02   323.3 1165.92   345.5 1154.28  354.85 1151.62   356.5 1151.31
   366.8 1151.54     413 1158.43   533.5 1157.74   555.6 1158.95     567 1162.64
     633 1194.19   643.9 1203.84   710.8 1240.17   720.9 1243.53   733.9 1253.78
   811.9 1297.01   824.9 1308.43   902.8 1345.03   915.8 1355.76   938.5 1367.23
#Mann= 3 , 0 , 0
      .2      .1       0  354.85    .045       0   366.8      .1       0
Bank Sta=354.85,366.8
XS Rating Curve= 0 ,0
Exp/Cntr=0.3,0.1

Type RM Length L Ch R = 1 ,31720.2 ,90.6,91.8,93.2
XS GIS Cut Line= 4
     1673370.883      221597.055     1673050.808      221499.427
     1672810.663      221651.675     1672433.321       221870.51
#Sta/Elev= 30
       0 1331.69    11.3 1329.43      31 1319.36    83.9 1302.96    94.5 1296.74
   168.7 1267.72   179.3 1260.03   253.5 1225.96   264.1 1217.79   294.4 1206.69
   327.7 1190.79   338.7 1181.37   453.2 1149.74   463.2 1148.44   473.2 1149.13
   507.2 1154.05   669.3 1156.75   685.2 1161.82   691.6 1161.62   755.5 1190.02
   767.2  1198.7   825.8 1231.61   837.5 1239.29   849.2  1251.1   864.2 1257.41
   919.5  1292.1   931.2 1303.83  1001.5 1341.74  1013.2 1352.11  1055.2 1370.64
#Mann= 3 , 0 , 0
       0      .1       0   453.2    .045       0   473.2      .1       0
Bank Sta=453.2,473.2
XS Rating Curve= 0 ,0
Exp/Cntr=0.3,0.1

Type RM Length L Ch R = 1 ,31628.5 ,186.5,192.9,199
XS GIS Cut Line= 4
     1673103.336       221244.66     1672998.697        221435.8
     1672801.977      221541.833     1672411.326      221657.634
#Sta/Elev= 30
     3.4 1290.83    61.2 1258.99    72.7 1258.33    95.8 1246.95   118.9 1238.14
   137.7 1229.18   176.7 1203.39   188.3 1202.75   199.8  1195.5   217.9 1187.82
   243.3 1181.76   282.5 1166.63   312.7 1156.56  330.81 1149.18   335.4 1147.01
   349.9 1147.54   371.4 1151.36   544.9 1156.49     566 1159.44   576.6 1165.16
   602.6  1173.2     619 1179.62     640 1190.75   650.6 1200.97   694.1 1222.53
   724.6 1239.06   735.2 1251.42   798.3 1291.44   809.2 1303.07   848.8 1321.38
#Mann= 3 , 0 , 0
     3.4      .1       0  330.81    .045       0   349.9      .1       0
Bank Sta=330.81,349.9
XS Rating Curve= 0 ,0
Exp/Cntr=0.3,0.1

Type RM Length L Ch R = 1 ,31435.5 ,176,175.7,175.4
XS GIS Cut Line= 4
     1673097.427      221230.587     1672948.608      221282.674
     1672613.764      221373.826      1672344.03      221468.698
#Sta/Elev= 30
     4.3 1299.08    20.9 1293.51    31.6 1288.99    53.1 1278.42    74.6 1266.75
    84.5 1255.78   149.7 1218.19   160.4 1206.49   181.4 1194.37   189.1 1191.95
   223.4 1172.51   233.9 1161.64   254.9 1146.97  258.12 1145.97   265.4 1143.83
   279.9 1144.16   312.9 1146.82   353.6 1147.43     486  1152.1   496.5 1154.02
   528.6 1168.23   539.3 1178.05   613.2  1216.6   614.5 1217.36   625.3 1228.63
   689.8 1264.26   700.5 1275.23     765 1307.81   775.7 1318.35   790.6 1325.81
#Mann= 3 , 0 , 0
     4.3      .1       0  258.12    .045       0   279.9      .1       0
Bank Sta=258.12,279.9
XS Rating Curve= 0 ,0
Exp/Cntr=0.3,0.1

Type RM Length L Ch R = 1 ,31259.8 ,85.7,87.4,89.2
XS GIS Cut Line= 4
     1673056.502      221055.725      1672887.22      221117.112
     1672496.569      221228.727     1672316.126       221403.59
#Sta/Elev= 30
     6.6 1309.05    42.1 1288.92    54.1 1276.73    74.4 1265.65   125.3 1241.44
   133.2 1231.66   203.3 1193.07   213.8 1182.14     256 1158.61   277.1 1143.76
  283.96 1140.21   287.6 1138.42   302.9 1139.63   350.9 1142.72   477.4 1143.91
   487.9 1144.54   498.4  1147.5     509 1152.52   519.5 1162.53   582.8 1195.42
   595.7 1207.29   657.2  1233.9   671.8 1241.37   680.4 1245.96   694.5 1258.37
     730 1277.54   744.6 1283.41   779.2 1303.08   793.3 1314.82   837.6 1334.44
#Mann= 3 , 0 , 0
     6.6      .1       0  283.96    .045       0   302.9      .1       0
Bank Sta=283.96,302.9
XS Rating Curve= 0 ,0
Exp/Cntr=0.3,0.1

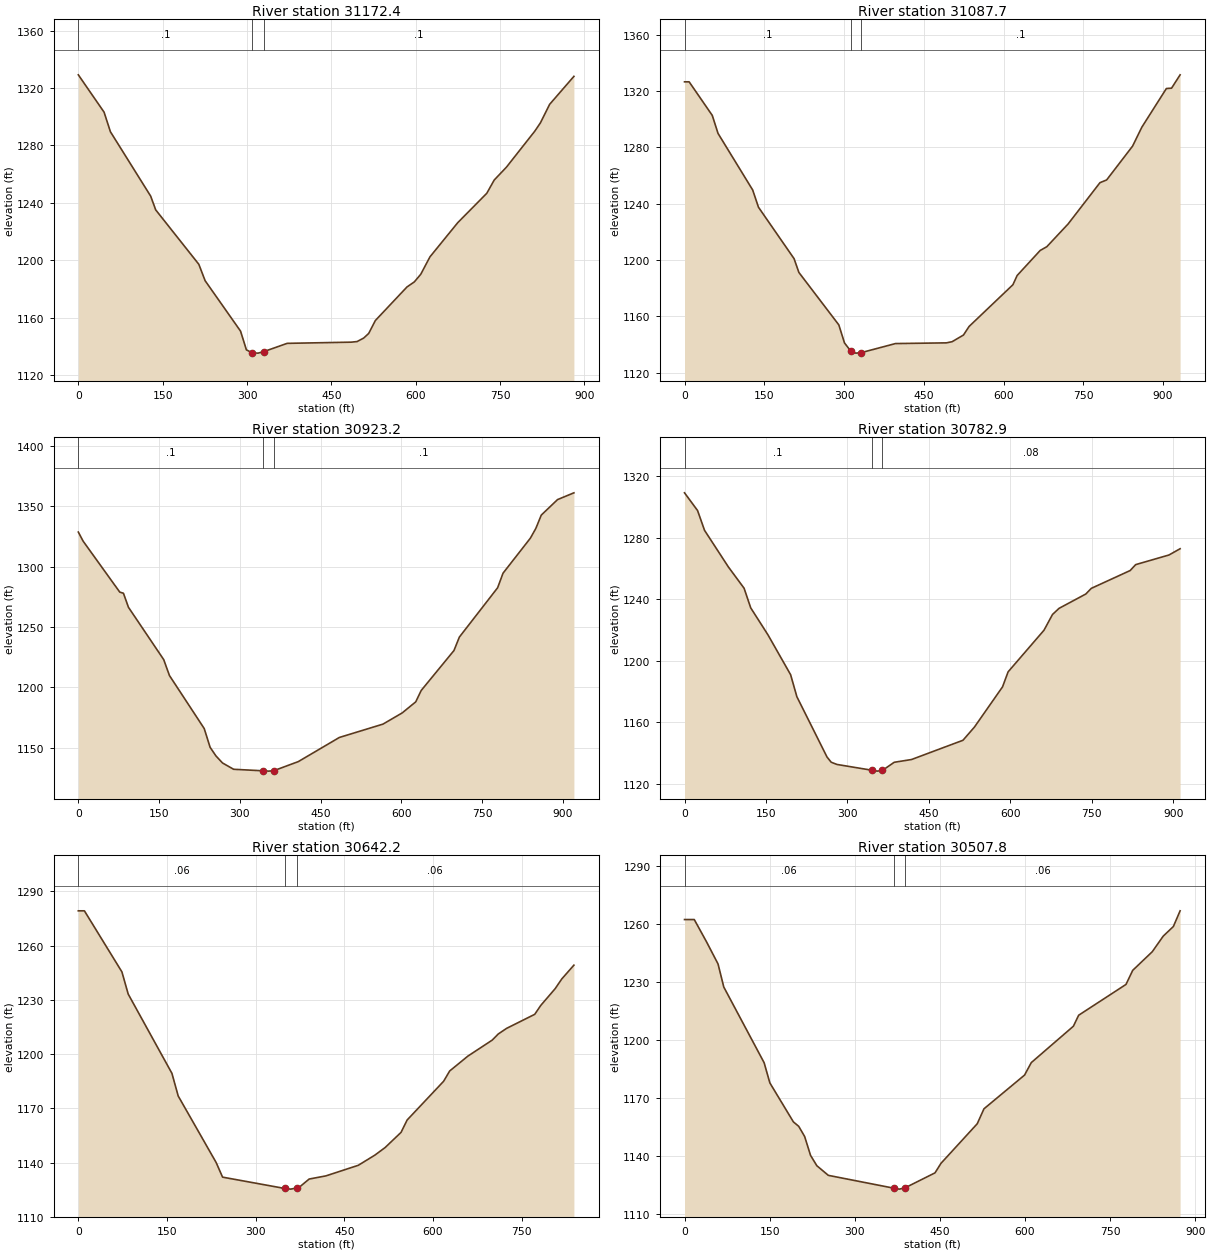
Type RM Length L Ch R = 1 ,31172.4 ,87.5,84.8,82.1
XS GIS Cut Line= 4
     1673048.155      220945.133     1672834.693      221046.981
     1672523.567      221112.554     1672321.266      221369.268
#Sta/Elev= 30
       0 1329.14    45.8 1303.12    57.1 1289.45   128.7 1244.59   137.6 1235.04
   214.3  1197.1   225.5 1185.67   288.5 1150.53   298.9 1137.49   309.6  1135.3
   319.6  1135.2   329.6 1136.21   371.4 1142.01   485.3 1142.84   495.7 1143.26
   507.5  1145.7   516.4 1148.92   528.2 1157.91   584.5 1181.32   597.4  1184.8
   608.9 1190.11   625.3 1202.28   674.8 1226.14   726.4  1246.6   739.6 1255.83
   761.2 1264.74   811.8 1289.91   821.8  1295.7   838.2  1308.6   881.3 1328.07
#Mann= 3 , 0 , 0
       0      .1       0   309.6    .045       0   329.6      .1       0
Bank Sta=309.6,329.6
XS Rating Curve= 0 ,0
Exp/Cntr=0.3,0.1

Type RM Length L Ch R = 1 ,31087.7 ,166,164.4,162.8
XS GIS Cut Line= 4
      1673045.34       220867.84     1672818.391      220955.271
     1672507.731      221055.725     1672295.663      221349.643
#Sta/Elev= 30
       0  1326.6     8.7  1326.6    52.2 1302.75      63 1289.97   128.2 1249.77
   139.1 1237.53     206 1201.03   215.1 1191.21   290.2 1153.97   300.9 1141.12
   312.2  1135.6   322.2  1133.9   332.2 1134.23   396.7 1140.69   492.6 1141.19
   503.3 1142.02   524.6 1146.73   535.2 1152.84   617.6 1182.46   625.6 1189.04
   668.9 1206.81   681.4 1209.48   721.5 1225.66   781.4 1254.98   793.9  1256.9
   842.7 1280.92   860.1 1294.36   906.3 1321.86     916 1322.08   932.1 1331.57
#Mann= 3 , 0 , 0
       0      .1       0   312.2    .045       0   332.2      .1       0
Bank Sta=312.2,332.2
XS Rating Curve= 0 ,0
Exp/Cntr=0.3,0.1

Type RM Length L Ch R = 1 ,30923.2 ,137.9,140.3,142.8
XS GIS Cut Line= 4
      1672984.92      220743.163     1672784.014      220810.132
     1672534.277      220910.585     1672094.795      220902.214
#Sta/Elev= 30
       0 1328.65       9 1321.08      77 1278.87    83.8 1277.94    93.1 1266.31
   158.6 1222.91   169.3 1209.69   233.8  1165.8   244.8 1150.19   255.7 1143.02
   267.8 1137.22   288.5 1131.98   343.5  1130.7   353.5 1130.45   363.5 1130.88
   408.6 1138.34   484.8 1158.35   565.9 1169.43   601.6 1178.72   626.7 1187.88
   636.9 1197.34   697.7 1230.42   707.8 1241.61   778.8 1282.47   788.9 1294.58
   839.6 1323.57   849.8 1331.69   859.9 1342.72   890.1 1355.57   920.5 1361.19
#Mann= 3 , 0 , 0
       0      .1       0   343.5    .045       0   363.5      .1       0
Bank Sta=343.5,363.5
XS Rating Curve= 0 ,0
Exp/Cntr=0.3,0.1

Type RM Length L Ch R = 1 ,30782.9 ,143.2,140.7,138.1
XS GIS Cut Line= 4
     1672915.123      220577.643     1672747.702      220691.117
     1672405.417       220789.71     1672053.832      220745.064
#Sta/Elev= 30
       0 1309.08      24 1297.59    36.9  1284.7    80.7 1260.98   109.7 1247.11
   121.9 1234.37   153.7 1216.82   195.4 1190.94   206.9 1176.66   262.4 1137.49
   270.2 1134.08   280.7 1132.65   344.5 1128.92   354.5 1128.31   364.5 1128.78
   386.2 1134.06     418 1135.84   512.8 1148.35   533.9 1156.91   585.7 1183.06
   595.9 1192.78     662 1219.82   677.7 1230.07   689.8 1234.05     739 1243.35
   749.2 1247.04   820.7  1258.6   830.9 1262.45   892.2  1268.7   912.7 1272.77
#Mann= 3 , 0 , 0
       0      .1       0   344.5    .045       0   364.5     .08       0
Bank Sta=344.5,364.5
XS Rating Curve= 0 ,0
Exp/Cntr=0.3,0.1

Type RM Length L Ch R = 1 ,30642.2 ,130.9,134.4,137.9
XS GIS Cut Line= 4
     1672884.919      220487.513     1672684.013      220547.506
     1672431.486      220649.354       1672079.9      220709.347
#Sta/Elev= 30
       0  1279.3    10.3  1279.3    73.8 1245.49    84.4 1233.24   158.4 1189.36
     169 1176.84   233.2 1140.03   244.1 1131.92   349.4 1125.65   359.4 1125.29
   369.4 1125.94   375.3 1126.72   390.6 1130.87     419 1132.62   473.7 1138.47
   501.9 1144.12   519.4 1148.37   546.1  1156.7   556.4 1163.54   618.1 1184.96
   628.4 1190.67   659.2  1198.9   700.4 1207.76   710.6 1211.14   724.7 1214.25
   772.3 1222.02   782.6 1226.98   806.9 1236.23   818.1 1241.62   838.6 1249.23
#Mann= 3 , 0 , 0
       0     .06       0   349.4    .045       0   369.4     .06       0
Bank Sta=349.4,369.4
XS Rating Curve= 0 ,0
Exp/Cntr=0.3,0.1

Type RM Length L Ch R = 1 ,30507.8 ,247.7,246,244.3
XS GIS Cut Line= 4
     1672863.037      220426.963     1672663.991      220438.124
     1672366.352      220512.534     1672053.832      220705.999
#Sta/Elev= 30
       0 1262.13    17.2 1262.13    38.8 1250.62    59.1 1239.19    69.2 1227.29
   140.3  1188.2   150.4 1177.79   191.9 1157.64   201.2 1155.38   211.7 1150.12
   222.1 1140.37   233.2 1135.01   253.5 1130.03   368.8 1123.41   378.8 1122.92
   388.8  1123.6   441.5 1131.32     452 1136.23   515.9 1156.67   527.8  1164.4
   599.3 1181.81   611.2 1188.26   685.4 1207.04   694.7 1212.72   778.1 1228.63
     790 1235.91   824.4 1245.51   843.7 1253.56   861.6 1258.53   873.5 1266.64
#Mann= 3 , 0 , 0
       0     .06       0   368.8    .045       0   388.8     .06       0
Bank Sta=368.8,388.8
XS Rating Curve= 0 ,0
Exp/Cntr=0.3,0.1

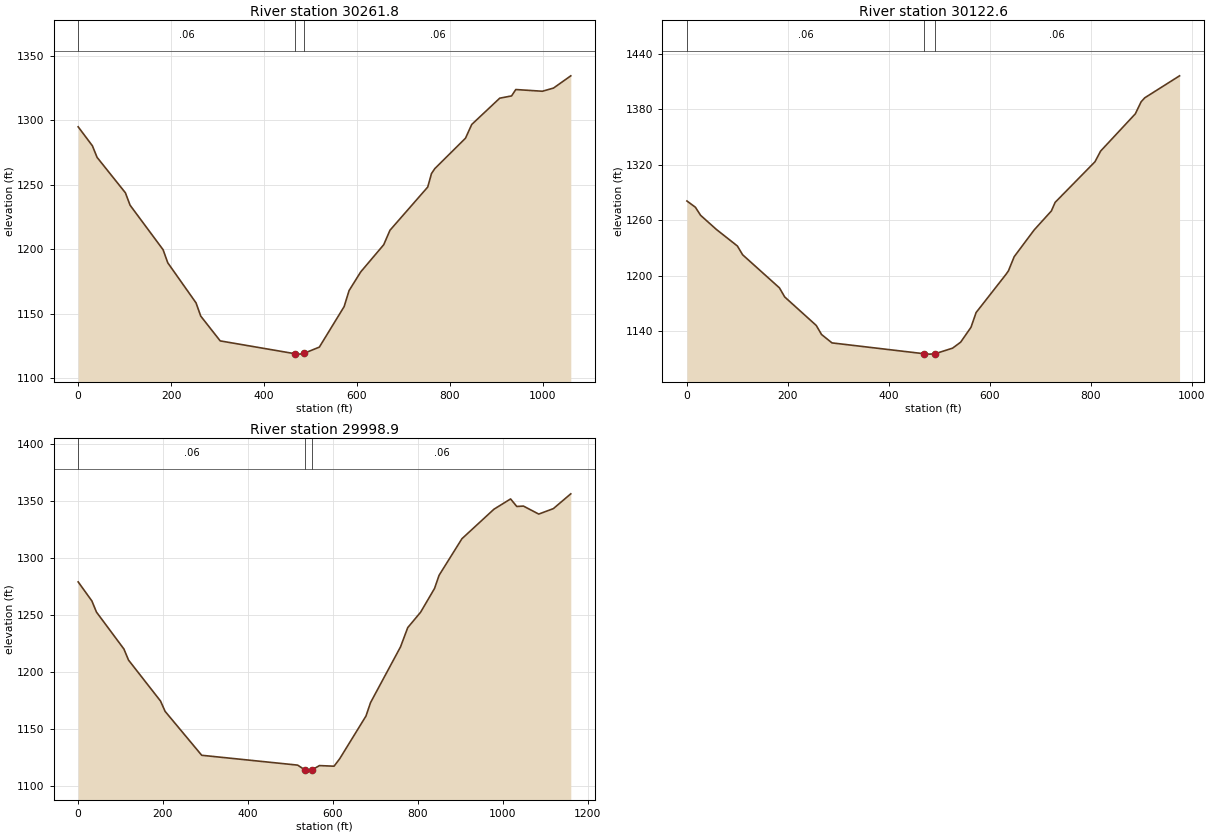
Type RM Length L Ch R = 1 ,30261.8 ,134.2,139.3,144.3
XS GIS Cut Line= 4
      1672885.36      220190.712     1672606.324      220186.992
     1672293.803      220289.305     1671955.239      220588.804
#Sta/Elev= 30
       0 1295.07    30.6 1280.36    40.7 1271.38   101.6 1243.93   111.7  1234.3
   182.7 1199.81   192.8 1189.65   253.6  1158.6   263.7 1148.36   305.6 1129.13
   466.3 1119.19   476.3 1118.87   486.3 1119.54   518.9 1124.31   572.2 1155.69
   582.9 1168.14   607.9 1182.59   657.4 1203.67   670.9  1214.9   752.1 1248.38
   760.2 1258.85   767.4 1262.69   833.3 1286.22   846.8 1296.89     907 1317.26
   932.5 1319.01   941.6 1323.97   998.8 1322.64  1022.7 1325.09  1059.9 1334.59
#Mann= 3 , 0 , 0
       0     .06       0   466.3    .045       0   486.3     .06       0
Bank Sta=466.3,486.3
XS Rating Curve= 0 ,0
Exp/Cntr=0.3,0.1

Type RM Length L Ch R = 1 ,30122.6 ,129.1,123.7,118.2
XS GIS Cut Line= 4
     1672870.968      220156.856     1672594.722      220091.282
     1672269.645      220127.557     1671945.963      220296.374
#Sta/Elev= 30
       0 1280.73    16.7 1274.02    27.1 1265.25    58.3 1250.03     100 1232.09
   110.4 1222.61   183.3 1186.88   193.8 1177.03   256.3 1146.24   266.7  1136.5
   287.4 1127.43   470.6 1115.66   480.6 1115.29   490.6 1115.52   526.4 1121.75
   542.4 1128.24   562.8 1144.24     573 1160.23   631.9 1201.27     637 1205.21
   648.4 1220.53   687.9 1249.38   722.1 1269.97   729.6 1279.27   808.5  1323.1
   819.7 1334.66   888.5 1374.93   899.9 1387.86   907.1 1392.19   976.1 1415.96
#Mann= 3 , 0 , 0
       0     .06       0   470.6    .045       0   490.6     .06       0
Bank Sta=470.6,490.6
XS Rating Curve= 0 ,0
Exp/Cntr=0.3,0.1

Type RM Length L Ch R = 1 ,29998.9 ,51.9,47.2,42.5
XS GIS Cut Line= 4
     1672876.096      220125.098       1672440.8      219968.838
     1672265.007      220028.831     1671782.274      220200.438
#Sta/Elev= 30
     1.1 1279.13    33.4 1262.39    44.2 1252.62   108.8 1220.21   119.6 1210.53
     195 1174.55   205.7 1165.54   291.9 1126.98   517.7 1118.35  535.15 1114.07
   539.1  1112.2  551.45 1114.15   568.9 1117.94   603.4  1117.4   616.8 1124.02
   678.5  1161.4   689.3 1173.23   759.8 1222.08   776.8 1238.99   807.1 1252.52
   839.9 1273.38   850.6 1284.92   904.4 1317.02   979.7  1342.9  1018.9 1351.92
  1033.5 1345.31  1049.2 1345.65  1085.2 1338.64  1119.5 1343.41  1160.6 1356.41
#Mann= 3 , 0 , 0
     1.1     .06       0  535.15    .045       0  551.45     .06       0
Bank Sta=535.15,551.45
XS Rating Curve= 0 ,0
Exp/Cntr=0.3,0.1