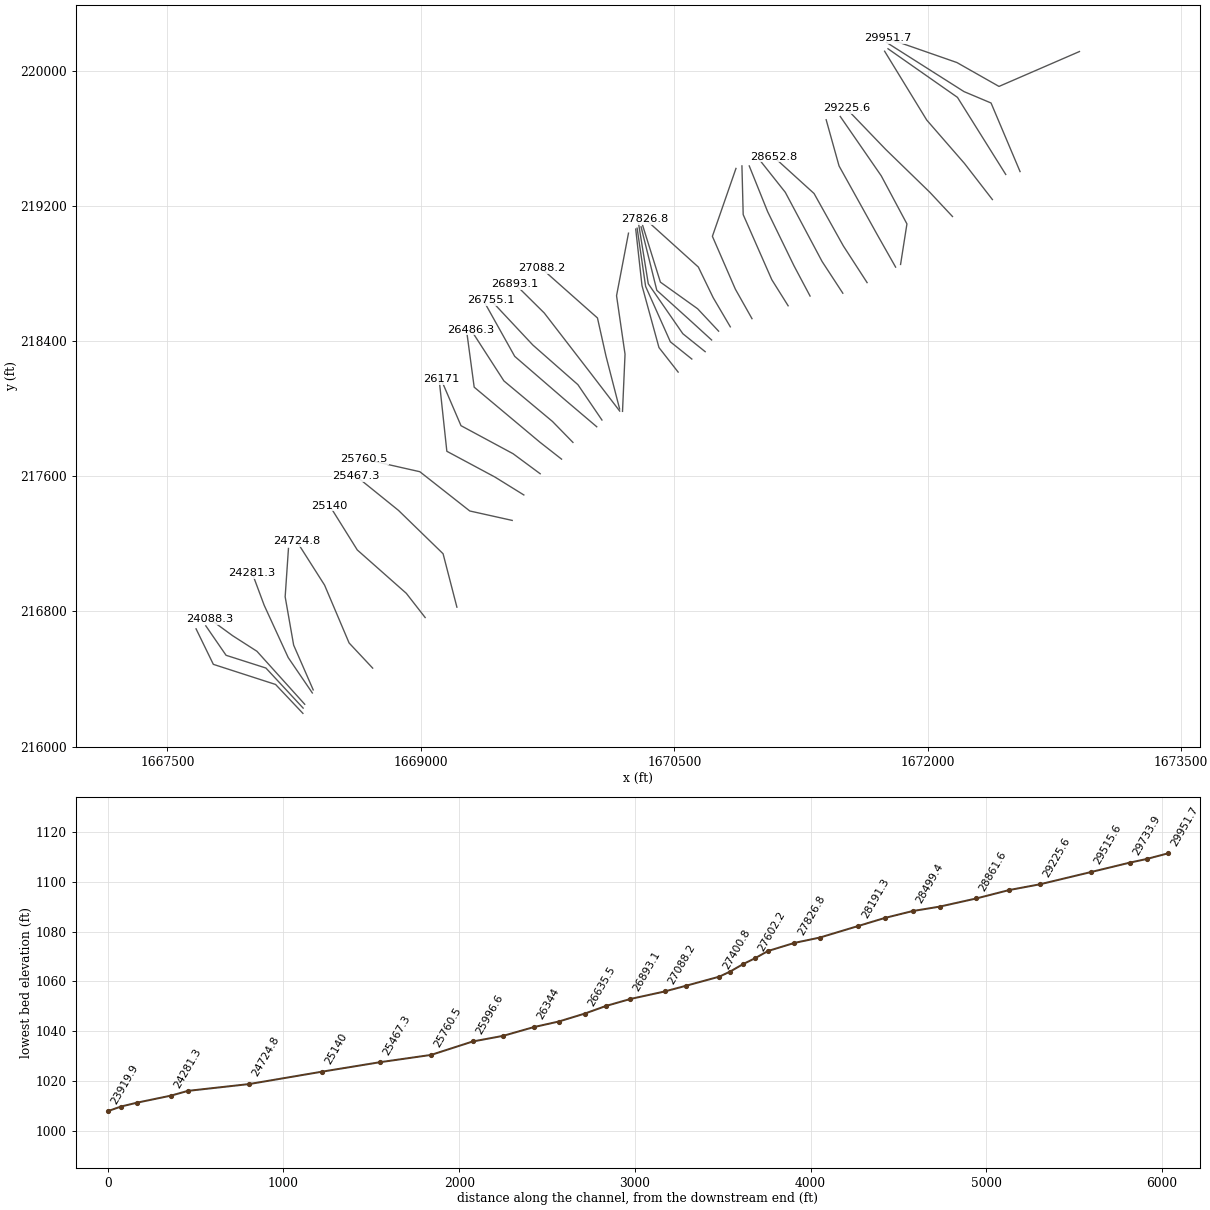
HEC-RAS study bchcrk.prj: bchcrk

--- bchcrk.g01 (geometry) --- (continued)

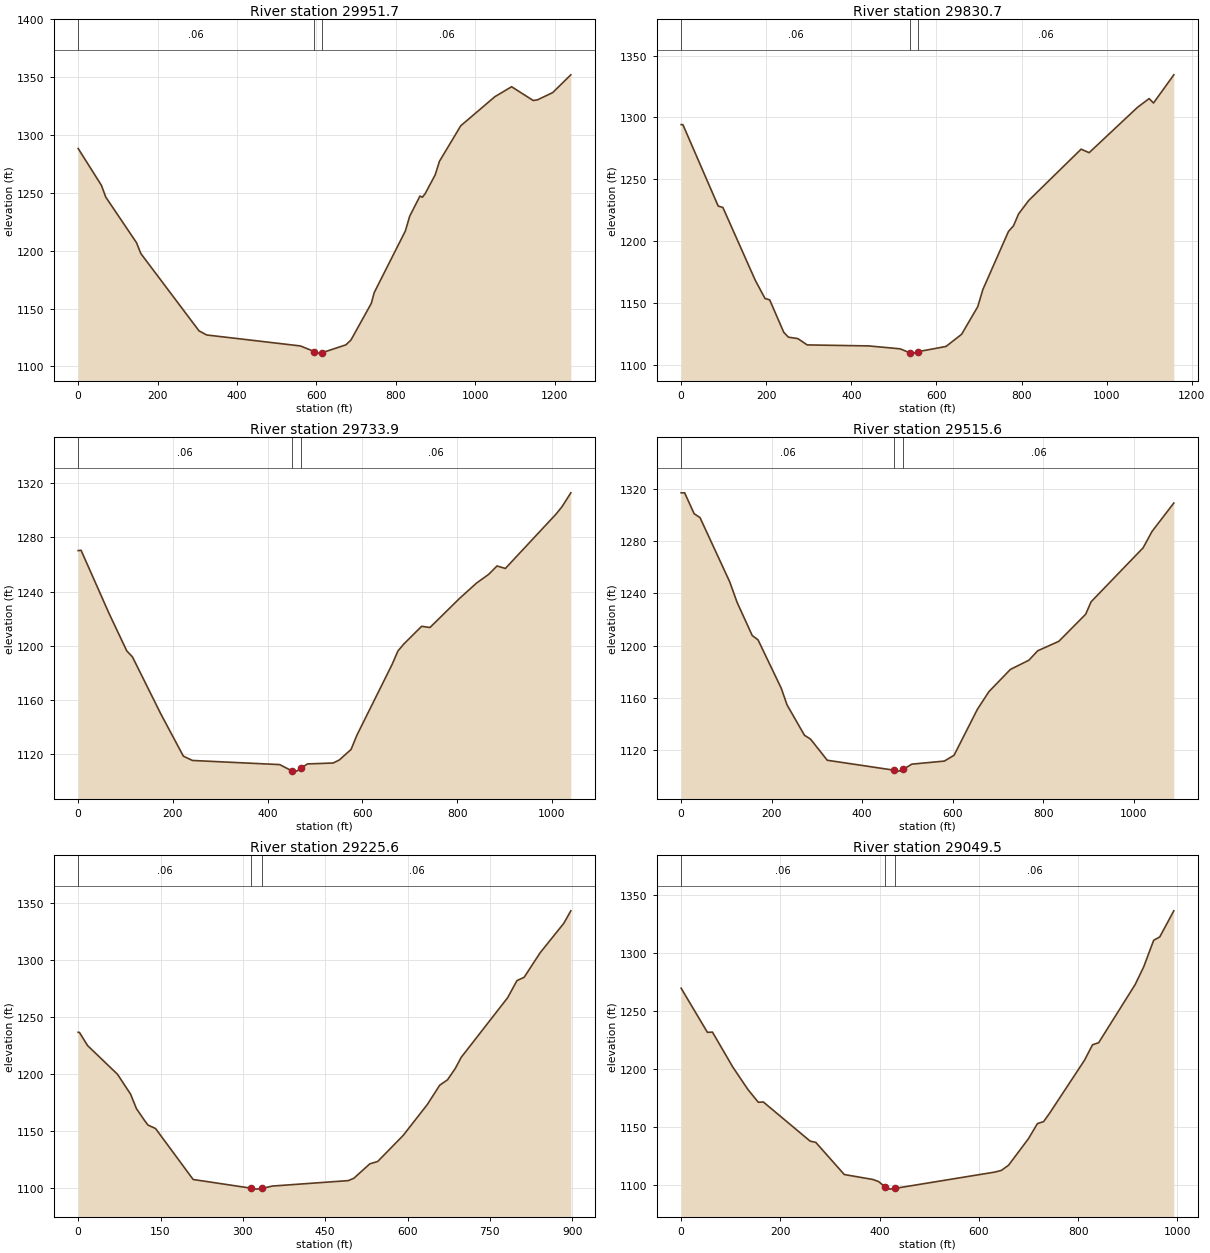
Type RM Length L Ch R = 1 ,29951.7 ,118,121,124
XS GIS Cut Line= 4
     1672898.381      220114.442      1672422.16      219907.956
     1672172.887      220049.334     1671761.774      220192.572
#Sta/Elev= 30
       0 1288.39    58.6 1256.53    69.6 1246.33     147 1206.94   157.9 1197.56
   304.4 1130.74   323.7 1127.17   559.9 1117.68   594.8 1112.85   604.4 1111.47
   614.8 1111.87   674.3 1118.62     687 1122.72   738.4 1154.51   745.8 1163.86
   824.2 1217.11   834.9 1229.65   846.8 1237.77     861 1247.28   867.1 1246.28
   874.2 1249.43   899.3 1265.61     910 1277.29   963.7 1308.05  1049.6 1333.18
  1091.8 1341.81  1146.2 1329.92  1156.9 1330.46  1195.3 1336.74    1241  1352.1
#Mann= 3 , 0 , 0
       0     .06       0   594.8    .045       0   614.8     .06       0
Bank Sta=594.8,614.8
XS Rating Curve= 0 ,0
Exp/Cntr=0.3,0.1

Type RM Length L Ch R = 1 ,29830.7 ,112.4,96.8,81.2
XS GIS Cut Line= 4
     1672546.796       219403.83     1672375.105      219809.775
     1672215.008      219877.267     1671756.193      220168.389
#Sta/Elev= 30
       0  1294.2     4.1  1294.2    87.1 1228.27    98.1 1227.12   174.2 1168.19
   197.1 1153.44   208.1 1152.33   241.2 1126.06   252.2 1122.11   274.2 1120.99
   296.2 1115.86   440.8 1115.05   514.6 1112.69   537.2 1109.54   547.2 1109.21
   557.2 1110.41   622.5 1114.61   659.2 1124.47   697.1 1146.81   709.1 1160.68
   769.3 1207.71   781.1 1212.27   793.1 1221.93   817.1 1232.88     940 1274.33
   958.9 1271.49  1072.4 1308.15  1099.8 1315.27  1110.2  1311.7  1157.9 1334.52
#Mann= 3 , 0 , 0
       0     .06       0   537.2    .045       0   557.2     .06       0
Bank Sta=537.2,557.2
XS Rating Curve= 0 ,0
Exp/Cntr=0.3,0.1

Type RM Length L Ch R = 1 ,29733.9 ,214.3,218.3,222.4
XS GIS Cut Line= 4
     1672461.955      219386.905     1672251.631      219722.795
     1672176.292      219843.129     1671765.062      220130.885
#Sta/Elev= 30
       0  1270.1     6.1 1270.38    64.9  1224.1   102.6 1196.28   114.6 1191.85
   174.4 1149.93   222.2 1118.72   241.4 1115.58   425.5 1112.54   451.4 1107.87
   461.4 1107.73   471.4 1110.05   484.1 1113.03   538.3  1113.7   551.4 1115.94
   576.2  1123.7   588.5 1134.19   662.8 1186.27   675.1 1196.17   687.5 1201.31
   725.2 1214.38   742.8 1213.49   804.9 1234.81   841.3 1246.27   866.6 1252.58
   884.3 1258.81     902 1256.98  1008.7  1296.9  1021.5 1302.41  1040.2 1312.67
#Mann= 3 , 0 , 0
       0     .06       0   451.4    .045       0   471.4     .06       0
Bank Sta=451.4,471.4
XS Rating Curve= 0 ,0
Exp/Cntr=0.3,0.1

Type RM Length L Ch R = 1 ,29515.6 ,287.7,290,292.4
XS GIS Cut Line= 4
     1672383.094      219238.269     1672217.533      219452.197
     1671994.304       219708.91     1671745.032      220116.303
#Sta/Elev= 30
       0 1317.06     7.7 1317.06    28.8 1301.03    41.6 1298.14   107.1 1249.08
   123.6 1233.21     157 1207.83   169.8 1204.52   221.1 1167.48   233.9 1154.72
   272.4 1131.46   285.8 1128.51   322.8 1112.32   470.8 1104.68   480.8 1103.99
   490.8 1105.36   509.5 1109.34   581.4 1111.68   602.9 1116.15   654.3 1151.26
   679.8 1164.81   727.3 1181.85   768.1 1188.89   787.6 1196.11   834.3 1203.38
   893.7 1224.15   905.6 1233.65  1020.6 1274.99    1040 1287.41  1088.3 1309.24
#Mann= 3 , 0 , 0
       0     .06       0   470.8    .045       0   490.8     .06       0
Bank Sta=470.8,490.8
XS Rating Curve= 0 ,0
Exp/Cntr=0.3,0.1

Type RM Length L Ch R = 1 ,29225.6 ,183.9,176.1,168.4
XS GIS Cut Line= 4
     1672146.844      219137.816     1672012.907      219281.054
     1671752.473      219534.047     1671518.082      219777.739
#Sta/Elev= 30
       0 1236.76     2.2 1236.76    17.2 1225.09    71.6 1199.96    95.5 1182.44
   106.2 1169.69     121 1159.31   127.1 1155.35     141 1152.27   209.4 1107.54
   314.9  1099.9   324.9 1099.07   334.9 1099.67   353.6 1101.76     492 1106.55
     502 1108.57   531.1 1121.25   545.6 1123.38     592 1146.25   635.9 1173.36
   658.6 1190.38   672.6 1195.01   686.7  1204.9   697.6 1214.77   782.1 1267.08
   799.2 1282.19   812.3 1285.09   841.4 1306.63   884.5  1332.5   897.3 1343.45
#Mann= 3 , 0 , 0
       0     .06       0   314.9    .045       0   334.9     .06       0
Bank Sta=314.9,334.9
XS Rating Curve= 0 ,0
Exp/Cntr=0.3,0.1

Type RM Length L Ch R = 1 ,29049.5 ,187.4,187.9,188.3
XS GIS Cut Line= 4
     1671839.477      218854.088     1671877.147      219094.059
     1671725.072      219378.676      1671482.31      219730.262
#Sta/Elev= 30
       0 1269.47    52.9 1231.55    63.1 1231.73   104.2 1201.63   134.9 1182.22
   155.5 1171.43   165.7 1171.64   259.9 1138.04   271.4 1136.91   328.8 1109.29
   386.3 1105.05   397.8 1103.28   410.8  1098.7   420.8 1096.74   430.8 1097.37
   632.1 1111.39   645.3 1112.82   659.9  1117.3   700.2 1140.27     718 1153.05
   730.6 1154.81   742.9 1162.21   812.9 1207.54   829.1 1220.85   841.4 1222.61
   914.9 1272.55   932.1 1287.72   952.3 1310.66   964.6 1313.59   992.9 1336.01
#Mann= 3 , 0 , 0
       0     .06       0   410.8    .045       0   430.8     .06       0
Bank Sta=410.8,430.8
XS Rating Curve= 0 ,0
Exp/Cntr=0.3,0.1

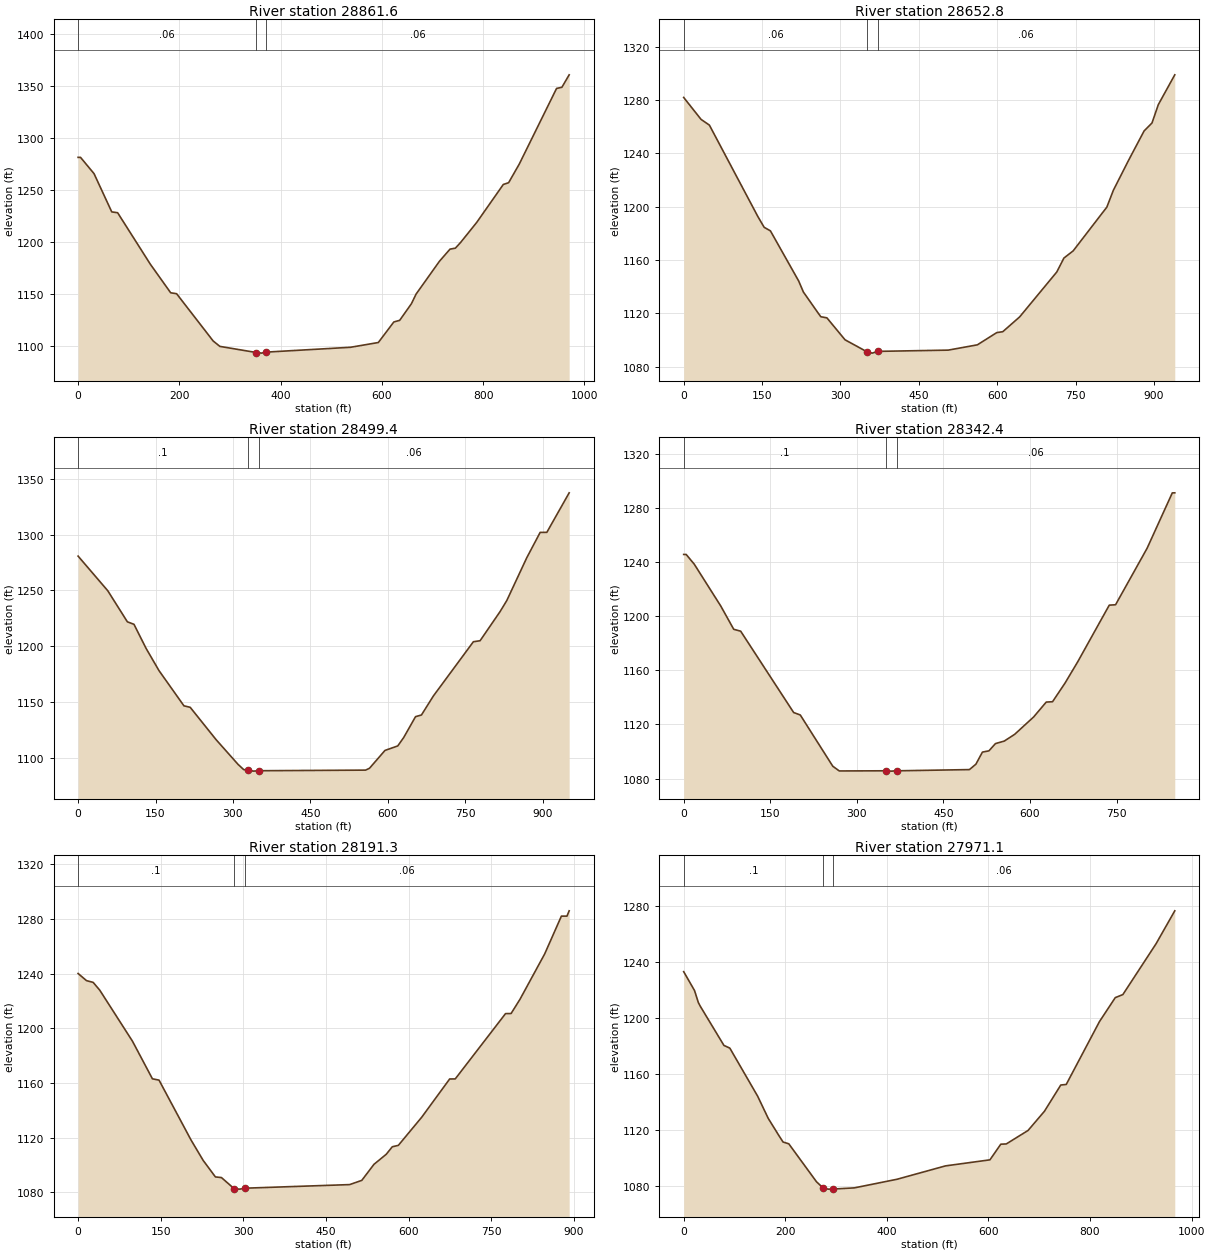
Type RM Length L Ch R = 1 ,28861.6 ,208.8,208.9,208.9
XS GIS Cut Line= 4
      1671810.14      218838.317     1671698.526      219035.503
     1671475.297      219437.315     1671399.027       219710.77
#Sta/Elev= 30
       0 1281.63     4.8 1281.63    31.5 1265.97    66.5 1229.18    78.1 1228.39
   142.7 1178.87   182.9 1151.39   194.6 1150.48   266.8 1105.05   280.1 1099.81
   352.1 1093.93   362.1 1093.34   372.1 1094.32   538.1 1098.96   593.1 1103.54
   623.7 1123.29   635.3 1124.88   658.5 1140.89   667.7 1150.13   713.7  1181.6
   734.7 1193.35   745.3  1194.3   755.8 1199.88   787.4 1219.03     840 1255.56
   850.5 1257.27   871.5 1275.15   945.2 1347.91   955.7 1349.03   970.1 1361.02
#Mann= 3 , 0 , 0
       0     .06       0   352.1    .045       0   372.1     .06       0
Bank Sta=352.1,372.1
XS Rating Curve= 0 ,0
Exp/Cntr=0.3,0.1

Type RM Length L Ch R = 1 ,28652.8 ,153.9,153.4,152.9
XS GIS Cut Line= 4
     1671641.361      218746.659     1671500.448      218964.308
     1671327.445      219274.038     1671086.079      219493.081
#Sta/Elev= 30
       0 1281.91    33.2 1265.48    49.2 1261.15   141.9 1192.59     154 1184.48
     166 1181.81   220.1 1144.18   229.1 1135.92   256.8 1120.42   262.5 1117.36
   274.1 1116.53   308.8 1100.06     351 1091.01     361 1090.05     371 1091.36
   506.3  1092.3   562.1 1096.27   599.2 1105.44   610.8 1106.13     643 1117.21
   714.2 1150.96   727.8  1161.4   745.5 1166.78     810 1199.63   822.4 1212.22
   851.1  1234.4   881.3  1256.8   896.4 1262.76   908.5 1276.54     940  1298.9
#Mann= 3 , 0 , 0
       0     .06       0     351    .045       0     371     .06       0
Bank Sta=351,371
XS Rating Curve= 0 ,0
Exp/Cntr=0.3,0.1

Type RM Length L Ch R = 1 ,28499.4 ,157.9,157,156.2
XS GIS Cut Line= 4
      1671497.62      218683.917     1671374.844      218871.801
     1671157.196      219281.054     1670993.494      219487.541
#Sta/Elev= 30
       0 1280.74    57.5 1249.75    95.5 1221.92   108.3 1219.69   131.6 1198.26
   156.7 1178.29   205.1 1146.73   217.2  1145.4   267.4 1116.44   309.8 1094.39
   320.9 1089.64   329.8 1089.22   339.8 1088.28   349.8 1088.63   557.1 1089.18
   564.6 1090.83   594.6  1106.8   619.4 1110.84   630.9 1118.36   653.8 1137.03
   665.3 1138.54   688.3 1155.48   765.9  1204.1   778.9    1205   817.7 1231.13
   830.6 1240.93   869.4 1279.33   895.3 1301.96   908.2    1302   951.5 1337.38
#Mann= 3 , 0 , 0
       0      .1       0   329.8    .045       0   349.8     .06       0
Bank Sta=329.8,349.8
XS Rating Curve= 0 ,0
Exp/Cntr=0.3,0.1

Type RM Length L Ch R = 1 ,28342.4 ,152,151,150
XS GIS Cut Line= 4
     1671303.727      218667.134     1671208.855      218845.717
     1671052.595      219166.609     1670943.771      219437.274
#Sta/Elev= 30
       0 1245.53     4.3 1245.53    18.3 1238.34    64.2 1207.47    86.7 1190.25
    98.7 1188.88   190.5 1128.81     202 1126.98   258.3 1089.15   269.6 1085.65
   349.8 1085.76   359.8 1085.52   369.8 1085.75   495.1 1086.65   506.3 1090.64
   517.6 1099.57   528.9  1100.5   540.2 1105.86   555.4  1107.7   573.5  1112.7
   606.3  1125.5   628.2 1136.52   639.1 1136.77   660.9 1150.65   682.8 1166.31
   737.4 1208.09   748.3 1208.38   802.9 1250.05   846.6 1290.98   850.9 1291.04
#Mann= 3 , 0 , 0
       0      .1       0   349.8    .045       0   369.8     .06       0
Bank Sta=349.8,369.8
XS Rating Curve= 0 ,0
Exp/Cntr=0.3,0.1

Type RM Length L Ch R = 1 ,28191.3 ,220.4,220.2,220.1
XS GIS Cut Line= 4
     1671173.938      218609.507     1671077.205      218763.907
     1670907.923      219148.977     1670900.482      219437.315
#Sta/Elev= 30
       0 1240.11    15.3 1234.87    27.3  1233.6    39.3 1227.92    98.7 1190.55
   134.9 1163.03   146.9 1162.07   204.9 1118.31     227 1103.33   249.2 1091.24
   260.2 1090.75   283.5 1082.54   293.5  1082.3   303.5 1082.99   492.8 1085.61
   514.9  1088.7     537 1100.44   559.2 1107.77   570.3 1113.29   581.3 1114.34
   623.7 1134.94   674.4 1162.91   684.5 1162.94   775.8 1210.74   785.9 1210.81
     802  1221.2   846.8 1254.37   877.2 1282.08   887.3 1282.09   891.3 1285.96
#Mann= 3 , 0 , 0
       0      .1       0   283.5    .045       0   303.5     .06       0
Bank Sta=283.5,303.5
XS Rating Curve= 0 ,0
Exp/Cntr=0.3,0.1

Type RM Length L Ch R = 1 ,27971.1 ,143.3,144.3,145.3
XS GIS Cut Line= 4
      1670960.01      218533.238     1670861.417        218708.1
      1670725.62      219020.621     1670865.138      219422.433
#Sta/Elev= 30
       0 1233.06    21.3 1219.58    28.8 1211.03    32.7 1208.32    79.2 1180.35
    90.8 1178.42   145.7 1143.98   166.4 1128.22     187 1116.13   195.6 1111.29
   206.9 1110.01   261.5 1082.84   274.2 1078.58   284.2 1077.61   294.2 1077.68
   335.9  1078.5     420 1084.66   515.4 1094.22   602.9 1098.55   624.3 1109.74
   635.1 1109.91     678 1119.56   710.2 1133.27   742.4 1152.04   753.1 1152.43
   818.5 1197.35   849.6 1214.49   864.6 1216.69     930 1253.04   966.8 1276.56
#Mann= 3 , 0 , 0
       0      .1       0   274.2    .045       0   294.2     .06       0
Bank Sta=274.2,294.2
XS Rating Curve= 0 ,0
Exp/Cntr=0.3,0.1

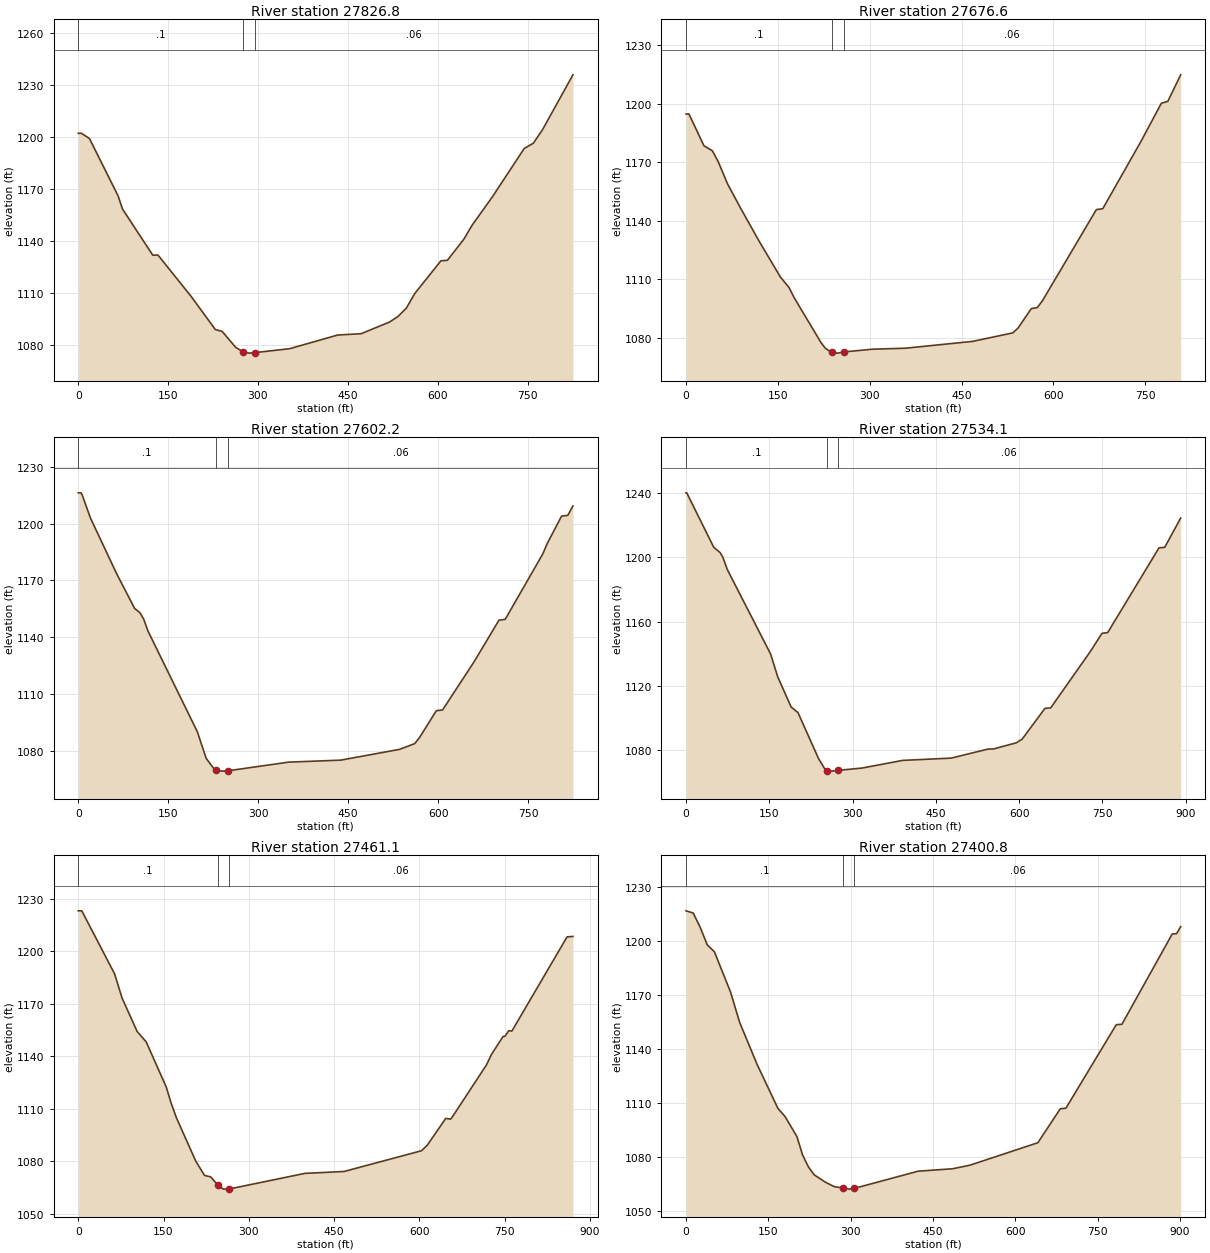
Type RM Length L Ch R = 1 ,27826.8 ,137.7,150.2,162.7
XS GIS Cut Line= 4
     1670831.653      218484.871     1670730.308      218657.368
     1670642.411      218838.741     1670327.528      219122.934
#Sta/Elev= 30
       0 1202.18     5.2 1202.18    18.6 1199.21    66.5 1166.09    73.9  1158.5
   124.4 1131.92   133.1 1131.99     188 1108.35   228.9 1089.04   240.2 1088.01
   262.7 1078.83   275.2  1076.2   285.2 1075.47   295.2 1075.77   352.8 1078.02
   433.1  1085.9   472.2 1086.66   519.3 1093.34   533.6 1096.53   547.8 1101.45
   561.7 1109.79   605.4 1128.69   616.3 1128.97   643.6 1141.09   657.3 1149.09
   691.5 1165.62   744.5 1193.43   759.6 1196.43   774.8 1204.09   825.8 1235.88
#Mann= 3 , 0 , 0
       0      .1       0   275.2    .045       0   295.2     .06       0
Bank Sta=275.2,295.2
XS Rating Curve= 0 ,0
Exp/Cntr=0.3,0.1

Type RM Length L Ch R = 1 ,27676.6 ,77.2,74.4,71.5
XS GIS Cut Line= 4
     1670762.397      218459.252     1670638.226      218591.794
     1670417.788       218749.45     1670311.754      219088.479
#Sta/Elev= 30
       0 1194.63     4.8 1194.63    29.3 1178.36    43.1  1175.8    52.8 1170.06
    67.7 1158.93    88.8 1146.62   119.5 1129.46   154.3  1111.1   168.1 1105.87
   176.9 1100.45   220.4 1077.63   227.7 1074.65   237.8 1072.58   247.8 1072.21
   257.8 1072.82   304.1 1074.21   358.5 1074.73   468.3 1078.23   533.9 1082.59
   542.6 1085.18   563.9 1095.01   573.7 1095.52   582.4 1099.16   670.1 1145.67
   680.7 1146.18   743.5 1180.87   776.3 1200.13   786.9 1201.12   807.9  1214.7
#Mann= 3 , 0 , 0
       0      .1       0   237.8    .045       0   257.8     .06       0
Bank Sta=237.8,257.8
XS Rating Curve= 0 ,0
Exp/Cntr=0.3,0.1

Type RM Length L Ch R = 1 ,27602.2 ,74.1,68.1,62.2
XS GIS Cut Line= 4
     1670720.929      218407.034     1670589.085      218527.368
      1670396.55      218701.068     1670303.421      219076.721
#Sta/Elev= 30
       0 1216.22     4.8 1216.22     6.5 1215.13    20.2 1202.99      64  1173.5
    94.1 1155.12   102.6 1153.01   109.1 1149.54   116.3 1143.21   198.5 1090.09
   213.3 1076.03   225.8 1070.72   229.5 1069.94   239.5 1069.28   249.5 1069.46
   350.8 1074.03   437.8 1075.09   535.9 1080.78     561 1083.81   569.3 1087.12
     597 1101.18   607.5 1101.59   659.7 1126.87   701.5 1148.98   711.9 1149.43
   774.6 1183.98   781.9 1189.42   805.9 1203.94   816.3 1204.33   824.8  1209.3
#Mann= 3 , 0 , 0
       0      .1       0   229.5    .045       0   249.5     .06       0
Bank Sta=229.5,249.5
XS Rating Curve= 0 ,0
Exp/Cntr=0.3,0.1

Type RM Length L Ch R = 1 ,27534.1 ,77.5,73,68.4
XS GIS Cut Line= 4
     1670682.834      218337.912     1670550.757      218443.946
     1670346.131      218739.724     1670288.463      219096.891
#Sta/Elev= 30
       0 1240.28     1.3 1240.28    49.8 1206.42    61.3 1203.09      66  1200.4
    74.3 1192.52   152.3 1139.87   165.3 1125.51   189.3 1106.87   201.6  1103.4
   238.6 1074.77   250.9 1067.72   253.2  1067.3   263.2 1066.91   273.2 1067.35
   317.3 1068.84   390.1  1073.6   477.5 1075.02   543.8 1080.64     554 1080.75
   595.1 1084.58   605.4 1086.88   646.4 1106.03   656.7  1106.3   728.6 1141.67
   749.1 1152.76   759.4 1153.23   851.8 1206.04     862  1206.3   890.8 1224.57
#Mann= 3 , 0 , 0
       0      .1       0   253.2    .045       0   273.2     .06       0
Bank Sta=253.2,273.2
XS Rating Curve= 0 ,0
Exp/Cntr=0.3,0.1

Type RM Length L Ch R = 1 ,27461.1 ,64.2,60.4,56.5
XS GIS Cut Line= 4
     1670603.799      218294.289     1670476.837      218396.137
     1670330.343      218724.005     1670280.117      219068.615
#Sta/Elev= 30
       0 1223.11     6.2 1223.11    63.9 1187.05    76.9 1173.34   103.4 1154.18
   119.6 1148.07   154.9 1122.21   162.8 1113.66   172.5 1104.84   206.7 1079.92
     222  1071.8   233.1  1070.9   245.3 1066.28   255.3 1063.94   265.3 1064.01
   398.5 1072.94   467.6 1074.04   603.7  1085.9   613.9 1089.09   646.3 1104.38
   654.9 1103.99   658.1  1105.3   717.9 1134.97   726.6 1140.88   747.1 1151.24
   750.3 1151.32   757.3 1154.59   762.6 1154.31   859.7  1208.2     870 1208.45
#Mann= 3 , 0 , 0
       0      .1       0   245.3    .045       0   265.3     .06       0
Bank Sta=245.3,265.3
XS Rating Curve= 0 ,0
Exp/Cntr=0.3,0.1

Type RM Length L Ch R = 1 ,27400.8 ,194.3,191.2,188.1
XS GIS Cut Line= 4
     1670522.853      218216.997     1670409.379      218362.095
     1670308.926      218728.563     1670271.721      219063.406
#Sta/Elev= 30
       0 1216.68      13 1215.48    25.8 1207.52    38.7 1197.74    51.6 1193.96
    81.1 1171.51    97.6  1154.7   129.5 1131.25   167.4 1106.81   180.2 1102.38
     202 1091.17   212.4 1080.84     223 1074.25   233.5 1069.87   253.7 1065.81
   270.2 1063.28   286.6 1062.56   296.6 1061.92   306.6 1062.33   422.7 1071.89
   485.7 1073.25   517.3 1075.24     641 1087.74   681.8 1106.62     692 1106.93
   783.8 1153.38     794 1153.56   885.8 1203.85   893.6 1203.98   901.1 1207.88
#Mann= 3 , 0 , 0
       0      .1       0   286.6    .045       0   306.6     .06       0
Bank Sta=286.6,306.6
XS Rating Curve= 0 ,0
Exp/Cntr=0.3,0.1

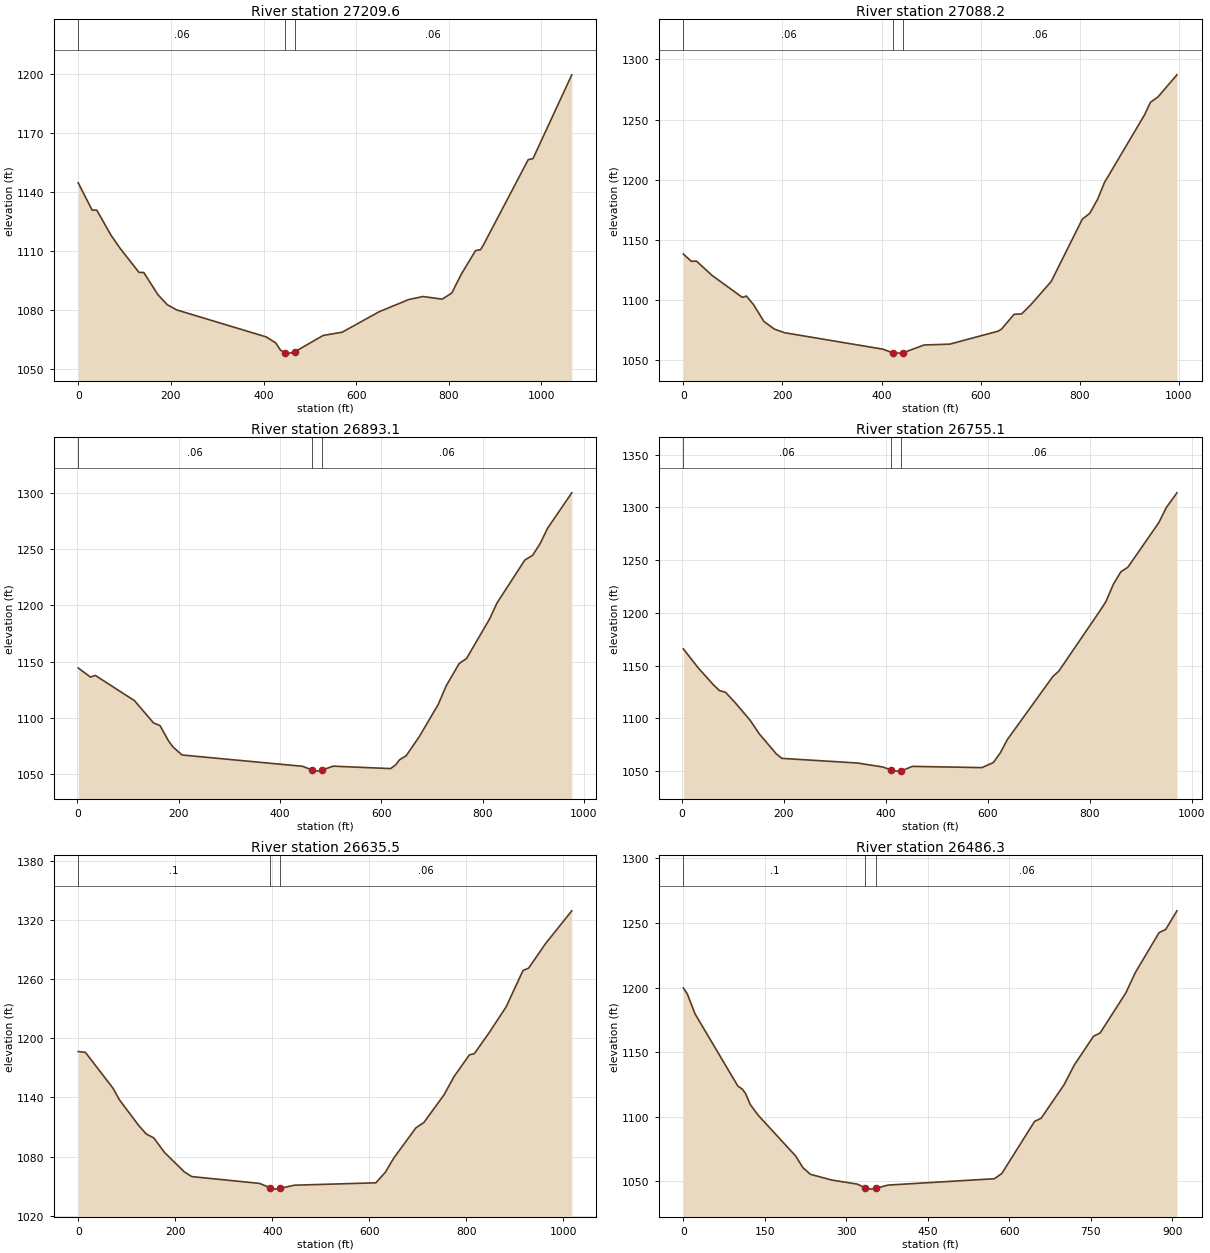
Type RM Length L Ch R = 1 ,27209.6 ,119.5,121.4,123.3
XS GIS Cut Line= 4
     1670193.591      217984.466     1670208.473       218323.03
     1670158.246      218669.035     1670228.935      219039.223
#Sta/Elev= 30
       0 1144.64    29.9  1130.8    40.1 1130.77    70.5 1118.14    90.8 1111.27
   131.2 1099.18   141.5 1099.12     172  1087.9   192.3 1082.78   212.5 1080.15
   405.9 1066.44   426.4 1063.41   436.7  1059.7   447.1 1058.26   457.1 1058.22
   467.1 1058.86   528.8 1067.19   569.8 1068.84     650 1079.27   713.4  1085.4
   744.2 1086.94   785.6  1085.6   806.3 1088.67   826.9 1098.28   857.8  1110.3
   868.2 1110.62   874.4    1113   971.4 1156.39   981.7 1156.91  1065.4 1199.41
#Mann= 3 , 0 , 0
       0     .06       0   447.1    .045       0   467.1     .06       0
Bank Sta=447.1,467.1
XS Rating Curve= 0 ,0
Exp/Cntr=0.3,0.1

Type RM Length L Ch R = 1 ,27088.2 ,184.1,195.1,206.1
XS GIS Cut Line= 4
     1670176.421      217998.842     1670095.501      218312.758
     1670045.274      218537.382     1669714.616       218830.37
#Sta/Elev= 30
       0 1138.26      16 1132.25    26.5 1132.41    57.9 1120.52   118.9 1102.29
   127.2 1103.38   141.6 1096.23   162.6 1082.23   183.5 1075.95   204.4 1072.88
   402.7 1059.22   423.9 1055.97   433.9 1055.93   443.9 1056.27   485.8 1062.69
   537.7 1063.41   634.8 1074.14     642 1075.84   667.4 1088.18   682.7 1088.56
   700.8 1095.95   742.5 1115.58     805 1167.18   820.2 1172.15   836.2 1183.95
   849.7  1197.6     931 1254.17   942.5 1264.31   957.8 1268.86   996.1 1287.23
#Mann= 3 , 0 , 0
       0     .06       0   423.9    .045       0   443.9     .06       0
Bank Sta=423.9,443.9
XS Rating Curve= 0 ,0
Exp/Cntr=0.3,0.1

Type RM Length L Ch R = 1 ,26893.1 ,133.2,138,142.8
XS GIS Cut Line= 4
     1670176.849      217986.327     1670000.126      218216.997
     1669730.391      218566.722     1669556.961      218738.288
#Sta/Elev= 30
     1.5  1144.4    25.7 1136.33    35.3  1137.8   112.5 1115.46   150.2 1095.68
   163.1 1093.29   179.9 1079.65   188.5 1074.41   206.5 1067.23   444.3  1057.2
   463.9 1053.89   473.9 1052.91   483.9 1053.94   504.8 1057.31   618.4 1055.16
   628.4 1058.45   636.3 1063.08   649.1 1066.53   674.7 1083.28   712.4 1111.99
     728  1128.4   753.9 1148.42   768.3 1152.72   814.2 1188.13   828.4 1201.95
   883.6 1240.17   898.9 1244.29     914 1254.92   928.2 1268.19   976.2 1299.73
#Mann= 3 , 0 , 0
     1.5     .06       0   463.9    .045       0   483.9     .06       0
#XS Ineff= 2 , 0
       0                     504       0
Permanent Ineff=
       F       F
Bank Sta=463.9,483.9
XS Rating Curve= 0 ,0
Exp/Cntr=0.3,0.1

Type RM Length L Ch R = 1 ,26755.1 ,119.4,119.7,119.9
XS GIS Cut Line= 4
     1670071.783      217933.269     1669929.474      218142.546
     1669662.995      218376.936     1669414.652      218642.021
#Sta/Elev= 30
     3.1 1165.95    32.3 1147.88    61.3 1132.29    73.6 1126.46    85.8 1124.81
   105.3 1114.64   133.9 1098.42   151.9  1085.5   185.5 1066.41   196.1 1062.21
   344.6 1057.81   394.8 1053.99   410.3 1051.19   420.3 1050.12   430.3 1050.29
   452.3 1054.62   588.8 1053.45   611.1 1058.27   624.6 1067.33   638.9 1080.26
     728 1139.89   739.4 1144.76   819.5  1201.5   831.8 1210.62   846.6 1227.25
   861.1 1238.88     875  1243.3   935.5 1285.39   950.4 1299.84   971.2 1313.76
#Mann= 3 , 0 , 0
     3.1     .06       0   410.3    .045       0   430.3     .06       0
#XS Ineff= 2 , 0
       0                     460       0
Permanent Ineff=
       F       F
Bank Sta=410.3,430.3
XS Rating Curve= 0 ,0
Exp/Cntr=0.3,0.1

Type RM Length L Ch R = 1 ,26635.5 ,148.8,149.2,149.6
XS GIS Cut Line= 4
     1670041.051      217893.315     1669856.887      218049.575
     1669555.528      218310.009     1669371.364      218639.271
#Sta/Elev= 30
       0 1186.49    14.8 1185.72    71.7 1149.35      85 1137.57   124.4 1111.74
   140.1 1102.99   155.8 1098.94   178.1 1084.11   218.4 1064.67   234.1 1059.78
   373.7 1052.87   395.3 1048.45   405.3 1047.07   415.3 1047.78   445.5 1051.05
   613.4 1053.47     633 1064.24   650.1 1078.43   695.9 1109.21   712.4 1114.64
   753.9 1142.73   774.6 1161.23   806.1 1183.18   816.2 1184.34   846.9  1205.7
   881.7 1231.74   916.6 1268.68   928.2 1271.07     963 1295.95  1017.1 1329.17
#Mann= 3 , 0 , 0
       0      .1       0   395.3    .045       0   415.3     .06       0
Bank Sta=395.3,415.3
XS Rating Curve= 0 ,0
Exp/Cntr=0.3,0.1

Type RM Length L Ch R = 1 ,26486.3 ,142.3,142.3,142.2
XS GIS Cut Line= 4
     1669900.175      217800.727     1669778.795      217924.898
     1669491.387      218164.869     1669296.062      218467.623
#Sta/Elev= 30
       0 1199.61     7.2 1195.08    21.7 1179.44   100.3 1123.67   108.7 1121.22
   114.5 1117.85   123.2 1109.34   137.7 1101.09   206.9 1069.39   220.1 1060.43
   233.7 1055.35     273  1050.9   320.1 1047.72   334.9 1044.79   344.9 1043.85
   354.9  1044.5   376.5 1046.98   572.4  1051.9   586.1 1055.96   646.4 1096.34
   658.4 1098.71   700.7 1124.73   719.4 1139.91   754.9  1162.3     767 1164.79
   814.3 1195.82   831.6 1211.44   875.6 1242.58   887.7 1244.98   908.4 1259.42
#Mann= 3 , 0 , 0
       0      .1       0   334.9    .045       0   354.9     .06       0
Bank Sta=334.9,354.9
XS Rating Curve= 0 ,0
Exp/Cntr=0.3,0.1

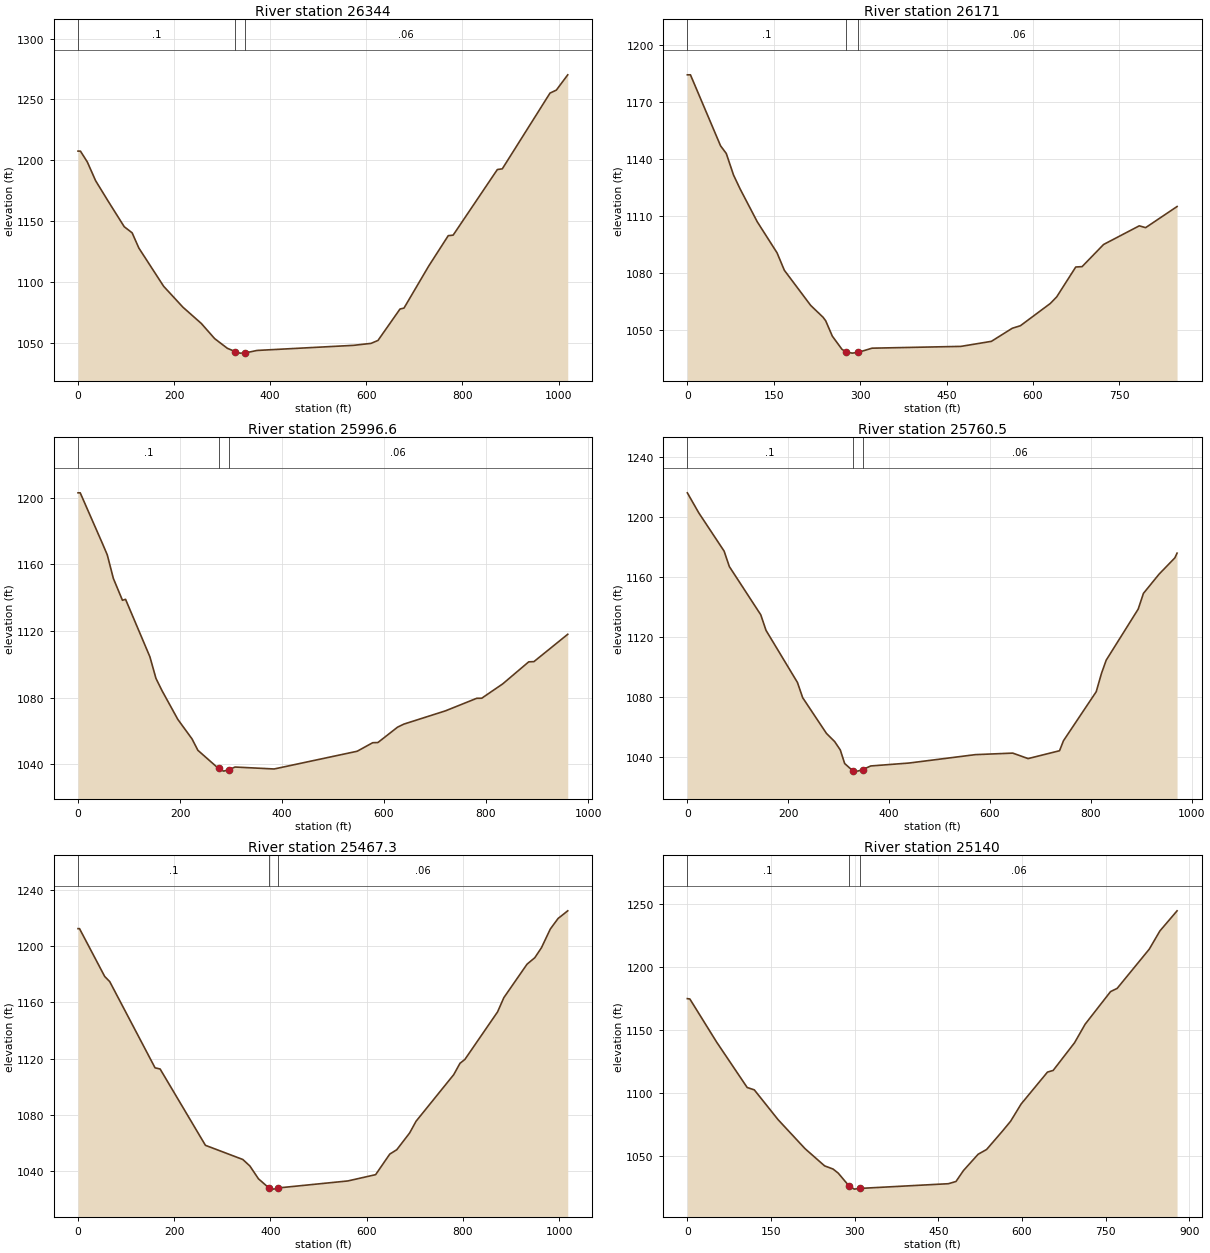
Type RM Length L Ch R = 1 ,26344   ,167.9,173,178.1
XS GIS Cut Line= 4
     1669832.704       217701.71     1669704.347      217802.163
     1669315.557      218127.705     1669269.051       218473.71
#Sta/Elev= 30
       0 1207.52       5 1207.52    19.4 1198.56    36.6 1183.22    62.7 1166.42
    96.2 1145.41   112.6 1140.41   126.6  1127.9   178.2 1096.49   218.2 1079.37
   256.7 1065.92   284.3 1053.53   310.7 1045.58   327.2 1042.84   337.2  1041.6
   347.2 1041.69   372.5  1043.8   573.9    1048   609.9 1049.62   624.3 1052.03
   670.1 1077.81   678.4  1078.6   729.6 1112.95   770.5 1138.07   780.7  1138.5
   872.7 1192.38     883 1192.96   982.3 1255.17   995.5 1257.63  1019.2 1270.17
#Mann= 3 , 0 , 0
       0      .1       0   327.2    .045       0   347.2     .06       0
Bank Sta=327.2,347.2
XS Rating Curve= 0 ,0
Exp/Cntr=0.3,0.1

Type RM Length L Ch R = 1 ,26171   ,174.4,174.5,174.5
XS GIS Cut Line= 4
     1669706.245      217615.168     1669545.799      217733.758
     1669237.465      217899.785     1669118.874       218176.03
#Sta/Elev= 30
       0 1184.28     5.4 1184.28    57.7 1146.99    67.6 1142.97    80.2 1131.64
    91.8 1124.24   121.4 1107.09   155.8 1090.77   168.4 1081.64   214.2 1063.16
   235.5    1057   240.2 1055.11   251.7 1047.05   268.5  1040.1   276.2 1038.68
   286.2 1038.11   296.2 1038.47   320.8 1040.71     475 1041.65     528 1044.31
   564.1 1051.16   578.3  1052.5   630.3 1064.21   641.3 1067.65   674.4 1083.34
   685.4 1083.54   722.7 1095.17   784.7 1104.97   795.7 1104.01   850.3  1115.1
#Mann= 3 , 0 , 0
       0      .1       0   276.2    .045       0   296.2     .06       0
Bank Sta=276.2,296.2
XS Rating Curve= 0 ,0
Exp/Cntr=0.3,0.1

Type RM Length L Ch R = 1 ,25996.6 ,240.5,236.1,231.7
XS GIS Cut Line= 4
     1669609.475      217489.642     1669438.333      217595.676
     1669153.716      217748.216      1669107.21      218181.652
#Sta/Elev= 30
       0 1203.01     4.3 1203.01    48.5 1172.12    57.4 1165.69    69.3 1151.57
    87.1 1138.45    93.2 1139.03   140.9 1104.53   152.8 1091.55   164.7 1084.16
   195.7 1066.89   223.5 1055.19     235 1048.34   275.5  1037.4   285.5 1035.82
   295.5 1036.64   307.9 1038.28   384.5 1037.11   547.3 1047.76   577.8 1052.89
     588    1053   626.5 1062.23     639 1064.08   720.6 1072.05   781.7 1079.57
   791.5 1079.61   832.7 1088.23   883.7 1101.47   893.9 1101.61   960.2 1118.03
#Mann= 3 , 0 , 0
       0      .1       0   275.5    .045       0   295.5     .06       0
Bank Sta=275.5,295.5
XS Rating Curve= 0 ,0
Exp/Cntr=0.3,0.1

Type RM Length L Ch R = 1 ,25760.5 ,295.8,293.2,290.5
XS GIS Cut Line= 4
     1669540.646      217338.963     1669289.514       217394.77
     1668993.735        217627.3     1668664.472       217701.71
#Sta/Elev= 30
       0 1215.96    22.6 1202.65    72.9 1177.11    83.3  1166.8   145.6 1134.65
     156 1124.29   218.3 1089.56   228.7 1079.39   275.8 1055.59   292.2 1050.11
   303.3 1044.54     312 1035.48   327.8 1030.75   337.8 1030.43   347.8 1031.47
   363.6 1033.87   439.8 1035.83     571 1041.42   645.3 1042.44   675.7 1038.79
   738.1 1044.03   745.8 1050.67   810.8 1083.38   821.2 1095.57   830.6 1104.41
     894 1138.44   904.4 1148.92   935.5 1161.77   966.7 1172.59   971.1 1175.76
#Mann= 3 , 0 , 0
       0      .1       0   327.8    .045       0   347.8     .06       0
Bank Sta=327.8,347.8
XS Rating Curve= 0 ,0
Exp/Cntr=0.3,0.1

Type RM Length L Ch R = 1 ,25467.3 ,326.2,327.3,328.5
XS GIS Cut Line= 4
     1669213.244      216825.536     1669131.393      217141.777
     1668867.239       217398.49     1668616.106      217601.257
#Sta/Elev= 30
       0  1212.4     3.1  1212.4    55.4 1178.47    65.9 1174.78   160.1 1113.58
   170.6 1112.76   264.8 1058.57   342.5 1048.51   357.1 1043.92     375 1034.81
   396.5 1028.38   406.5 1027.47   416.5 1028.33   560.7 1033.27   618.5 1037.74
   647.9 1052.33   662.5 1055.45   689.2 1067.35   702.6 1075.68   780.8 1108.73
   793.8 1116.77   804.1 1119.58     872 1153.32     885  1163.4   933.2 1187.16
   949.3 1191.74   963.2 1198.86   981.6 1212.14   997.7  1219.6  1017.8 1225.04
#Mann= 3 , 0 , 0
       0      .1       0   396.5    .045       0   416.5     .06       0
Bank Sta=396.5,416.5
XS Rating Curve= 0 ,0
Exp/Cntr=0.3,0.1

Type RM Length L Ch R = 1 ,25140   ,426.6,415.2,403.8
XS GIS Cut Line= 4
     1669025.359      216764.148     1668913.745      216907.387
     1668623.547        217164.1     1668459.846      217426.394
#Sta/Elev= 30
       0 1175.02     4.5 1174.75    52.5 1140.51   107.3 1104.43   120.1 1102.54
   162.7 1078.89     211 1055.86   246.1 1042.18   261.4 1039.63   270.6 1036.39
   289.3 1026.56   299.3 1023.69   309.3 1024.25   468.1 1027.99   481.7 1029.75
   495.2 1038.48   521.4 1051.37   536.7  1055.2     565 1069.74   579.7 1077.63
   598.6 1091.33   645.8 1116.66     656 1117.98   694.3 1139.95   713.4 1154.73
   758.9  1180.6   770.8 1183.17   828.3  1214.3   847.4 1228.79   878.2 1244.78
#Mann= 3 , 0 , 0
       0      .1       0   289.3    .045       0   309.3     .06       0
Bank Sta=289.3,309.3
XS Rating Curve= 0 ,0
Exp/Cntr=0.3,0.1

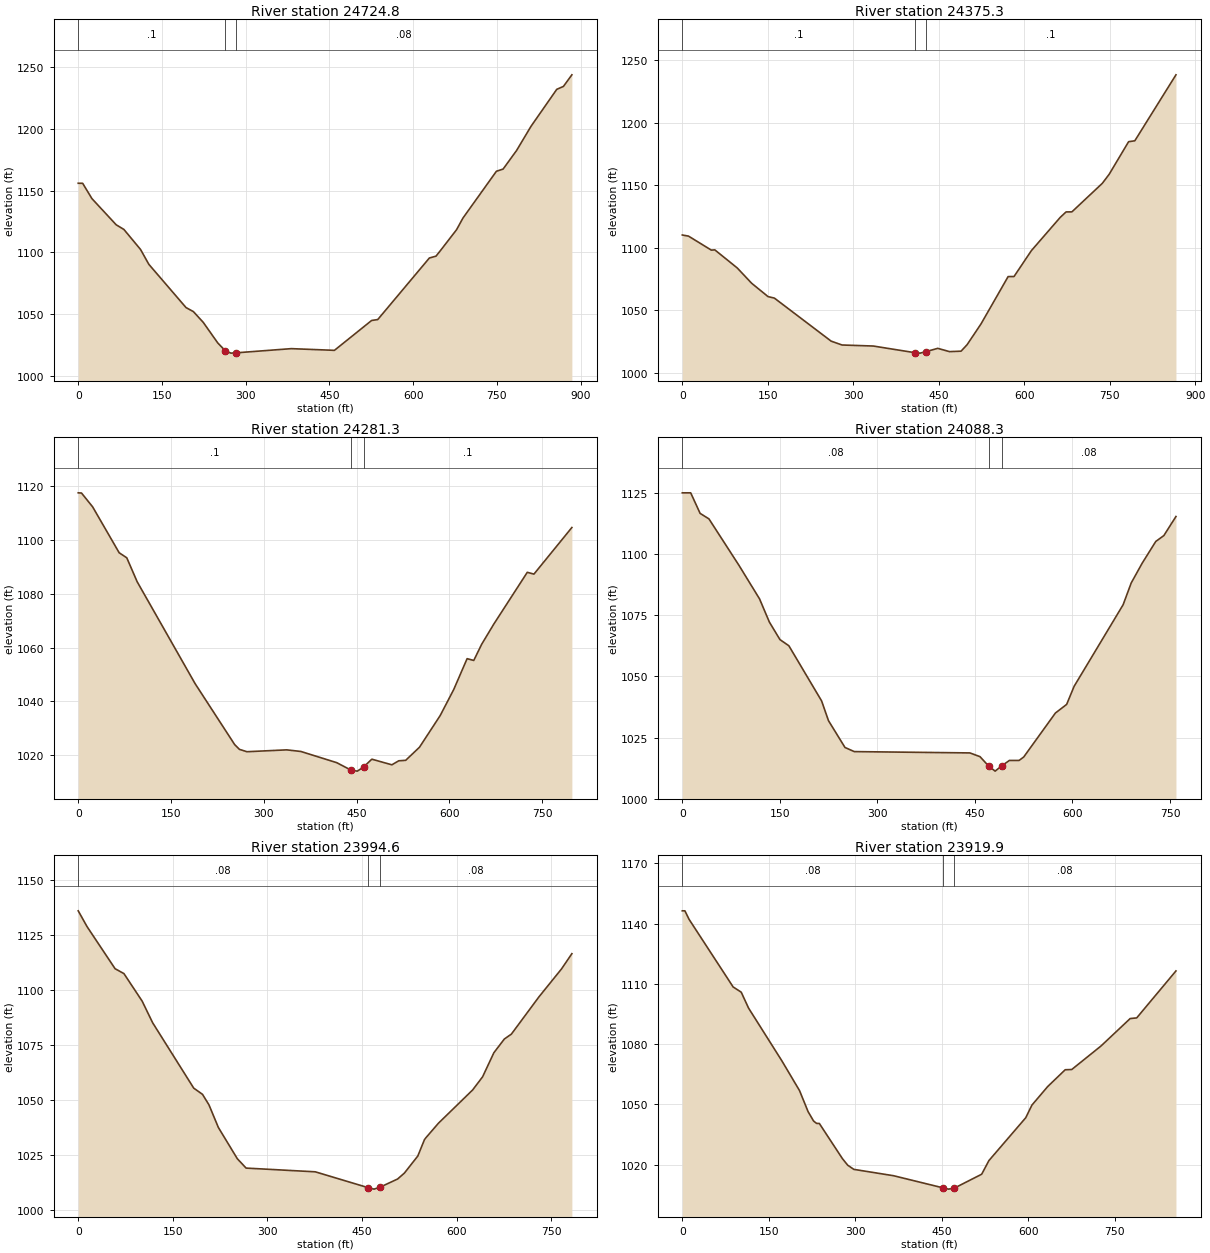
Type RM Length L Ch R = 1 ,24724.8 ,355.1,349.5,343.9
XS GIS Cut Line= 4
     1668714.699      216464.649     1668575.181      216613.469
     1668430.082      216955.753     1668264.521      217216.187
#Sta/Elev= 30
       0 1155.88     7.9 1155.88    24.6 1143.46      68 1122.35    81.9 1118.56
   111.7 1102.38   126.5 1090.43   193.1  1055.5   206.3 1052.24     224 1043.54
     250 1026.93   263.5  1020.6   273.5  1018.7   283.5 1018.96   381.7 1022.32
     459 1020.95   525.6 1045.06   536.6  1045.8   629.1 1095.52     641 1097.03
   648.4  1101.2   677.8 1118.36   689.2 1127.74   749.2 1165.57   761.2 1167.35
   785.3 1182.31   811.1 1201.81   857.3 1231.72   869.3 1234.11   884.4 1243.45
#Mann= 3 , 0 , 0
       0      .1       0   263.5    .045       0   283.5     .08       0
Bank Sta=263.5,283.5
XS Rating Curve= 0 ,0
Exp/Cntr=0.3,0.1

Type RM Length L Ch R = 1 ,24375.3 ,87.6,94,100.5
XS GIS Cut Line= 4
     1668362.686      216335.787     1668246.886      216600.871
      1668196.66      216886.883     1668216.192      217172.895
#Sta/Elev= 30
       0 1110.28    10.9 1109.38      51 1098.19    57.1  1098.4    96.4 1083.97
   121.7 1071.74   150.5 1061.07   161.6 1059.89   261.2 1025.52   280.3 1022.44
   335.1 1021.62   407.5 1016.35   417.5 1015.95   427.5 1017.13   448.3 1019.77
   468.9 1017.15   489.2 1017.51   499.8 1022.69   524.2 1039.27   571.8 1077.07
   582.1 1077.11   612.6  1097.8   663.2 1124.34   673.5 1128.71   683.7 1128.75
   737.1 1151.54   749.1 1158.76   783.2 1184.78   794.1  1185.5   866.3 1238.18
#Mann= 3 , 0 , 0
       0      .1       0   407.5    .045       0   427.5      .1       0
Bank Sta=407.5,427.5
XS Rating Curve= 0 ,0
Exp/Cntr=0.3,0.1

Type RM Length L Ch R = 1 ,24281.3 ,178.7,193,207.3
XS GIS Cut Line= 4
     1668357.533       216317.69     1668214.797      216526.927
     1668072.488      216836.657     1668001.334      217027.797
#Sta/Elev= 30
       0 1117.59     5.3 1117.51    23.3 1112.38    66.2  1095.3    78.5 1093.42
    95.3 1084.51   188.9 1046.64     253 1023.92   260.7 1022.16   272.8 1021.29
   337.1 1021.98     360 1021.38   417.8 1017.23   441.3 1014.41   451.3 1014.07
   461.3 1015.61   474.7 1018.51   507.1 1016.42   518.2 1017.91   529.4 1018.09
   551.7 1022.95   585.2 1034.74   607.1 1044.43   628.7  1055.9   639.5 1055.24
   652.2 1061.23   671.9 1068.77     726 1088.02   736.8 1087.36   798.1 1104.69
#Mann= 3 , 0 , 0
       0      .1       0   441.3    .045       0   461.3      .1       0
Bank Sta=441.3,461.3
XS Rating Curve= 0 ,0
Exp/Cntr=0.3,0.1

Type RM Length L Ch R = 1 ,24088.3 ,87.2,93.7,100.2
XS GIS Cut Line= 4
     1668312.459      216250.681      1668029.69      216564.265
     1667885.986      216656.347     1667751.597      216754.341
#Sta/Elev= 30
       0 1125.13    12.9 1125.13    27.4 1116.72      41 1114.46    87.3 1095.39
   118.8 1081.73   133.9 1072.25   150.2 1065.06   163.9 1062.54   214.3 1039.94
   224.8  1031.9   250.2 1020.92   264.5 1019.23   442.3 1018.69   457.8 1017.17
   471.1 1013.32   481.1 1011.24   491.1 1013.37   503.1 1015.62     518 1015.62
   525.1 1017.03   573.8 1035.01   591.1 1038.55   602.6 1045.95   677.9  1079.3
   690.4 1088.24   707.2 1096.31   728.1 1105.21   740.6 1107.64   759.2 1115.44
#Mann= 3 , 0 , 0
       0     .08       0   471.1    .045       0   491.1     .08       0
Bank Sta=471.1,491.1
XS Rating Curve= 0 ,0
Exp/Cntr=0.3,0.1

Type RM Length L Ch R = 1 ,23994.6 ,74.8,74.7,74.6
XS GIS Cut Line= 4
     1668303.145      216228.026     1668082.707      216465.207
     1667846.921      216540.547     1667726.936      216714.944
#Sta/Elev= 30
       0 1136.02    13.9  1128.9    58.5 1109.73    72.5 1107.52   101.4 1095.02
   118.1 1085.17   183.2 1055.51   197.1  1052.7   207.4 1047.91   222.3 1037.64
   252.3 1023.48   266.3  1019.2     376 1017.51   459.2 1010.37   469.2 1009.65
   479.2 1010.59   506.6 1014.25   517.3 1016.92   538.6 1024.67   549.2 1032.13
   551.7 1033.06   571.3 1039.56   625.6 1054.68   641.4 1060.65   659.3 1071.59
   675.8 1077.78   687.1 1080.06   730.8 1096.96   766.6 1109.65     783 1116.56
#Mann= 3 , 0 , 0
       0     .08       0   459.2    .045       0   479.2     .08       0
Bank Sta=459.2,479.2
XS Rating Curve= 0 ,0
Exp/Cntr=0.3,0.1

Type RM Length L Ch R = 1 ,23919.9 ,474.4,444.7,415
XS GIS Cut Line= 4
     1668301.725      216196.775     1668139.885      216367.917
     1667771.557      216486.972     1667669.244      216697.179
#Sta/Elev= 30
       0  1146.4     4.5  1146.4    11.7 1142.19    88.2 1108.48   102.2 1105.88
   114.9 1097.98   172.9  1071.6   203.4 1056.84   218.2 1046.39   227.7 1041.72
   232.9 1040.51   237.7 1040.49   277.9 1022.91   286.9 1019.71   297.6 1017.61
   366.5 1014.45   451.9 1008.43   461.9 1007.77   471.9 1008.27   519.4  1015.2
   531.9 1021.98   595.8 1043.33   606.5 1049.61   633.8 1058.84   664.3 1067.24
   675.6 1067.35   726.5  1079.1     777 1092.74   788.3 1093.06   856.4 1116.46
#Mann= 3 , 0 , 0
       0     .08       0   451.9    .045       0   471.9     .08       0
Bank Sta=451.9,471.9
XS Rating Curve= 0 ,0
Exp/Cntr=0.3,0.1