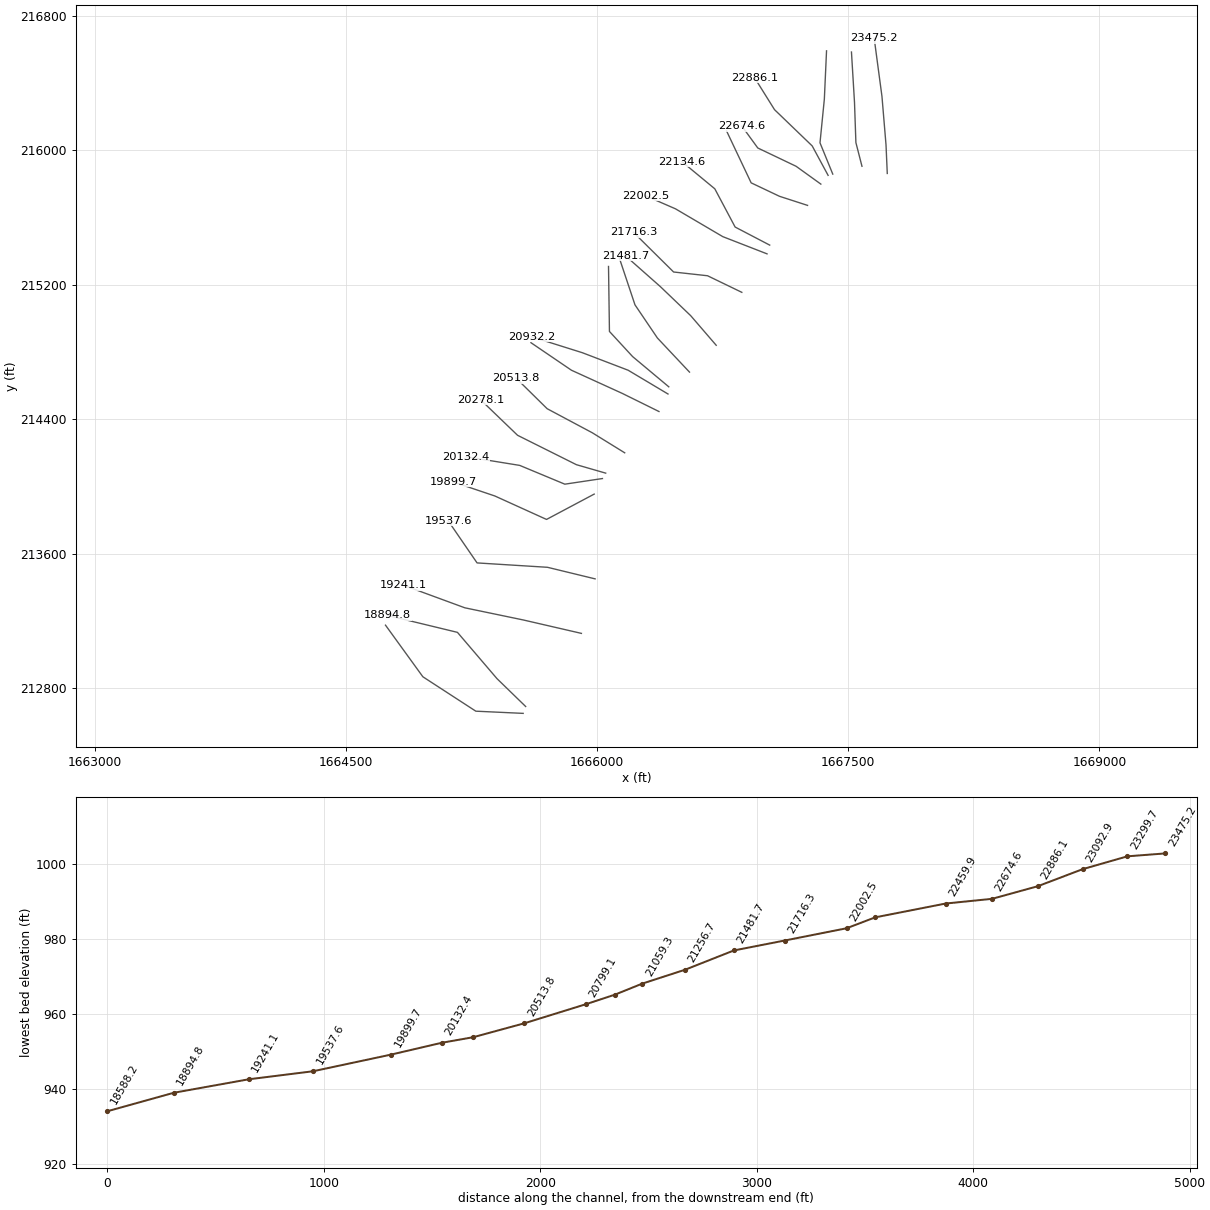
HEC-RAS study bchcrk.prj: bchcrk

--- bchcrk.g01 (geometry) --- (continued)

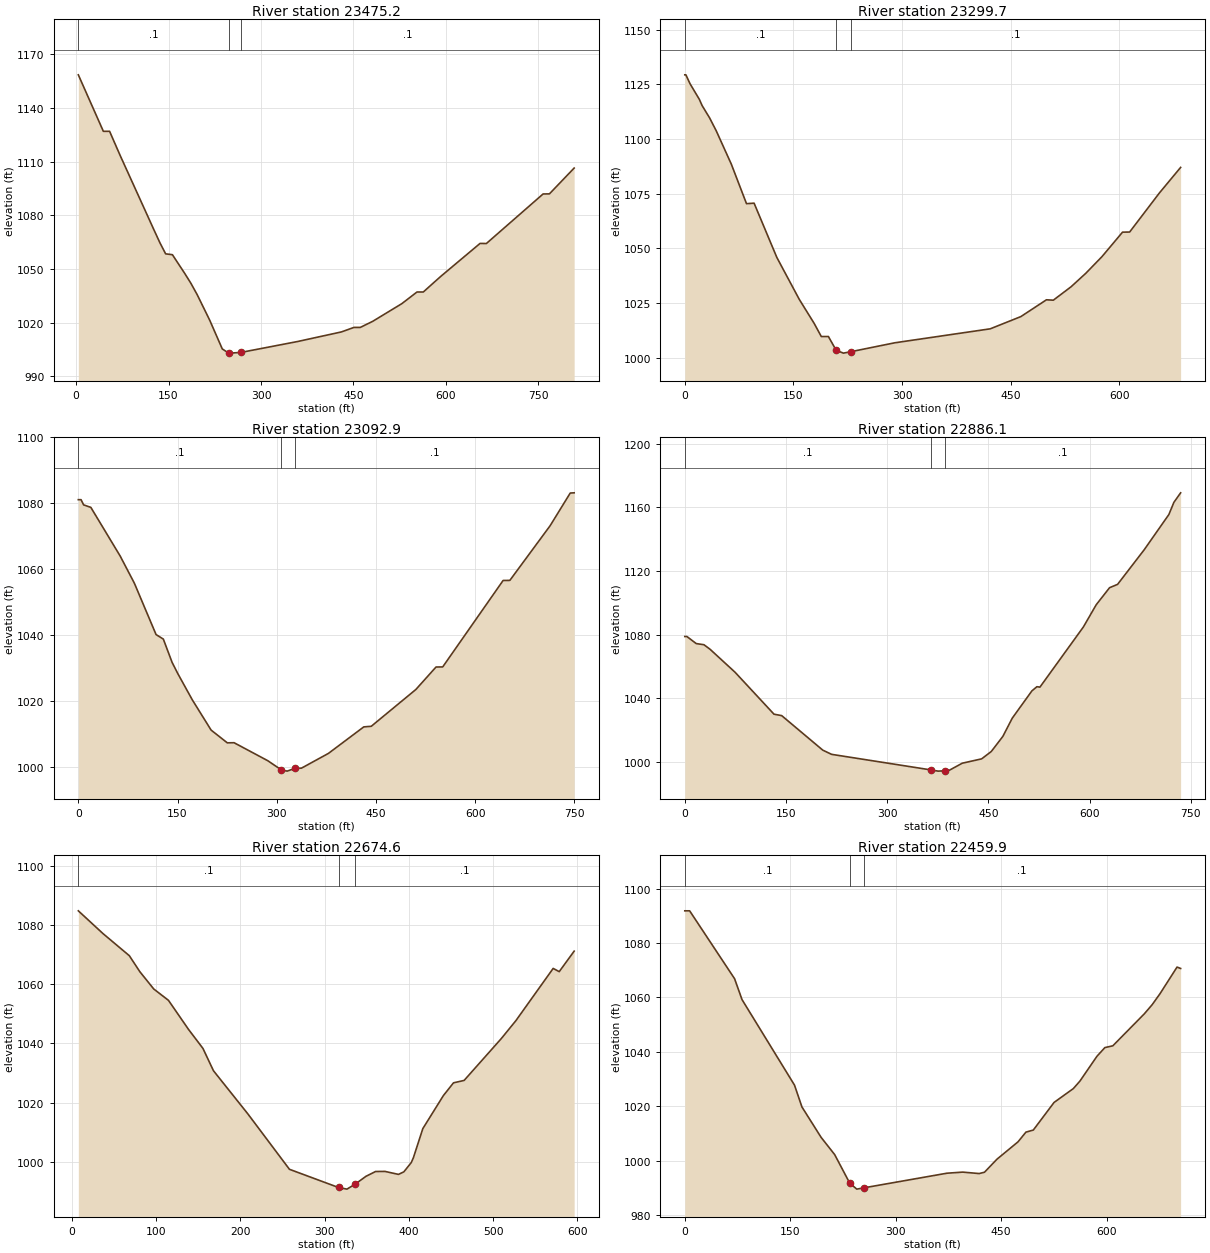
Type RM Length L Ch R = 1 ,23475.2 ,176.8,175.5,174.3
XS GIS Cut Line= 4
     1667732.492      215861.931     1667725.051      216031.213
     1667700.868       216319.55     1667654.362      216665.555
#Sta/Elev= 30
     3.7 1158.54    44.3 1126.96    54.4 1126.97    71.4 1113.57   125.8 1072.29
     136 1064.67   145.3 1058.46   156.3 1057.98   176.2 1047.56   186.3 1041.99
   196.5 1035.63   216.9 1021.29   237.2  1005.3   247.5 1002.99  250.02 1002.96
   267.5 1003.36   359.2 1009.44   430.4 1014.81   450.8 1017.34     461 1017.33
   481.4 1020.78   528.4 1030.62     553 1037.13   563.2 1037.13   591.5 1045.85
   655.3 1064.29   665.5 1064.23   757.5 1091.93   767.8 1091.99   807.9 1106.42
#Mann= 3 , 0 , 0
     3.7      .1       0   247.5    .045       0   267.5      .1       0
Bank Sta=247.5,267.5
XS Rating Curve= 0 ,0
Exp/Cntr=0.3,0.1

Type RM Length L Ch R = 1 ,23299.7 ,210.1,206.7,203.4
XS GIS Cut Line= 4
     1667581.385      215904.676      1667545.11      216045.589
     1667536.739       216285.56     1667518.602      216584.129
#Sta/Elev= 30
       0  1129.3     1.5  1129.3     7.2 1125.25    20.1 1118.09    23.9 1115.27
    34.2 1109.66    43.4 1103.74    64.3 1088.46    85.2 1070.45    95.7 1070.67
   127.1 1045.89   158.1 1026.73   178.7 1015.73   188.5 1009.76   198.3 1009.77
     209 1003.51     219 1002.18     229 1002.81     290  1006.9   421.8 1013.28
     464 1018.85   499.4 1026.54   508.9 1026.36   533.5 1032.51   553.8 1038.66
     576 1046.22   604.5 1057.44   614.3 1057.49   655.4 1075.34   684.7 1087.01
#Mann= 3 , 0 , 0
       0      .1       0     209    .045       0     229      .1       0
Bank Sta=209,229
XS Rating Curve= 0 ,0
Exp/Cntr=0.3,0.1

Type RM Length L Ch R = 1 ,23092.9 ,184,206.8,229.6
XS GIS Cut Line= 4
      1667406.95      215858.211      1667330.68      216044.235
     1667356.723      216304.669     1667369.745      216591.146
#Sta/Elev= 30
       0 1081.09     4.1 1081.09       8 1079.51    18.9 1078.76    63.3 1063.98
    84.7 1055.76   117.5 1040.18   128.5  1038.8   141.7 1031.76   150.4 1028.32
   172.3 1020.37   200.7  1011.2   225.2 1007.33   235.4 1007.37   286.3 1001.92
   306.9  999.12   315.7  998.75   326.9  999.56   337.3  999.65     378 1004.12
   431.5 1012.17   442.8 1012.35   510.2 1023.51   540.7 1030.33   550.8 1030.36
   642.1 1056.58   652.3 1056.61   713.2  1073.2   743.6 1083.11   749.5 1083.17
#Mann= 3 , 0 , 0
       0      .1       0   306.9    .045       0   326.9      .1       0
Bank Sta=306.9,326.9
XS Rating Curve= 0 ,0
Exp/Cntr=0.3,0.1

Type RM Length L Ch R = 1 ,22886.1 ,203.6,211.5,219.6
XS GIS Cut Line= 4
     1667379.046       215850.77     1667284.174      216025.632
     1667059.084       216241.42     1666940.029      216431.165
#Sta/Elev= 30
       0 1078.85     3.1 1078.85    16.9 1074.41    28.4 1073.67    37.4 1070.84
    74.5 1056.37   132.2    1030   143.6  1029.1   204.5 1007.39   217.6 1004.75
   365.4  994.92   375.4   994.2   385.4  994.42   392.4  994.83   411.2  999.18
   439.9 1001.91   454.2 1006.54   471.3 1015.99   485.3  1027.5   514.4 1044.66
   521.8 1047.28   526.3 1047.02   590.7 1084.85   609.7 1098.81   629.5 1109.53
   641.4 1111.64   680.7 1133.32   717.4 1155.55   724.8 1163.19   734.8 1169.19
#Mann= 3 , 0 , 0
       0      .1       0   365.4    .045       0   385.4      .1       0
Bank Sta=365.4,385.4
XS Rating Curve= 0 ,0
Exp/Cntr=0.3,0.1

Type RM Length L Ch R = 1 ,22674.6 ,214.7,214.7,214.5
XS GIS Cut Line= 4
     1667335.833      215798.642     1667187.944      215904.676
     1666959.134        216013.5     1666864.262      216143.252
#Sta/Elev= 30
       8 1084.71    37.1 1077.07    68.5 1069.57      81 1064.16    97.5 1058.33
   114.9 1054.52   138.7 1044.71   155.8  1038.3   168.3 1030.76     209 1016.24
   258.4  997.52   316.6  991.38   326.6  990.83   336.6  992.55   349.2  995.16
   360.5  996.77   371.7  996.81   387.7   995.8   394.1  996.66   402.9  999.79
   405.4  1001.4   416.6 1011.24     441 1022.39     453 1026.69   465.6  1027.5
   509.7 1041.62   526.9 1047.63   571.2 1065.28   578.4  1064.2   596.1 1071.11
#Mann= 3 , 0 , 0
       8      .1       0   316.6    .045       0   336.6      .1       0
#XS Ineff= 2 , 0
       0                     364       0
Permanent Ineff=
       F       F
Bank Sta=316.6,336.6
XS Rating Curve= 0 ,0
Exp/Cntr=0.3,0.1

Type RM Length L Ch R = 1 ,22459.9 ,341.4,325.2,309.2
XS GIS Cut Line= 4
      1667256.27      215672.187     1667088.848      215726.134
     1666919.566      215806.124     1666772.607      216114.924
#Sta/Elev= 30
       0 1091.81     6.9 1091.81    70.8 1066.87    81.4 1059.19     156 1027.78
   166.6 1019.75   193.9 1008.57   213.1 1002.27   234.6  991.75   244.6  989.57
   254.6  990.04   372.9  995.42   395.3  995.82   418.6  995.29   426.2  995.78
   443.9 1000.56   473.9 1006.95   485.1 1010.51   495.6 1011.27   525.1 1021.41
   552.5  1026.5   561.9 1029.26   586.1 1038.37   597.4 1041.57   608.7 1042.22
   653.5 1053.98   664.7 1057.35   675.9 1061.41     700 1071.14   705.1 1070.64
#Mann= 3 , 0 , 0
       0      .1       0   234.6    .045       0   254.6      .1       0
Bank Sta=234.6,254.6
XS Rating Curve= 0 ,0
Exp/Cntr=0.3,0.1

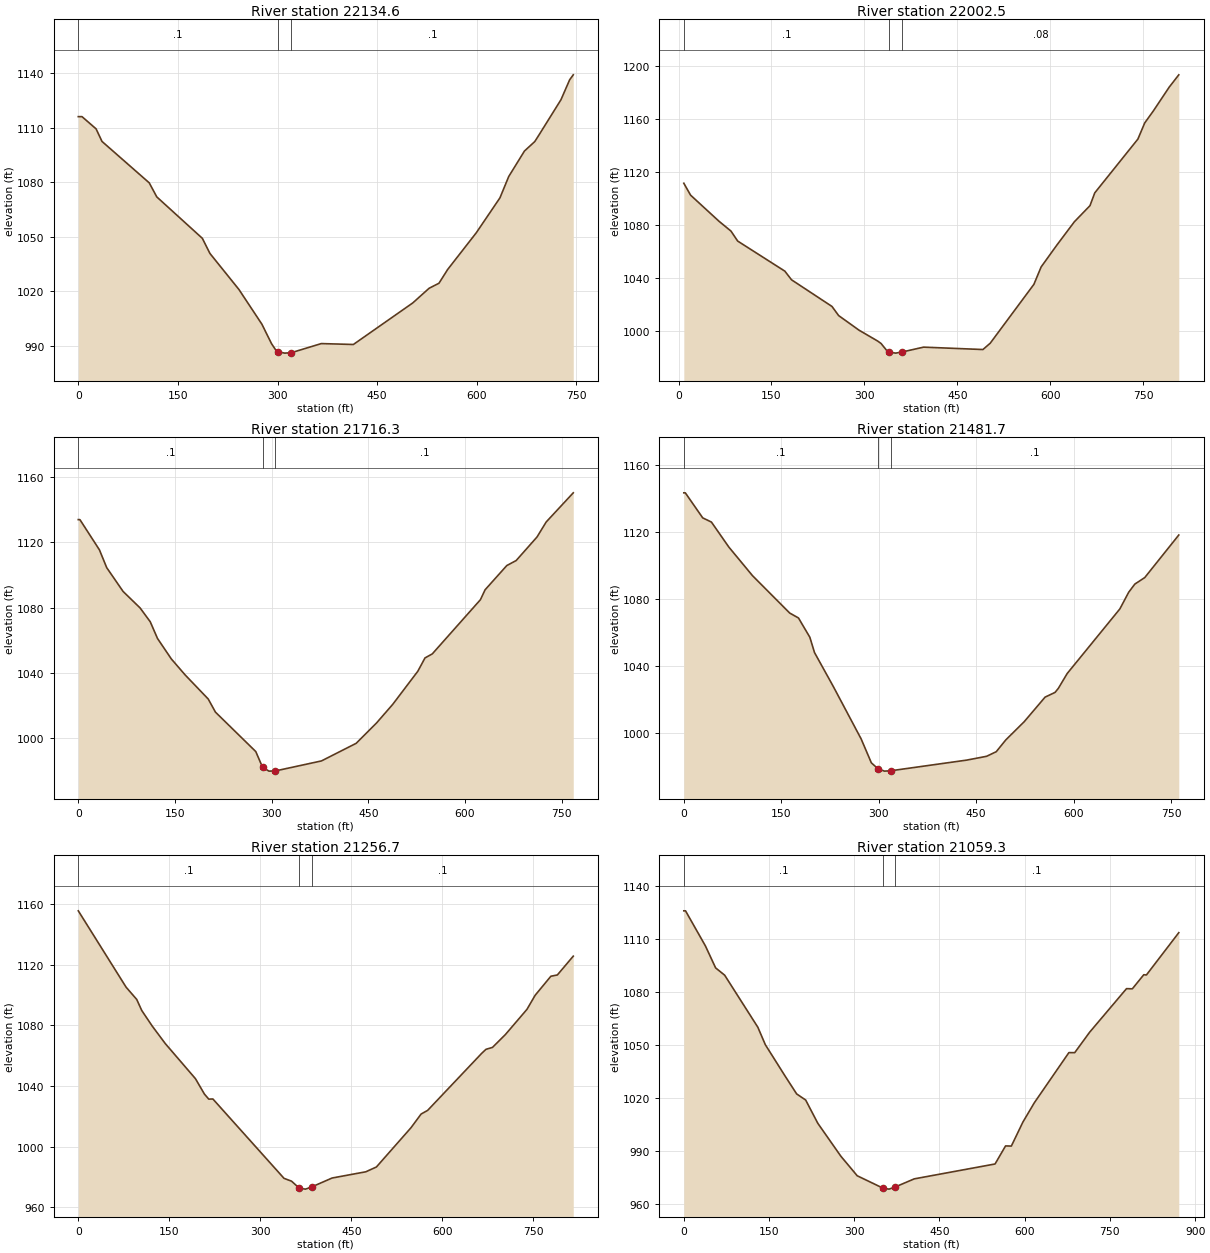
Type RM Length L Ch R = 1 ,22134.6 ,118.3,132.2,146
XS GIS Cut Line= 4
     1667030.288      215435.895     1666823.802      215543.324
     1666702.421      215770.739       1666505.7       215932.58
#Sta/Elev= 30
       0 1116.17     5.6 1116.17    26.8 1109.44    35.7 1102.51   106.8 1079.71
   118.2 1071.95   186.8 1049.13   198.2 1040.81   241.9 1020.94   276.4 1001.86
     291  991.08   298.5  986.95   300.8  986.62   310.8  985.88   320.8  986.12
   365.9  991.14   414.2  990.64   503.7 1013.55   528.2  1021.6   543.1 1024.39
   556.2 1031.97   599.2 1052.15   634.9 1071.42   648.1 1083.16   671.8 1097.22
   687.4 1102.46   694.8 1106.72   726.8  1125.5   739.9 1136.49   745.3 1139.21
#Mann= 3 , 0 , 0
       0      .1       0   300.8    .045       0   320.8      .1       0
Bank Sta=300.8,320.8
XS Rating Curve= 0 ,0
Exp/Cntr=0.3,0.1

Type RM Length L Ch R = 1 ,22002.5 ,275.7,286.2,296.7
XS GIS Cut Line= 4
     1667014.439      215383.849     1666750.284      215486.162
     1666467.528      215651.724     1666287.084      215729.854
#Sta/Elev= 30
     8.5 1111.18    19.4 1102.21    65.2 1082.54    84.6 1075.09    95.5 1067.53
   171.6 1044.84   182.4 1038.31   247.7  1018.2   258.5 1011.29   291.4 1000.28
   321.5  992.07     327  990.21   336.3  984.85   340.5  983.72   350.5  982.97
   360.5  983.78   395.6  987.49   491.4  985.68   503.2  990.47   573.7 1034.89
   585.4 1048.04   610.9 1064.59     639 1082.09   664.2 1094.25     672 1103.95
   741.6 1144.52   752.6 1156.69   766.6  1165.8   792.1 1183.68   807.6    1193
#Mann= 3 , 0 , 0
     8.5      .1       0   340.5    .045       0   360.5     .08       0
#XS Ineff= 2 , 0
       0                     480       0
Permanent Ineff=
       F       F
Bank Sta=340.5,360.5
XS Rating Curve= 0 ,0
Exp/Cntr=0.3,0.1

Type RM Length L Ch R = 1 ,21716.3 ,250.9,234.6,218.3
XS GIS Cut Line= 4
     1666863.759       215155.04     1666659.133      215253.632
     1666456.366      215275.955     1666216.395      215512.206
#Sta/Elev= 30
       0 1133.93     2.5 1133.93    32.8  1115.4    44.1 1104.47    69.5 1089.88
    95.9 1079.76   111.6 1071.31   122.9 1061.04   144.4 1048.47   165.9 1038.63
   201.6 1023.91   212.8 1015.87   275.4  991.67   285.8  982.09   295.8  979.69
   305.8  979.81   377.3  985.95   431.1  996.74   462.6 1009.18   487.8 1020.62
   526.8 1040.97   537.9 1049.12   549.2 1051.58   623.9 1084.83   631.1 1090.89
   664.8 1105.76   679.3 1108.82   711.7 1123.29   725.9 1132.48   767.9 1150.36
#Mann= 3 , 0 , 0
       0      .1       0   285.8    .045       0   305.8      .1       0
Bank Sta=285.8,305.8
XS Rating Curve= 0 ,0
Exp/Cntr=0.3,0.1

Type RM Length L Ch R = 1 ,21481.7 ,230.7,225,219.4
XS GIS Cut Line= 4
     1666710.792      214840.153     1666558.717      215015.946
     1666377.344      215188.948     1666168.067      215373.112
#Sta/Elev= 30
       0 1143.16     2.3 1143.16    29.1 1128.21    42.5 1125.71    69.3 1110.79
   105.8 1093.68   163.1 1071.37   176.5 1068.46     194 1056.95   201.2  1047.8
   230.1 1027.56     273  996.23   288.7  981.97   298.8   978.5   308.8  977.04
   318.8  977.27   435.5  983.62     466  985.88   480.9  988.63   495.6  995.66
   523.9 1006.52   556.1 1021.21   571.5 1024.05   576.6  1026.5   590.1 1035.29
   671.2 1073.86   684.7 1083.75   694.2 1088.67   709.5 1092.57   761.9 1117.98
#Mann= 3 , 0 , 0
       0      .1       0   298.8    .045       0   318.8      .1       0
Bank Sta=298.8,318.8
XS Rating Curve= 0 ,0
Exp/Cntr=0.3,0.1

Type RM Length L Ch R = 1 ,21256.7 ,193.6,197.3,201.1
XS GIS Cut Line= 4
     1666551.239      214680.678     1666359.634      214883.444
     1666225.696       215080.63     1666130.824      215363.387
#Sta/Elev= 30
       0 1155.67    78.8 1105.24    96.3 1097.16   104.6 1089.85   121.8 1079.59
   143.3 1068.03   193.1 1044.81   207.9 1034.63     215 1031.33   221.8 1031.42
     339  979.02   351.3  977.17   364.4  972.47   374.4   971.9   384.4  973.31
   418.2  979.23   473.8  983.35   491.2  986.51   548.2 1012.43   564.9 1021.49
   575.6 1023.87   664.7 1061.55   671.8 1064.23   682.5 1065.48   703.9 1074.03
   739.3  1090.6   752.8 1099.91   778.7 1112.47   789.4 1113.32   815.6 1125.73
#Mann= 3 , 0 , 0
       0      .1       0   364.4    .045       0   384.4      .1       0
Bank Sta=364.4,384.4
XS Rating Curve= 0 ,0
Exp/Cntr=0.3,0.1

Type RM Length L Ch R = 1 ,21059.3 ,115.3,127.1,138.7
XS GIS Cut Line= 4
      1666427.57      214593.206     1666211.317      214773.184
     1666073.194      214922.469     1666067.614      215308.934
#Sta/Elev= 30
       0 1126.02       3 1126.02      38 1106.13      56 1093.65    71.9 1089.53
   130.3 1060.01   143.5 1050.09   178.3 1032.31   198.6 1022.19   214.5 1018.72
   235.8 1005.56   276.5  986.83   305.2  975.78   351.2  968.66   361.2   968.2
   371.2   969.3   405.6  974.02   547.8  982.46   566.3   992.7   576.5  992.62
   596.8 1006.21     617 1017.21   677.8 1045.63     688 1045.58   714.3 1057.18
   779.2 1081.89   789.4 1081.78   809.6 1089.79   814.2 1089.64   871.2 1113.63
#Mann= 3 , 0 , 0
       0      .1       0   351.2    .045       0   371.2      .1       0
Bank Sta=351.2,371.2
XS Rating Curve= 0 ,0
Exp/Cntr=0.3,0.1

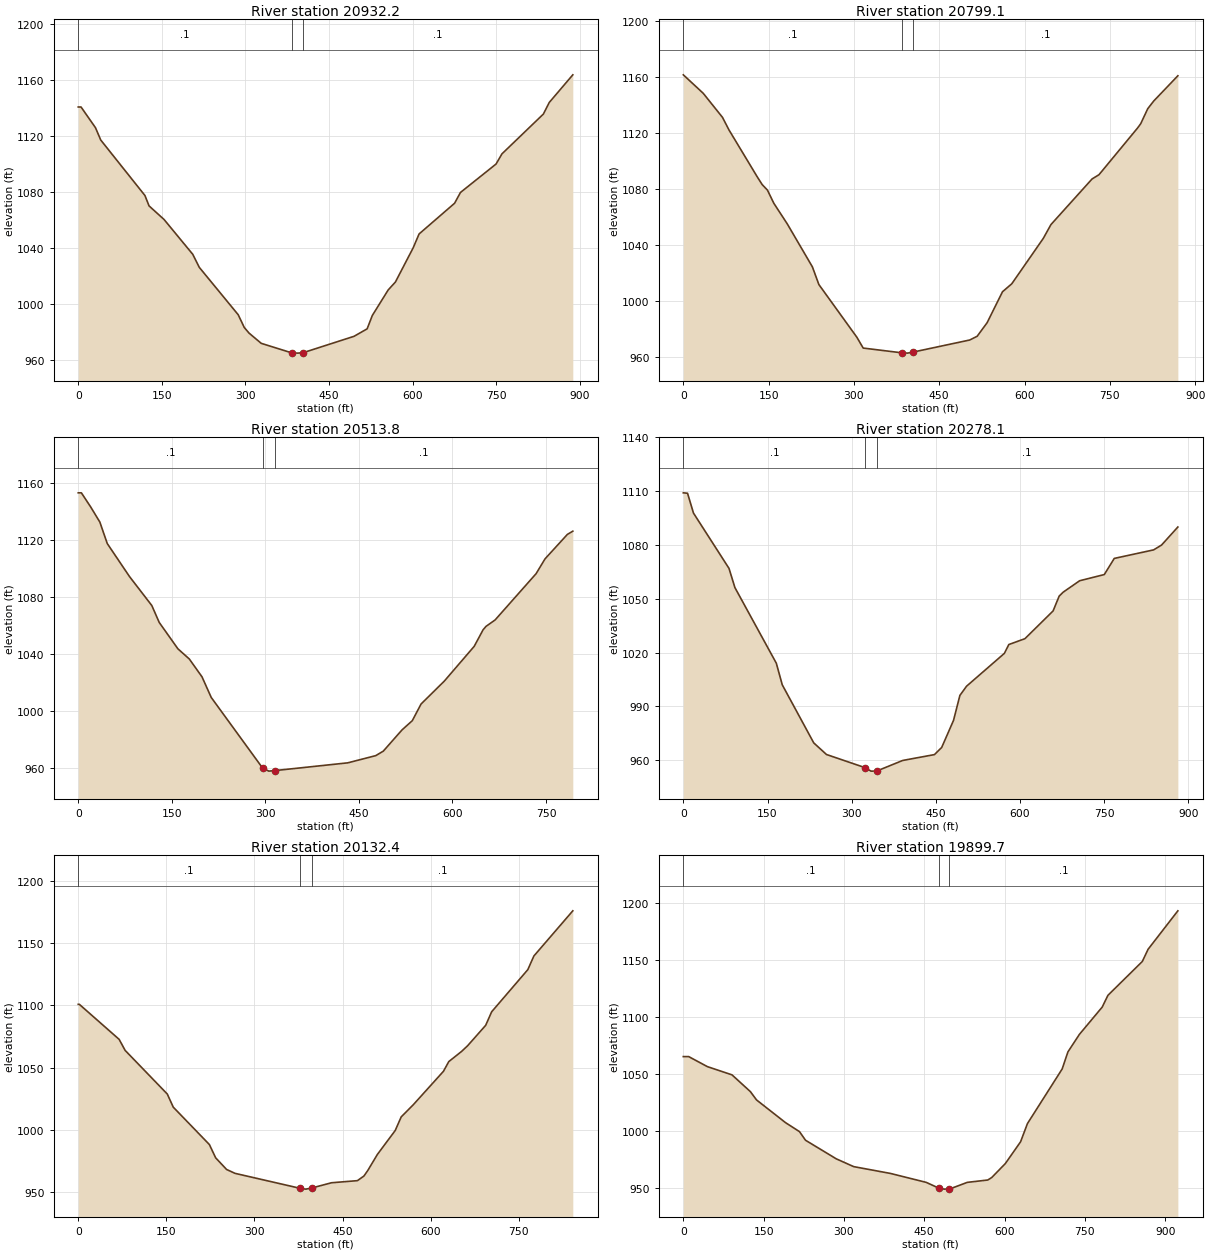
Type RM Length L Ch R = 1 ,20932.2 ,134.9,133.1,131.5
XS GIS Cut Line= 4
     1666422.882      214550.461     1666184.771       214691.84
     1665911.316      214796.013     1665608.096      214890.885
#Sta/Elev= 30
       0 1141.02       5 1141.02    30.9 1126.23    40.3 1117.45   119.6 1077.82
     127 1070.39   153.9 1060.69   205.4 1035.83   217.1 1026.51     287  992.64
   297.8  983.59   306.3  979.58   328.3  972.22   382.6  965.48   392.6  965.24
   402.6  965.44   494.8  977.25   518.3  982.59   527.6  992.14   556.1 1010.38
     569 1016.01   600.9 1040.46   611.5 1050.35   675.2 1072.29   685.8 1080.01
   749.6  1100.3   760.2 1107.56   834.5 1135.99   845.1 1144.29   887.3    1164
#Mann= 3 , 0 , 0
       0      .1       0   382.6    .045       0   402.6      .1       0
Bank Sta=382.6,402.6
XS Rating Curve= 0 ,0
Exp/Cntr=0.3,0.1

Type RM Length L Ch R = 1 ,20799.1 ,286.8,285.3,283.8
XS GIS Cut Line= 4
     1666368.935      214446.288     1666149.426      214554.182
     1665846.207       214691.84     1665604.376      214855.541
#Sta/Elev= 30
       0 1161.28      35  1148.1    68.9 1130.91    80.2 1122.02   129.7 1088.68
   138.6 1082.99   147.9 1079.03   159.2 1069.59   182.7 1054.97     227 1024.23
   238.3 1011.67   305.2  974.01   316.3  966.31   384.2  962.92   394.2   962.7
   404.2  963.46   503.6  972.06   516.7  974.73   534.2  984.41   561.2 1006.47
   577.6  1012.2     633 1044.59   646.4 1054.41   718.7 1086.96   730.9    1090
     799 1123.45   804.3 1126.42   816.6 1137.08   827.2 1142.61   869.6  1160.6
#Mann= 3 , 0 , 0
       0      .1       0   384.2    .045       0   404.2      .1       0
Bank Sta=384.2,404.2
XS Rating Curve= 0 ,0
Exp/Cntr=0.3,0.1

Type RM Length L Ch R = 1 ,20513.8 ,235,235.7,236.4
XS GIS Cut Line= 4
     1666164.308      214200.736     1665970.843      214319.791
     1665701.108       214463.03     1665515.084      214645.334
#Sta/Elev= 30
       0 1153.23       5 1153.23    20.2  1143.1    34.6 1132.68    46.5 1117.57
    82.2 1094.34   117.9 1074.03   129.8 1062.13   159.7 1043.62   178.1  1036.4
   198.4 1023.89   213.2 1009.39   295.5  959.79   305.5  957.59   315.5  957.98
   432.1  963.41     477  968.48   489.1  971.63   519.2  986.59   535.6  993.04
   549.7 1004.78     587  1020.9   634.9 1045.32   649.1 1056.92   653.9 1059.37
   668.4 1063.86   734.2 1096.43   748.4 1106.78   784.3    1124     793 1126.27
#Mann= 3 , 0 , 0
       0      .1       0   295.5    .045       0   315.5      .1       0
Bank Sta=295.5,315.5
XS Rating Curve= 0 ,0
Exp/Cntr=0.3,0.1

Type RM Length L Ch R = 1 ,20278.1 ,144,145.7,147.4
XS GIS Cut Line= 4
     1666050.834       214079.82     1665875.971      214130.047
     1665524.385      214304.909     1665303.017      214516.977
#Sta/Elev= 30
       0 1109.08     7.5 1108.85    18.1 1097.78    81.4 1066.94    91.9 1056.25
   165.7 1014.06   176.3 1002.01   232.4  969.63   255.1  963.15   324.3  955.77
   334.3  953.88   344.3  953.89   390.9  959.83   447.5   963.1   460.4  967.09
   481.5  982.21   492.8   996.1   504.7 1001.24   572.1 1019.56     580 1024.48
   608.7 1027.74   658.9 1043.22   669.7 1051.47   676.9 1053.69   706.2 1060.05
   750.1  1063.5   767.9  1072.5     838 1077.26   852.2 1079.97   881.2 1090.02
#Mann= 3 , 0 , 0
       0      .1       0   324.3    .045       0   344.3      .1       0
Bank Sta=324.3,344.3
XS Rating Curve= 0 ,0
Exp/Cntr=0.3,0.1

Type RM Length L Ch R = 1 ,20132.4 ,233.5,232.7,231.9
XS GIS Cut Line= 4
     1666031.339       214047.69     1665806.715      214014.206
     1665537.445       214125.82     1665217.948      214177.442
#Sta/Elev= 30
       0 1100.84     1.8 1100.84    69.6  1072.7    79.8 1063.84   151.6 1028.78
   161.8 1018.23   223.3   988.2     234  977.52   252.6  968.18   266.9  965.07
   377.6  953.06   387.6  952.39   397.6  953.29   431.2   957.5   475.4   959.2
   486.4  962.88   493.1  967.39   509.3  980.19   539.8   999.5     550 1010.43
   570.6 1020.21   621.9 1047.03     631 1054.84   652.7 1062.97     663 1067.54
   693.8 1083.95     704 1094.84   765.6  1128.7   775.9 1139.65   842.2 1175.94
#Mann= 3 , 0 , 0
       0      .1       0   377.6    .045       0   397.6      .1       0
Bank Sta=377.6,397.6
XS Rating Curve= 0 ,0
Exp/Cntr=0.3,0.1

Type RM Length L Ch R = 1 ,19899.7 ,353.1,362.2,371.2
XS GIS Cut Line= 4
     1665982.005      213955.184     1665697.388      213804.505
     1665388.588      213944.023     1665139.316      214027.733
#Sta/Elev= 30
       0 1065.38      10 1065.38      45 1056.57    90.9 1049.37   125.3 1034.67
   136.7 1027.43   190.8 1007.54     217  999.62   228.3  992.07   285.8  975.77
   318.2  968.97     387  962.99   453.8  955.16   477.1  950.15   487.1  949.25
   497.1  949.29   530.4  955.17   568.7  957.24   576.1   959.4   601.5  971.64
     630  990.73   642.8 1006.67   707.7 1054.55   718.4 1069.45   739.8 1084.78
   782.5 1108.77   793.2 1119.08   857.4 1148.71   868.1 1159.34   923.8 1193.09
#Mann= 3 , 0 , 0
       0      .1       0   477.1    .045       0   497.1      .1       0
Bank Sta=477.1,497.1
XS Rating Curve= 0 ,0
Exp/Cntr=0.3,0.1

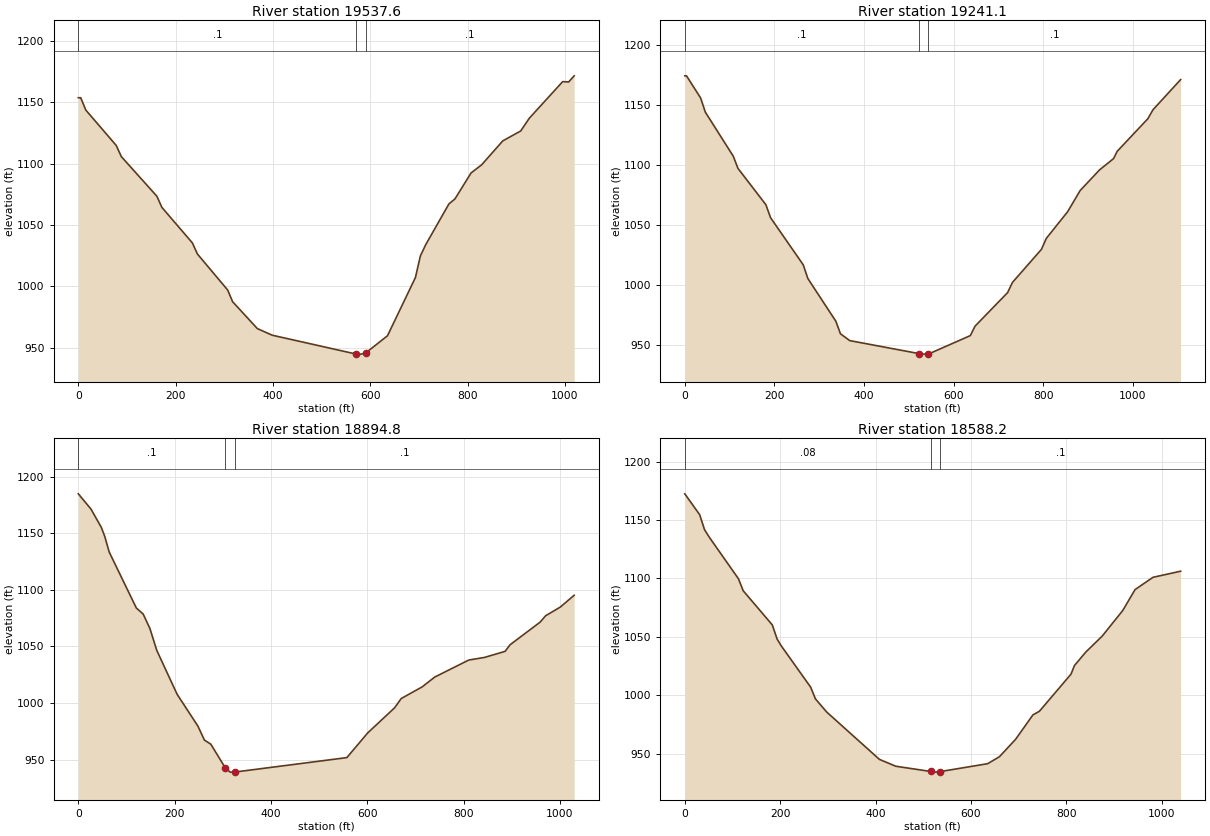
Type RM Length L Ch R = 1 ,19537.6 ,300.2,296.5,292.9
XS GIS Cut Line= 4
     1665987.585      213451.059     1665702.969      213519.888
     1665282.554      213545.931     1665109.552      213797.064
#Sta/Elev= 30
       0 1153.55     4.9 1153.55    15.4  1143.5    77.9  1114.7    88.4  1105.6
   161.4 1073.37   171.8 1064.23   234.4 1035.35   244.8 1026.28     307  996.95
   317.1  987.45   367.9  965.58   398.4  960.19   571.2  944.81   581.2  944.78
   591.2  945.92   635.4  959.74   692.8 1007.17     703 1024.77     714 1033.94
   761.6 1067.09   773.9 1071.09   807.2 1092.34     829 1098.99   872.4 1118.44
   909.1 1126.49   926.9  1136.9   995.4 1166.66  1007.7  1166.4    1019 1171.39
#Mann= 3 , 0 , 0
       0      .1       0   571.2    .045       0   591.2      .1       0
Bank Sta=571.2,591.2
XS Rating Curve= 0 ,0
Exp/Cntr=0.3,0.1

Type RM Length L Ch R = 1 ,19241.1 ,362.8,346.3,329.6
XS GIS Cut Line= 4
     1665905.773      213126.871     1665559.768      213206.396
     1665209.577      213278.946     1664839.855      213414.278
#Sta/Elev= 30
       0 1174.14     3.8 1174.14    35.4 1155.66    45.8 1143.94   108.2 1107.26
   118.6 1097.18     181  1066.9   191.4 1056.11   264.2    1017   274.6 1005.54
     337  970.04   347.4  959.55   368.1  953.88   523.7  943.01   533.7  942.64
   543.7  942.72   637.2  958.06   647.6  965.88   720.4  993.85   731.2 1002.31
   795.9 1029.83   806.7 1038.94   854.2 1061.05   882.3 1078.78   925.4 1095.86
   956.9 1105.34   964.8 1111.33  1033.4  1138.5  1044.8 1145.95  1106.4    1171
#Mann= 3 , 0 , 0
       0      .1       0   523.7    .045       0   543.7      .1       0
Bank Sta=523.7,543.7
XS Rating Curve= 0 ,0
Exp/Cntr=0.3,0.1

Type RM Length L Ch R = 1 ,18894.8 ,298.2,306.6,315.1
XS GIS Cut Line= 4
     1665572.752       212692.08      1665401.61      212857.642
     1665165.359      213132.958     1664748.665      213233.411
#Sta/Elev= 30
       0 1184.78    26.2 1171.35    47.7  1155.2    54.8 1147.25    64.1 1133.39
   120.5 1083.93   134.6 1078.68   148.7 1065.78   162.8 1046.62   205.1 1007.79
   248.4  979.59   261.8  967.35   275.1  963.72   305.2  942.78   315.2  939.04
   325.2  939.12   557.5  951.86   600.9  973.68   656.7  995.85   670.4 1004.02
   713.7 1014.25   740.1 1022.99   810.6    1038   843.4 1040.32   886.1 1045.69
   896.5 1051.51   959.1 1071.58   970.2 1077.11  1000.8 1084.81  1029.5 1095.22
#Mann= 3 , 0 , 0
       0      .1       0   305.2    .045       0   325.2      .1       0
Bank Sta=305.2,325.2
XS Rating Curve= 0 ,0
Exp/Cntr=0.3,0.1

Type RM Length L Ch R = 1 ,18588.2 ,291.8,308.2,324.5
XS GIS Cut Line= 4
      1665557.87      212651.155     1665275.113      212664.177
     1664958.872      212868.803     1664735.643      213175.743
#Sta/Elev= 30
       0 1172.51    31.2 1154.62    41.4 1141.78    51.5 1135.24   112.4  1099.8
   122.5 1089.45   183.4 1060.23   193.6 1048.04   201.4 1042.74     264 1006.77
   273.7  996.94   297.3  985.64   407.9  945.04   442.2  939.16   515.2  934.69
   525.2  934.11   535.2  934.56   634.9  941.34   659.5  947.31   693.5  962.27
   729.7  983.13   743.3  986.24   809.6 1018.08   816.8 1025.44   840.5 1036.95
   874.9 1050.62   917.9 1072.51   943.8 1090.47   981.4    1101  1039.3 1106.22
#Mann= 3 , 0 , 0
       0     .08       0   515.2    .045       0   535.2      .1       0
Bank Sta=515.2,535.2
XS Rating Curve= 0 ,0
Exp/Cntr=0.3,0.1