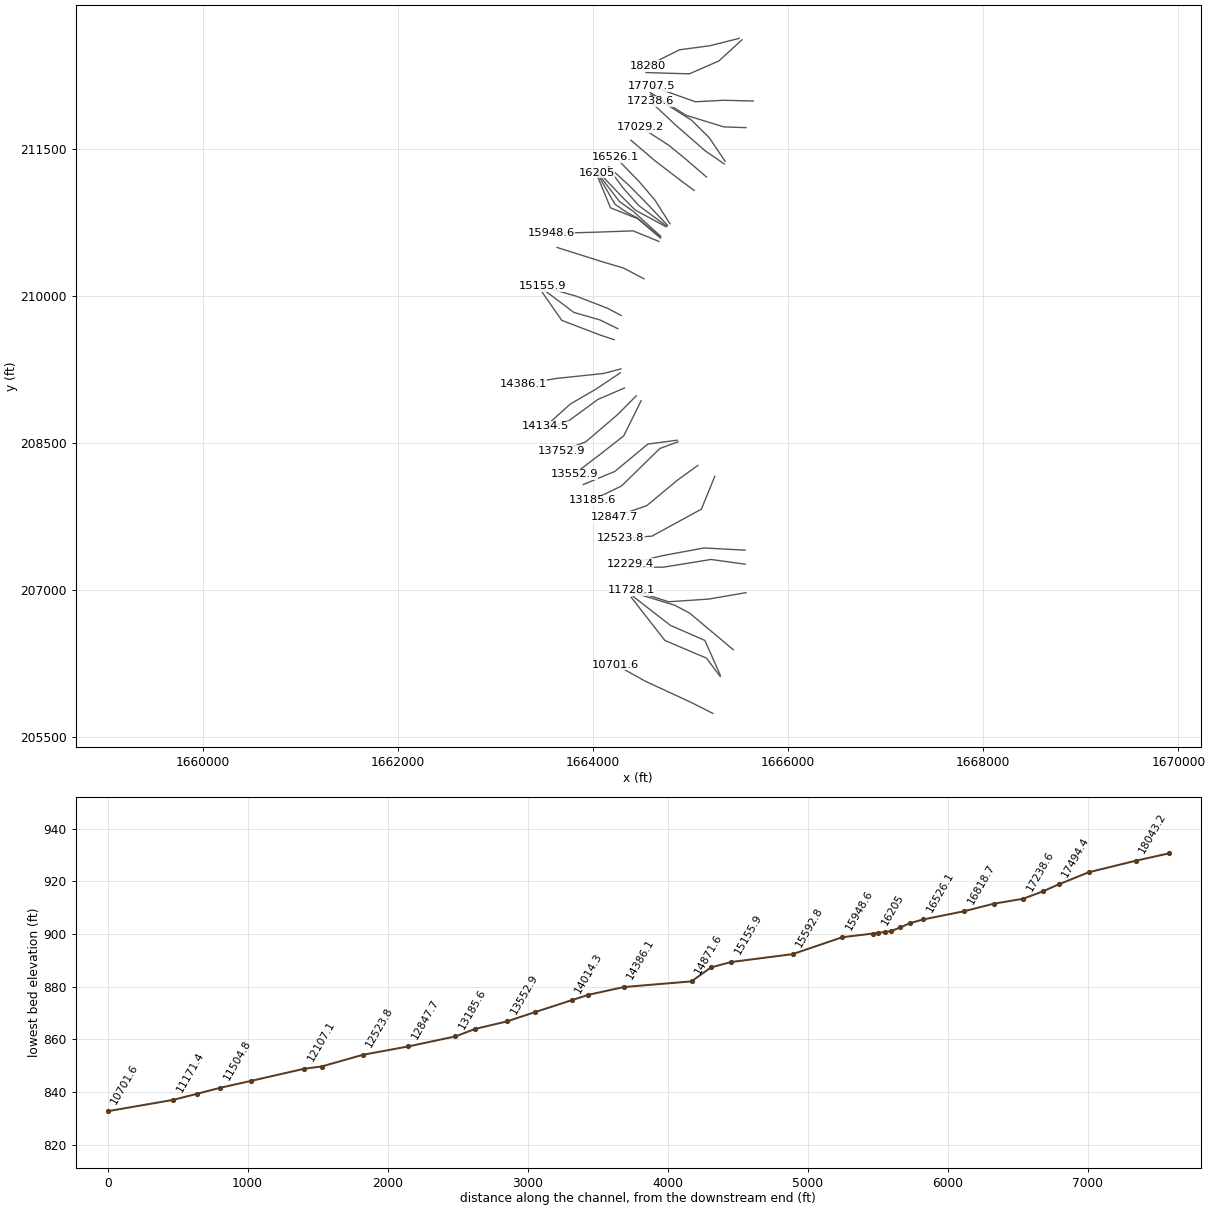
HEC-RAS study bchcrk.prj: bchcrk

--- bchcrk.g01 (geometry) --- (continued)

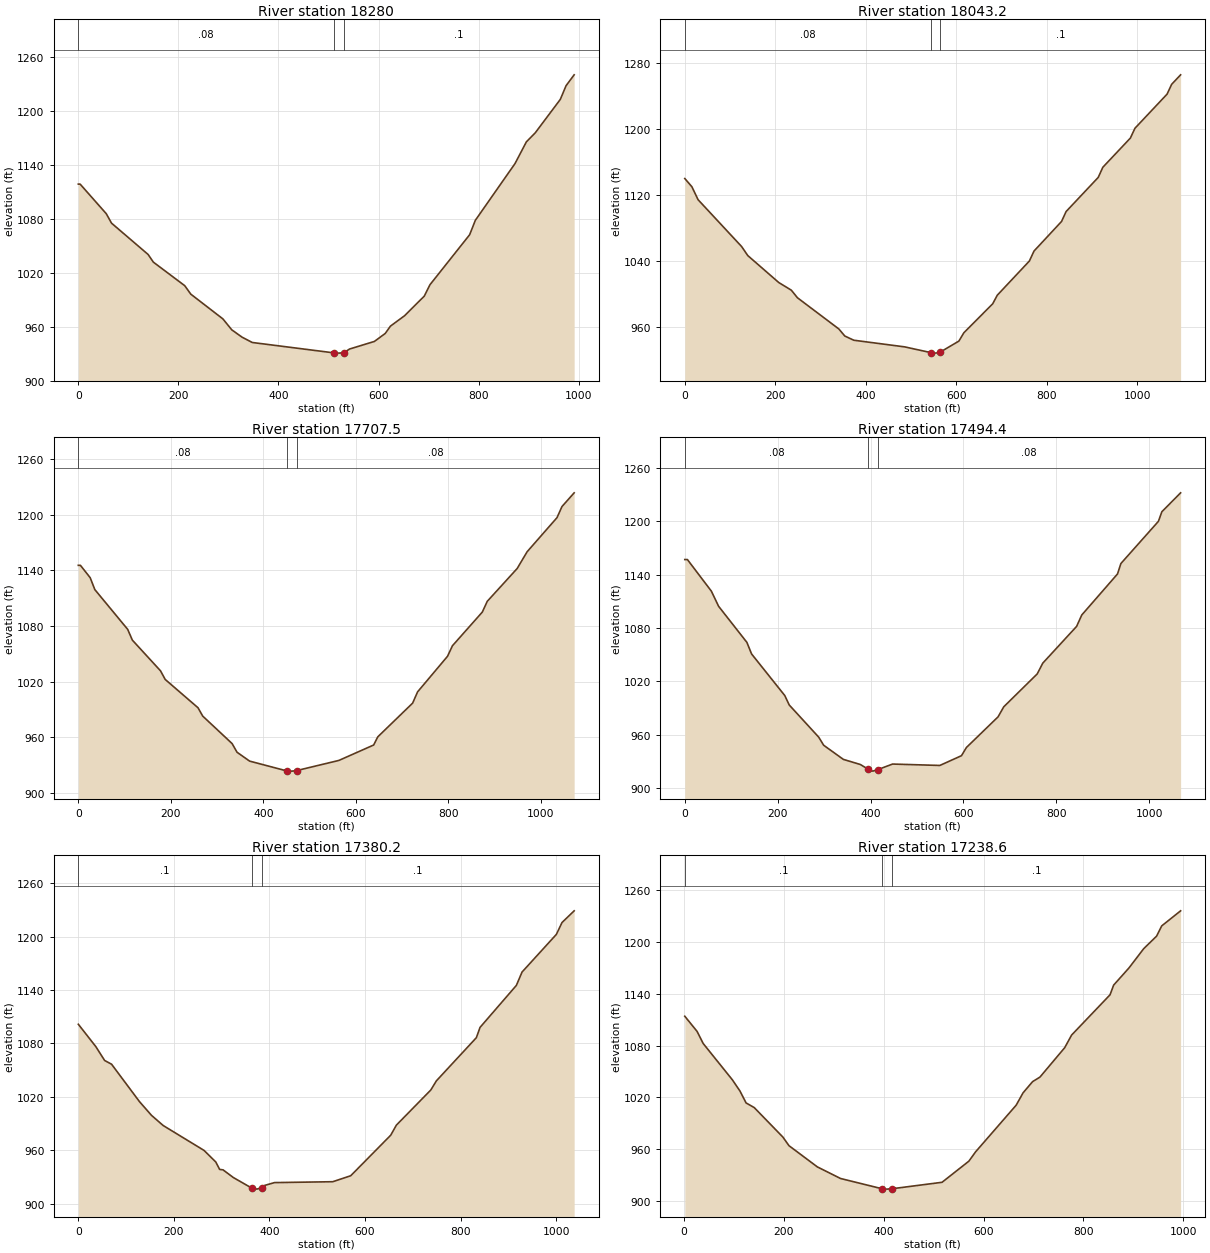
Type RM Length L Ch R = 1 ,18280   ,229.8,236.8,243.8
XS GIS Cut Line= 4
     1665499.775      212624.606     1665199.811      212549.266
     1664885.895      212507.411     1664559.423      212344.174
#Sta/Elev= 30
       0 1118.44     3.6 1118.44    55.9 1085.52    66.3  1075.1   139.5 1040.24
   149.9 1031.77   212.6 1005.59   224.8  996.15   288.9  968.67   306.7   956.5
   327.2  948.36   347.6  942.44     511  930.88     521  930.61     531  931.15
   541.9  935.13   591.8  943.61   613.5  952.52   623.7  960.56   652.1   972.2
   691.5  994.01   702.8 1006.61   782.1 1062.18   793.5 1078.22   872.8 1141.28
   895.5  1165.4   913.3 1175.48   963.4 1212.66   974.8  1227.8     991  1239.9
#Mann= 3 , 0 , 0
       0     .08       0     511    .045       0     531      .1       0
Bank Sta=511,531
XS Rating Curve= 0 ,0
Exp/Cntr=0.3,0.1

Type RM Length L Ch R = 1 ,18043.2 ,344.7,335.7,326.7
XS GIS Cut Line= 4
     1665528.106       212610.23     1665291.855      212394.442
     1664988.636      212262.365     1664544.038      212275.386
#Sta/Elev= 30
       0 1139.48    15.7  1129.5    29.4 1113.78   125.5 1057.06   139.2 1046.07
   207.7 1013.37   235.3 1004.16     249   994.9   340.2  957.19   353.6  948.54
   373.4  943.46   485.7  935.41   543.8  928.42   553.8  927.82   563.8  928.89
   605.6  942.41   616.6  952.51   680.3  987.64   690.4  998.01   761.4 1039.52
   771.5 1051.51   832.4 1087.43   842.5 1099.48   913.5 1140.87   923.6 1153.11
   984.5 1188.55   994.6 1200.43  1065.6 1241.83  1075.7 1253.73  1095.5 1265.21
#Mann= 3 , 0 , 0
       0     .08       0   543.8    .045       0   563.8      .1       0
Bank Sta=543.8,563.8
XS Rating Curve= 0 ,0
Exp/Cntr=0.3,0.1

Type RM Length L Ch R = 1 ,17707.5 ,221.9,213.2,204.4
XS GIS Cut Line= 4
     1665643.441      211985.189     1665340.222       211992.63
     1665048.164      211977.748     1664599.846      212137.728
#Sta/Elev= 30
       0 1145.46     4.5 1145.46    25.6 1132.13    35.7 1119.26   106.7 1076.37
   116.8 1064.76   177.6 1031.68   187.8 1022.36   258.7  991.81   268.9  982.81
   332.4  953.16   343.1   943.8   370.3  934.24   451.7  923.52   461.7  923.44
   471.7     924   563.2  934.98   638.4  951.61   647.3  960.41   722.6  996.77
   733.4 1008.97     798 1047.29   808.7 1058.68   873.3 1095.05     884 1106.64
   948.6    1142   970.1 1160.08  1034.7 1196.88  1045.5 1208.88  1071.8 1223.67
#Mann= 3 , 0 , 0
       0     .08       0   451.7    .045       0   471.7     .08       0
Bank Sta=451.7,471.7
XS Rating Curve= 0 ,0
Exp/Cntr=0.3,0.1

Type RM Length L Ch R = 1 ,17494.4 ,126.3,114.2,102.1
XS GIS Cut Line= 4
     1665569.031      211713.593     1665342.082      211721.035
     1664953.291       211840.09     1664586.824       212072.62
#Sta/Elev= 30
       0 1157.06     5.6 1157.06    57.2 1121.48    72.8 1104.43   133.7 1063.82
   143.8  1050.8   215.3 1003.96   224.9  993.32   288.4   957.1     299  948.03
   341.4  932.09     378  926.34     395  920.98     405  918.87     415  920.46
   447.4  926.83   549.2  925.26   595.8  936.24   606.4  945.45   674.6  979.98
   686.9  991.31   758.9 1028.31   770.9 1040.43   843.7 1081.78   854.9 1094.68
   931.8 1140.83   939.1 1152.58  1019.9 1200.08  1027.3 1210.87  1067.7 1232.16
#Mann= 3 , 0 , 0
       0     .08       0     395    .045       0     415     .08       0
Bank Sta=395,415
XS Rating Curve= 0 ,0
Exp/Cntr=0.3,0.1

Type RM Length L Ch R = 1 ,17380.2 ,139.1,141.6,144.1
XS GIS Cut Line= 4
     1665354.676      211370.338      1665191.44      211611.705
     1665010.066      211790.288     1664592.907      212051.187
#Sta/Elev= 30
       0 1101.51    36.7 1076.34      55 1060.83    69.6 1056.59     128 1014.54
   153.1  999.15   177.5  987.74   263.2  959.68   287.7  946.71   295.8  938.35
     303  937.83   324.5   929.2   363.7  917.15   373.7  916.18   383.7  917.69
   389.9  920.32   410.5  923.51   532.6  924.51   570.2  931.23   653.9  976.79
   665.8  988.14   737.9 1027.65   749.5  1037.9   833.2 1086.43   840.9 1097.99
   916.9 1145.16   928.8 1160.18  1000.6  1202.5  1012.5 1215.86  1037.9 1229.02
#Mann= 3 , 0 , 0
       0      .1       0   363.7    .045       0   383.7      .1       0
Bank Sta=363.7,383.7
XS Rating Curve= 0 ,0
Exp/Cntr=0.3,0.1

Type RM Length L Ch R = 1 ,17238.6 ,209.4,209.4,209.4
XS GIS Cut Line= 4
     1665345.802      211343.406     1665152.337      211475.483
     1664843.537      211743.357     1664586.824      211983.329
#Sta/Elev= 30
     1.9 1113.99    26.5 1096.39    38.7 1082.38    97.2 1040.17   112.4 1027.16
   124.6  1013.4   140.9    1008   198.3  973.75   210.5  963.77   267.3  939.16
   313.7  925.71   396.5  913.86   406.5  913.38   416.5   913.8   516.9  921.31
   570.6  945.82     584  956.61   665.3  1010.8   679.1 1025.11   698.1 1038.08
   712.9 1043.37   762.4 1077.47   776.3 1092.17   853.2 1138.87   860.4 1150.08
     891 1169.96   920.7 1192.45   946.4 1206.92   956.6 1218.79   994.5  1236.3
#Mann= 3 , 0 , 0
     1.9      .1       0   396.5    .045       0   416.5      .1       0
#XS Ineff= 2 , 0
       0     360             500       0
Permanent Ineff=
       F       F
Bank Sta=396.5,416.5
XS Rating Curve= 0 ,0
Exp/Cntr=0.3,0.1

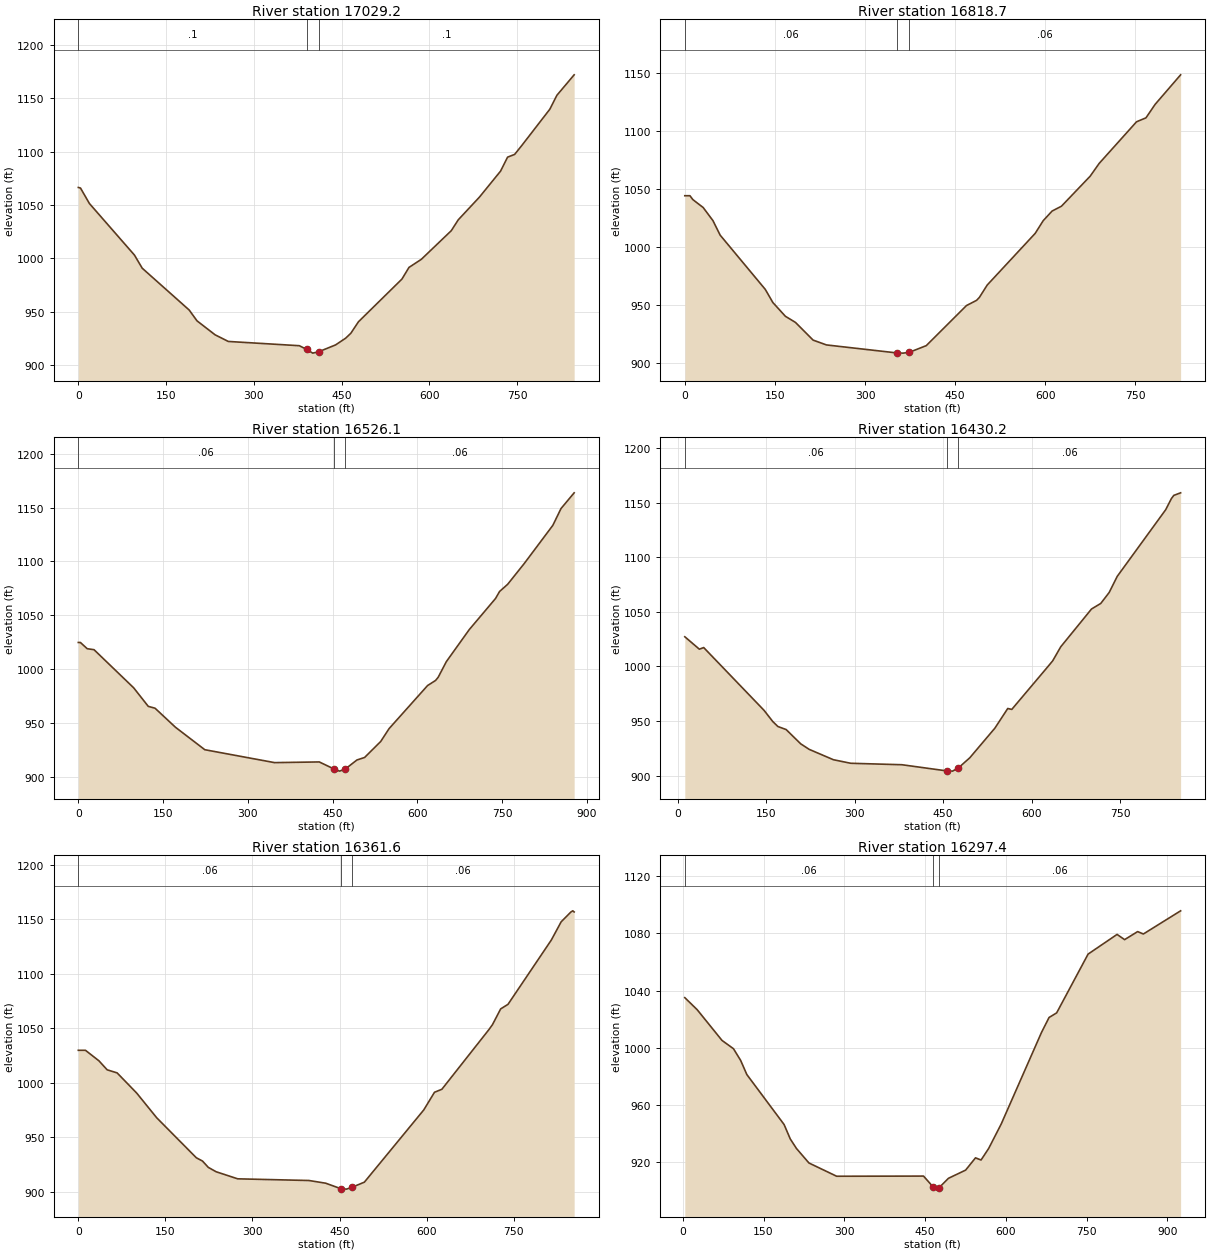
Type RM Length L Ch R = 1 ,17029.2 ,209.6,210.4,211.2
XS GIS Cut Line= 4
     1665163.536      211209.892     1664944.493      211398.242
     1664775.676       211534.97     1664488.269      211719.133
#Sta/Elev= 30
       0 1066.43     3.7  1065.9    18.9 1051.45    95.9 1003.22   109.2  990.92
   189.5   951.8   202.8  941.72   233.7  928.66   256.3  922.42   377.7  918.44
   390.6  914.93   400.6   911.5   410.6  912.73   439.7  919.18   456.9  925.46
   465.8  930.08   478.8  940.81   553.1  980.73   565.2  991.67   586.3  999.23
   637.4 1025.96   649.4 1036.17   685.6  1057.4   721.7  1081.7   733.7 1094.77
   745.8 1097.36   757.8 1105.54   805.9 1139.59     818 1152.64   847.5 1171.77
#Mann= 3 , 0 , 0
       0      .1       0   390.6    .045       0   410.6      .1       0
Bank Sta=390.6,410.6
XS Rating Curve= 0 ,0
Exp/Cntr=0.3,0.1

Type RM Length L Ch R = 1 ,16818.7 ,298,292.7,287.4
XS GIS Cut Line= 4
     1665037.002      211073.671     1664919.807      211159.242
     1664640.771      211371.309     1664389.639      211585.237
#Sta/Elev= 30
       0 1044.37     8.6 1044.37    13.4 1041.04    30.6 1034.19    46.9 1022.88
    58.8 1010.44     134  963.62   146.7  952.23   167.5  940.42   184.3  935.13
   213.6  919.89   235.8  915.73   353.1  908.83   363.1  908.66   373.1  909.23
     402  915.11     469  949.69   485.8  954.17   490.4  956.67   503.5  967.37
   583.4 1011.93   596.7 1022.85   611.5 1031.15   627.1 1035.33     675 1061.27
   689.8 1072.17   752.1 1108.12   767.8 1111.53   783.1 1123.17   825.5 1148.61
#Mann= 3 , 0 , 0
       0     .06       0   353.1    .045       0   373.1     .06       0
Bank Sta=353.1,373.1
XS Rating Curve= 0 ,0
Exp/Cntr=0.3,0.1

Type RM Length L Ch R = 1 ,16526.1 ,94,95.9,97.8
XS GIS Cut Line= 4
     1664788.685      210733.804     1664635.215      210975.171
     1664470.584       211166.31     1664233.403      211409.072
#Sta/Elev= 30
       0 1024.86     3.7 1024.86    15.7 1019.09    27.8 1018.18      98  982.79
   123.8  965.61   135.8  963.89   171.9  946.25   223.9  925.39   347.4  913.42
   426.5  914.05   452.4  907.58   462.4  905.53   472.4  907.45   493.3   915.9
   506.7  918.18   535.3  933.04     550   944.9   618.2   984.9   632.4  989.65
     637  992.59   651.5 1007.13     692  1036.8   738.5 1065.65   745.7 1072.19
   759.9 1078.78   788.9 1097.81     840 1133.55   854.5 1149.16   877.7 1163.69
#Mann= 3 , 0 , 0
       0     .06       0   452.4    .045       0   472.4     .06       0
Bank Sta=452.4,472.4
XS Rating Curve= 0 ,0
Exp/Cntr=0.3,0.1

Type RM Length L Ch R = 1 ,16430.2 ,69.8,68.5,67.2
XS GIS Cut Line= 4
     1664765.789      210715.507     1664521.981      210971.871
     1664368.162       211125.69     1664159.931      211315.086
#Sta/Elev= 30
    11.5 1027.19    36.2 1015.81    43.6 1017.29   146.1  959.71   160.8   949.5
   169.5  944.97   183.5  942.17   208.2   929.1   222.6  924.03   263.7  914.54
   293.1  911.29   379.9  909.96   455.9  904.31   465.9   904.1   475.9  907.15
     495  916.28   537.6  943.43   559.5  961.48   566.3  960.63   626.3  999.01
   635.7  1005.1   649.4 1017.99   701.6 1052.61   717.3 1057.71   731.6 1067.76
   745.3 1082.55   827.5 1143.59   837.1 1153.71   841.2 1156.68   852.8 1159.04
#Mann= 3 , 0 , 0
    11.5     .06       0   455.9    .045       0   475.9     .06       0
#XS Ineff= 2 , 0
       0     376                       0
Permanent Ineff=
       F       F
Bank Sta=455.9,475.9
XS Rating Curve= 0 ,0
Exp/Cntr=0.3,0.1

Type RM Length L Ch R = 1 ,16361.6 ,62.9,64.2,65.4
XS GIS Cut Line= 4
     1664756.143      210707.426     1664471.265      210917.749
     1664314.307      211091.973     1664154.995       211304.65
#Sta/Elev= 30
       0 1029.87    12.3 1029.87    35.5 1020.22    49.7 1011.95    66.8 1009.15
   100.5  990.66     135  967.98   203.3  931.26   213.9  928.26   223.9  922.46
   237.4  918.43   274.6  911.94   397.3   910.4   426.1  907.93     452  902.95
     462  902.49     472  904.29   492.8  908.89   595.1  975.15   613.6  991.37
   626.3  994.11   707.1 1048.69   713.5 1053.41   727.6 1067.85   740.2 1072.03
   814.9 1131.06   831.8 1147.76   848.7 1156.82   851.9 1157.84   854.2 1156.81
#Mann= 3 , 0 , 0
       0     .06       0     452    .045       0     472     .06       0
Bank Sta=452,472
XS Rating Curve= 0 ,0
Exp/Cntr=0.3,0.1

Type RM Length L Ch R = 1 ,16297.4 ,37.9,42.4,47
XS GIS Cut Line= 4
     1664749.546      210702.257     1664431.241      210874.586
     1664289.683      211016.866     1664039.615      211278.349
#Sta/Elev= 30
     3.8 1035.06    26.8 1026.63    72.9 1005.15    94.2  999.34   107.5  991.19
     119  981.29   188.2  946.32   199.7  936.21   211.2  929.55   234.3  919.44
   285.8  910.16   447.1  910.27  465.56  902.42   471.9  901.15   475.8  902.08
   493.4  908.72   525.3  914.46   543.6  923.02   553.9  921.51     568  929.54
   591.4  946.72   666.2 1010.76   680.2 1021.18   694.3 1024.41   752.7 1065.52
   806.5 1079.28   820.5 1075.63   844.7 1081.25   855.3 1079.57   924.5 1095.78
#Mann= 3 , 0 , 0
     3.8     .06       0  465.56    .045       0   475.8     .06       0
Bank Sta=465.56,475.8
XS Rating Curve= 0 ,0
Exp/Cntr=0.3,0.1

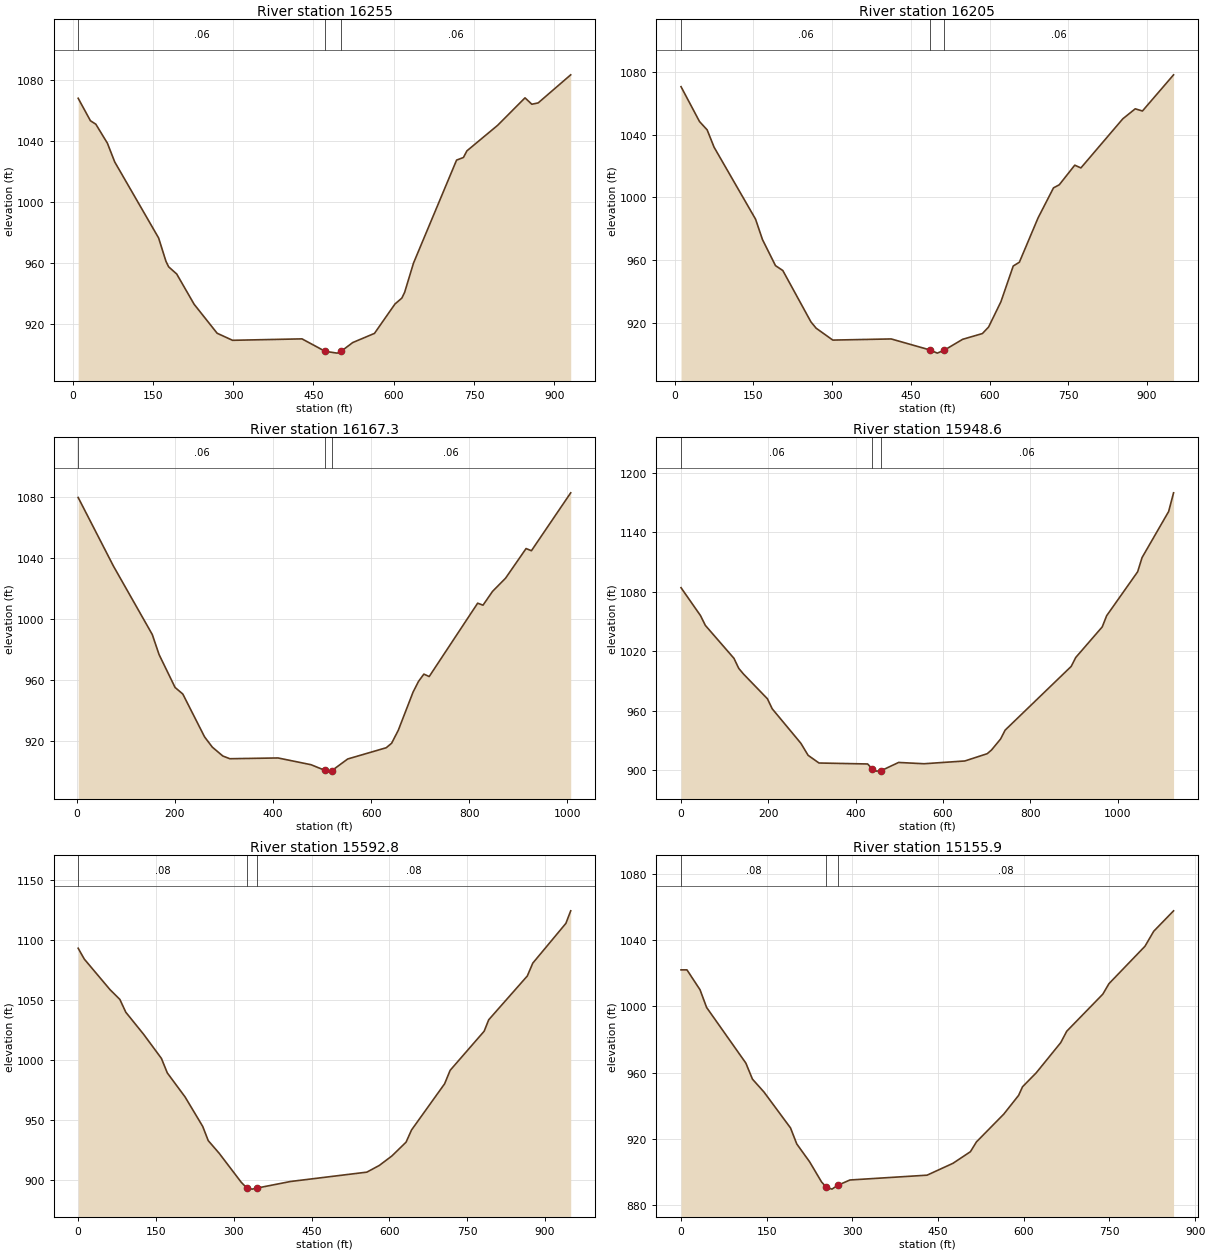
Type RM Length L Ch R = 1 ,16255   ,49.3,50,50.7
XS GIS Cut Line= 4
     1664693.186      210606.406     1664413.975       210858.89
     1664271.841      210959.387     1664040.241      211260.746
#Sta/Elev= 30
    10.5 1067.89    33.4 1053.15    43.5 1050.88    65.1 1038.44    78.8 1026.13
   160.8  976.27   174.5  960.97   179.5  957.37   194.6  952.64   227.1  932.82
   270.1   913.8   298.9  909.17   428.6  910.11   471.8  901.96   494.2  900.76
  501.23  901.83   523.3  907.68     564   913.7   602.3  932.97   615.1  936.83
   620.3  940.55   636.9  959.78   717.4 1027.34   730.2 1029.06   736.7  1033.4
   794.1 1050.15   845.2 1068.16     858 1063.97   869.8 1064.84   930.6 1083.26
#Mann= 3 , 0 , 0
    10.5     .06       0   471.8    .045       0  501.23     .06       0
Bank Sta=471.8,501.23
XS Rating Curve= 0 ,0
Exp/Cntr=0.3,0.1

Type RM Length L Ch R = 1 ,16205   ,32.7,37.7,42.8
XS GIS Cut Line= 5
     1664692.575      210595.201      1664452.43      210794.537
      1664357.47      210843.194     1664227.195      210930.306
     1664038.846      211254.424
#Sta/Elev= 30
    12.2 1070.72    47.4 1048.46      62 1043.12    75.2 1032.04   154.2  986.07
   167.4  973.01   192.1  956.42   206.1  953.28   259.6  920.51   269.6  916.43
   301.3  908.85   412.5  909.58   485.8   902.6   500.4  900.52  513.96  902.46
   548.6  909.34   586.3  913.03   598.1  917.22   621.5  933.32     645  956.16
   656.7  958.61   692.4  986.98   721.7 1006.08   732.7 1008.06   762.2 1020.58
   773.9 1018.82   853.7 1050.19   877.4 1056.59   891.1 1055.18   950.4 1078.29
#Mann= 3 , 0 , 0
    12.2     .06       0   485.8    .045       0  513.96     .06       0
Bank Sta=485.8,513.96
XS Rating Curve= 0 ,0
Exp/Cntr=0.3,0.1

Type RM Length L Ch R = 1 ,16167.3 ,208.2,218.6,229
XS GIS Cut Line= 4
     1664691.965      210587.642     1664458.151      210784.568
     1664179.934      210895.977     1664026.464      211267.095
#Sta/Elev= 30
     2.7 1079.43    74.8 1034.38   153.8  989.68   167.6  976.58   200.3  954.99
   216.1  950.67   260.4  922.63   276.1  915.95   297.6  910.09     312  908.32
   410.2  908.81   477.5  904.39   505.2  900.77   515.2  900.19   519.4  900.39
   552.2  908.14   630.7   915.5   641.7  918.43   655.3   926.9   685.5  951.95
   696.5   958.9   707.5  963.73   718.4  962.15   817.2  1010.2   828.1 1008.89
   847.5 1017.92     874 1026.54   915.9 1045.98   926.8 1044.56  1006.9 1082.48
#Mann= 3 , 0 , 0
     2.7     .06       0   505.2    .045       0   519.4     .06       0
Bank Sta=505.2,519.4
XS Rating Curve= 0 ,0
Exp/Cntr=0.3,0.1

Type RM Length L Ch R = 1 ,15948.6 ,363.9,355.9,347.8
XS GIS Cut Line= 4
     1664676.116      210552.803     1664411.961      210660.697
     1664047.354      210647.675     1663569.272      210634.654
#Sta/Elev= 30
       0 1084.14    44.7 1055.88    55.7 1046.05   121.3 1012.73   132.3 1002.56
   143.2  996.86     198  971.85   208.9  961.79   274.6  926.91   291.1   914.8
     316     907   427.5  906.02   437.8  901.05   447.8  898.79   457.8  899.12
   498.5  907.56   556.8  906.25   650.2  909.05   701.4  916.39   711.2  920.08
   732.1  931.24   742.5   940.2     894 1004.66   904.2 1013.57     965 1044.54
   975.1 1055.81  1046.1 1100.21  1056.2 1114.56  1117.1 1161.09  1128.4 1179.98
#Mann= 3 , 0 , 0
       0     .06       0   437.8    .045       0   457.8     .06       0
Bank Sta=437.8,457.8
XS Rating Curve= 0 ,0
Exp/Cntr=0.3,0.1

Type RM Length L Ch R = 1 ,15592.8 ,438.9,436.9,435
XS GIS Cut Line= 4
     1664523.576      210171.454     1664313.368      210281.208
     1664075.258      210351.897      1663632.52      210491.415
#Sta/Elev= 30
       0 1093.32    11.8 1084.29    61.2 1058.89    80.4 1050.61    91.9 1039.92
   126.2 1021.53   160.5 1001.43   171.9   989.3   206.2  969.22   240.2  944.63
   250.8  932.82     272  922.21   314.3  898.15   325.4  893.18   335.4  892.36
   345.4   893.3   409.4  898.73   556.6  906.53   580.8  912.16     605  920.07
   632.2  931.53   642.8  941.71   706.6  980.27   717.2  991.46   782.8  1024.1
   791.6 1033.64     866 1070.18   876.6 1080.92   940.4 1114.08   949.7 1124.54
#Mann= 3 , 0 , 0
       0     .08       0   325.4    .045       0   345.4     .08       0
Bank Sta=325.4,345.4
XS Rating Curve= 0 ,0
Exp/Cntr=0.3,0.1

Type RM Length L Ch R = 1 ,15155.9 ,143.1,145.3,147.5
XS GIS Cut Line= 4
     1664289.185      209797.545     1664151.528      209870.095
     1663827.846      209994.731     1663481.841      210093.324
#Sta/Elev= 30
       0 1022.19    10.4 1022.19    33.3 1010.12    44.8  999.41   113.5  965.71
     125  956.03   145.3  948.16   191.7  926.43   202.6  916.76     225  905.98
     246  893.73   254.2   890.6   264.2  889.38   274.2  891.66   295.6  894.91
   430.7  897.83     476  905.01   506.6  912.05   517.1  917.97     565  934.82
   590.9  946.15   597.8  951.38   621.9  959.87   664.7  978.12   675.2  985.02
   738.4 1007.49     749 1013.79   812.2 1036.51   827.4 1045.55   862.2 1057.95
#Mann= 3 , 0 , 0
       0     .08       0   254.2    .045       0   274.2     .08       0
Bank Sta=254.2,274.2
XS Rating Curve= 0 ,0
Exp/Cntr=0.3,0.1

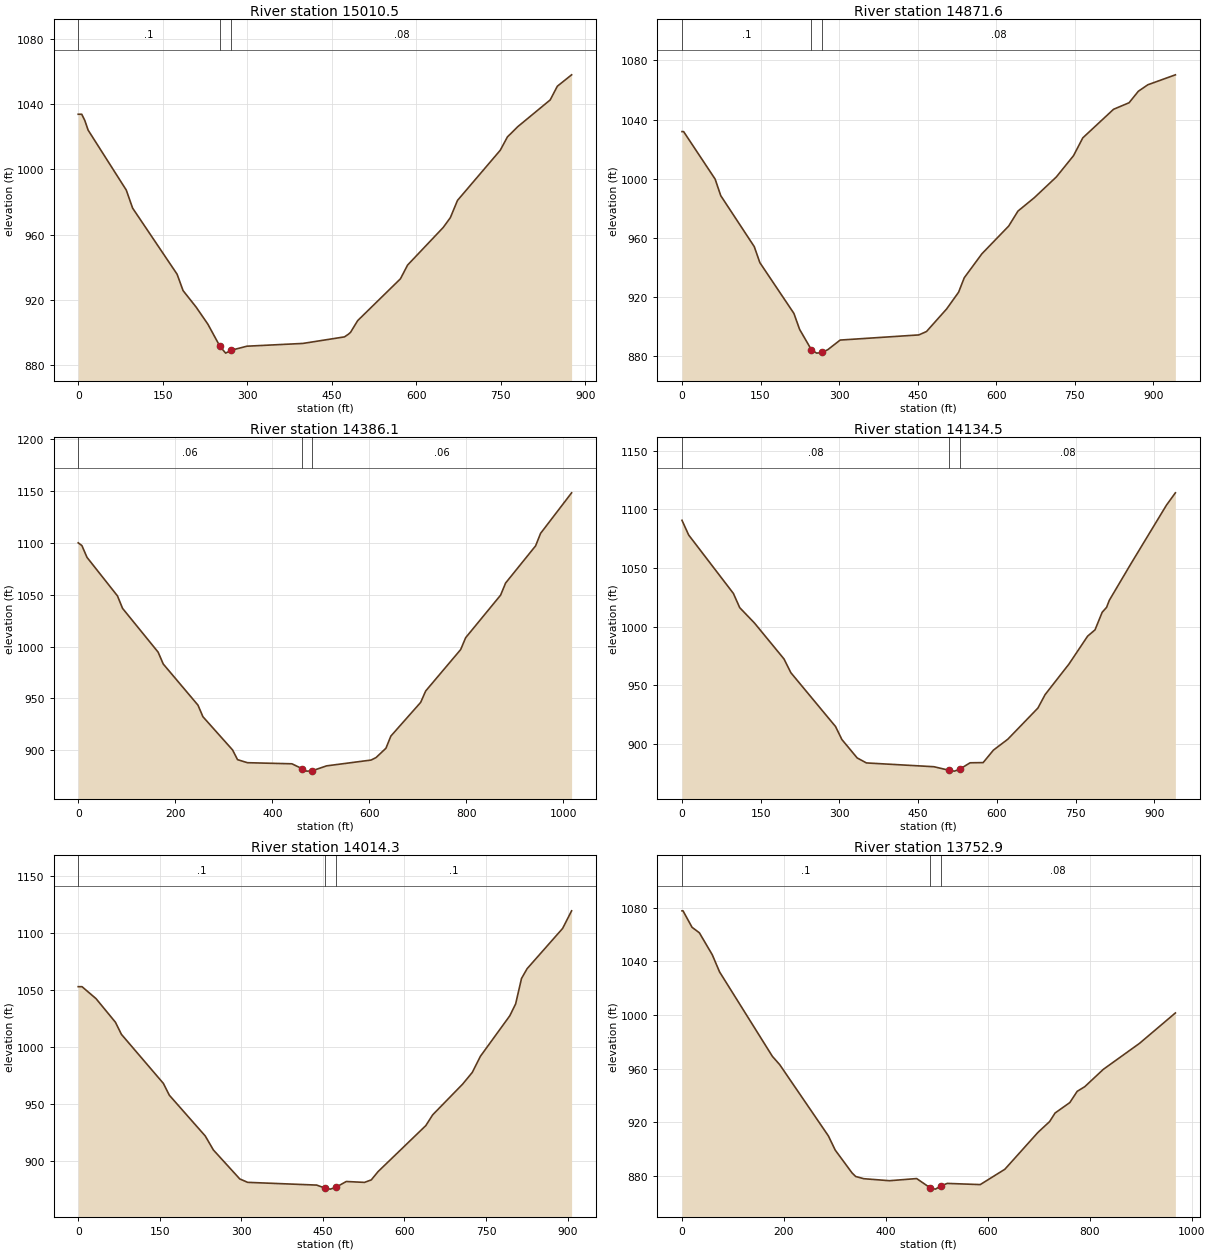
Type RM Length L Ch R = 1 ,15010.5 ,141,138.9,136.8
XS GIS Cut Line= 4
     1664255.274      209662.637     1664072.505      209751.928
      1663804.63      209828.663     1663489.319      210064.449
#Sta/Elev= 30
       0 1033.66     6.3 1033.66    11.8 1029.78    17.6 1023.94    85.3  987.22
    96.6  976.15   175.5  935.69   186.1  925.65   209.3  915.53   230.1   905.1
   251.7  891.41   261.7  887.34   271.7  889.11   299.4  891.58   398.8  893.28
   472.6  897.29   479.7  898.95   483.3  900.05     496  907.24   571.9  932.86
   584.6  941.28   647.9  964.33   660.5  970.33   673.2  980.89   749.1 1011.62
   761.8 1019.77   780.2 1026.07   837.7 1042.43   850.4 1050.83   875.7 1057.81
#Mann= 3 , 0 , 0
       0      .1       0   251.7    .045       0   271.7     .08       0
Bank Sta=251.7,271.7
XS Rating Curve= 0 ,0
Exp/Cntr=0.3,0.1

Type RM Length L Ch R = 1 ,14871.6 ,473.4,485.5,497.6
XS GIS Cut Line= 4
     1664218.496      209550.133     1664077.118      209596.639
     1663680.887      209747.319     1663468.819      210050.538
#Sta/Elev= 30
       0 1031.88     3.1 1031.88    63.3  999.74      74  988.56     138  954.08
   148.7  943.24   213.7  908.92   224.6  898.11   247.1  884.32   257.1  882.03
   267.1  882.47   278.4  884.35     302  890.86   452.3  894.35   466.9  896.63
   505.4  911.93   528.2  923.23     539  932.99   572.7  949.22   623.9  967.99
   641.6  978.11   672.9   987.2   714.9 1001.21   747.7  1015.6   765.4 1027.64
   824.1 1046.97   853.8  1051.4   871.5 1059.18   889.6 1063.55   942.2 1070.28
#Mann= 3 , 0 , 0
       0      .1       0   247.1    .045       0   267.1     .08       0
Bank Sta=247.1,267.1
XS Rating Curve= 0 ,0
Exp/Cntr=0.3,0.1

Type RM Length L Ch R = 1 ,14386.1 ,241.4,251.6,261.8
XS GIS Cut Line= 4
     1664287.325      209252.494     1664108.742      209205.988
     1663615.778      209153.902     1663284.655      209094.374
#Sta/Elev= 30
       0 1100.07     7.6 1097.44    18.1 1086.07    80.9 1048.88    91.4 1036.86
   164.7  994.63   175.2  983.21   246.8   943.5     257  932.34   318.1  900.28
   328.3  890.93   348.7  887.99   440.4  886.93     461  882.29     471  879.86
     481     880   511.8  884.93   603.5  890.54   613.7  892.92   634.1  901.91
   644.3  913.68   705.7  946.18     716  957.14   788.1  997.12   798.4 1008.56
   870.4 1049.62   880.7  1061.3   942.5 1097.15   952.8 1109.22  1016.7 1148.31
#Mann= 3 , 0 , 0
       0     .06       0     461    .045       0     481     .06       0
Bank Sta=461,481
XS Rating Curve= 0 ,0
Exp/Cntr=0.3,0.1

Type RM Length L Ch R = 1 ,14134.5 ,117.5,120.2,122.8
XS GIS Cut Line= 4
     1664280.387      209211.993      1664030.65      209045.967
     1663769.751      208895.287     1663517.223      208669.268
#Sta/Elev= 30
       0 1090.62    12.7 1078.14    97.9 1028.35     110 1016.21   138.1 1003.12
   194.4  972.47   207.4  960.81   292.6  914.89   304.6  903.88   333.8  888.14
   351.4   883.9   480.1  880.66   509.2  877.59   519.2  876.91   529.2  878.57
   548.9  884.01   573.8  884.18   593.4   894.8   620.9  904.14   678.2  930.67
   691.8  942.07   737.3  968.13   772.9  991.93     787  997.31   800.6 1012.26
     809 1016.47   814.2 1022.47     855 1053.32     923 1103.49   940.1 1114.06
#Mann= 3 , 0 , 0
       0     .08       0   509.2    .045       0   529.2     .08       0
Bank Sta=509.2,529.2
XS Rating Curve= 0 ,0
Exp/Cntr=0.3,0.1

Type RM Length L Ch R = 1 ,14014.3 ,259.5,261.4,263.3
XS GIS Cut Line= 4
      1664322.67      209057.169     1664052.154      208941.883
      1663754.98      208725.281     1663524.626      208640.475
#Sta/Elev= 30
       0 1052.83       7 1052.83    32.8 1042.31    68.4 1021.61    79.5 1010.91
   156.6  967.81   167.6   957.4   233.7  921.53   248.5  909.33   297.1  883.81
   311.6  880.81   438.6   878.4   453.7  875.76   463.7  874.85   473.7  876.44
     493  881.56   526.4  880.77   538.9  882.95   551.4  890.24   639.2   930.7
   651.8  940.14     707   967.2   724.7  977.49   739.6  991.64   793.6 1027.22
   804.4 1037.69   815.2 1060.04   825.4  1068.6   890.8 1104.05   907.3 1119.52
#Mann= 3 , 0 , 0
       0      .1       0   453.7    .045       0   473.7      .1       0
Bank Sta=453.7,473.7
XS Rating Curve= 0 ,0
Exp/Cntr=0.3,0.1

Type RM Length L Ch R = 1 ,13752.9 ,201.1,200,198.9
XS GIS Cut Line= 4
     1664443.585      208977.179     1664253.841      208787.434
     1663926.438      208508.398     1663673.446      208415.386
#Sta/Elev= 30
       0 1077.72       2 1077.72    19.7 1065.46    34.1 1061.35    59.4 1045.01
    73.7 1032.23   177.4  969.27   191.8  963.07   287.3  909.97   300.6  899.46
   333.6  882.46   340.8  879.76   356.7  878.11   407.1  876.61   460.4  878.21
   487.4  871.22   497.4  870.34   507.4  872.64   520.5   874.6   585.2  873.72
   633.5  885.14   698.5  912.63   721.4   920.7     732  927.04     761  934.84
   775.4   943.2   790.4  946.71   826.8  959.62   897.9  979.01   968.1 1001.62
#Mann= 3 , 0 , 0
       0      .1       0   487.4    .045       0   507.4     .08       0
Bank Sta=487.4,507.4
XS Rating Curve= 0 ,0
Exp/Cntr=0.3,0.1

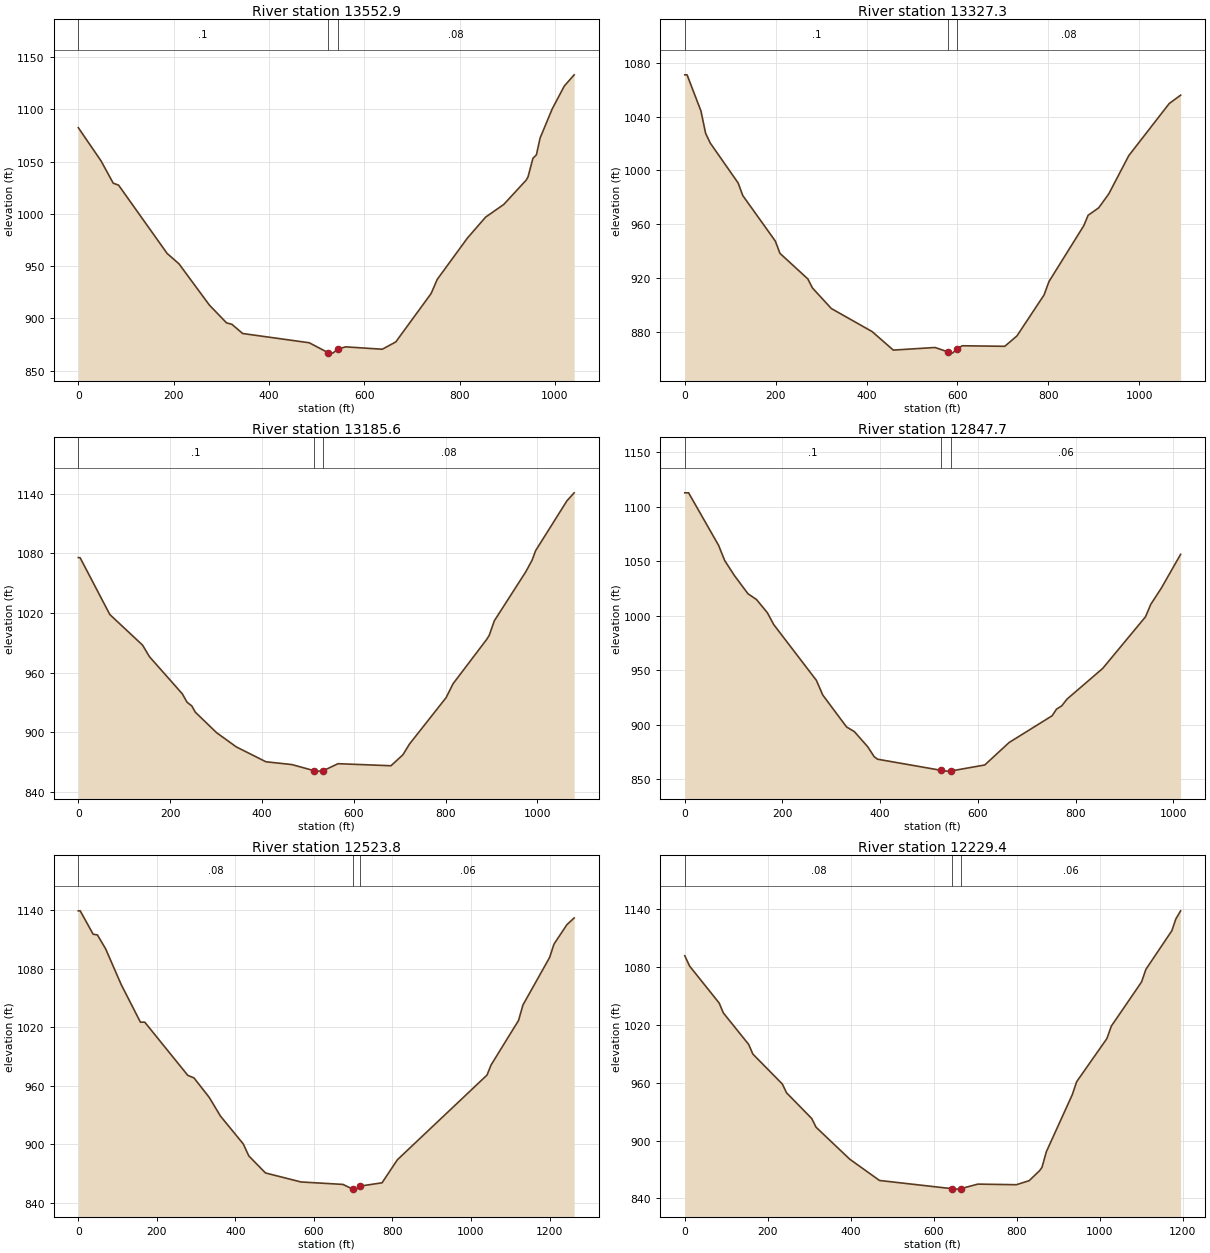
Type RM Length L Ch R = 1 ,13552.9 ,225,225.7,226.4
XS GIS Cut Line= 4
      1664493.85      208927.377     1664315.266      208568.815
     1664064.134       208373.49     1663807.421       208179.56
#Sta/Elev= 30
       0 1082.54    47.7 1050.74    73.2 1029.48    84.5 1027.56   186.4  962.18
   211.2  952.28   275.1  912.77     311  895.79   322.3  894.39   344.9  885.59
   484.6  876.74   524.1  867.25   534.1  866.82   544.1   870.5   560.8  872.82
   637.9  870.55   666.2  877.55   740.4  923.89   753.1  937.33   816.5  976.94
   854.7  996.97   892.8  1009.1   939.6 1032.26   943.6 1035.33     954 1053.23
   961.3 1056.62     969 1072.62   994.4 1100.48  1019.8 1122.41  1040.5 1133.14
#Mann= 3 , 0 , 0
       0      .1       0   524.1    .045       0   544.1     .08       0
Bank Sta=524.1,544.1
XS Rating Curve= 0 ,0
Exp/Cntr=0.3,0.1

Type RM Length L Ch R = 1 ,13327.3 ,139.6,141.7,143.7
XS GIS Cut Line= 4
      1664862.63         208525.     1664563.131      208485.935
     1664224.567      208206.899     1663900.885      208072.962
#Sta/Elev= 30
       0 1071.19       5 1071.19    35.6 1044.22    45.8 1027.68    56.1 1020.36
   117.4  990.67   127.6   981.3   199.2  947.43   209.4  938.29   270.7  919.25
   280.9  912.51   322.5  897.19   412.2  880.03   458.8  866.25   550.7  868.18
   578.9  864.95   588.9  863.99   598.9  866.99   610.5  869.48   704.1  869.07
   730.9   876.8   790.5  907.27   801.5  917.33   878.2     959   887.5  966.62
   910.8  972.16   933.1  982.62     977 1011.02    1066 1049.82  1091.1 1056.04
#Mann= 3 , 0 , 0
       0      .1       0   578.9    .045       0   598.9     .08       0
Bank Sta=578.9,598.9
XS Rating Curve= 0 ,0
Exp/Cntr=0.3,0.1

Type RM Length L Ch R = 1 ,13185.6 ,339.9,337.9,335.9
XS GIS Cut Line= 4
     1664871.441      208508.398     1664686.264      208440.664
     1664292.906       208058.22     1663991.547      207913.121
#Sta/Elev= 30
       0 1075.73     3.9 1075.62    68.6 1018.55     140  987.74   154.9   976.2
   226.6  938.79   236.8   930.4   247.3  926.61   254.9  920.37   301.3  899.75
   344.3  885.45   408.8  870.52   465.4  867.72   513.5  861.59   523.5  861.13
   533.5  861.54   565.9  868.61   681.2  866.54   707.3  877.62   721.4  888.27
   801.4  935.07   816.4  948.91     890  993.71   895.1  997.46   906.4 1012.24
     975 1061.54   988.7 1073.22   996.3 1082.68  1064.6 1132.85  1080.3 1140.84
#Mann= 3 , 0 , 0
       0      .1       0   513.5    .045       0   533.5     .08       0
Bank Sta=513.5,533.5
XS Rating Curve= 0 ,0
Exp/Cntr=0.3,0.1

Type RM Length L Ch R = 1 ,12847.7 ,328.8,323.9,319
XS GIS Cut Line= 4
     1665076.067      208268.427        1664864.      208115.887
     1664551.479      207857.314     1664222.217      207743.839
#Sta/Elev= 30
       0 1112.73     7.8 1112.73    69.2 1064.52    81.7 1050.57   101.6 1036.81
   129.3 1020.13   146.7 1014.86   169.1 1002.67     182  991.87   269.4  940.65
   282.5  927.14   331.2  897.85   347.1   893.6   374.6  879.64   387.8   870.5
   394.8  868.25   524.9  858.04   534.9  857.32   544.9  857.45   614.1  862.97
     664  883.59     752  908.13     761  914.22   771.8  917.26   782.5  923.39
   855.6  951.59   943.2  998.95     954 1010.41   975.5 1025.18  1015.1 1056.29
#Mann= 3 , 0 , 0
       0      .1       0   524.9    .045       0   544.9     .06       0
Bank Sta=524.9,544.9
XS Rating Curve= 0 ,0
Exp/Cntr=0.3,0.1

Type RM Length L Ch R = 1 ,12523.8 ,302.3,294.4,286.4
XS GIS Cut Line= 4
      1665249.07      208156.813     1665111.412      207821.969
     1664605.426      207546.653     1664281.744       207522.47
#Sta/Elev= 30
       0 1139.51     4.8 1139.51    37.7 1115.55    48.6  1114.8    69.6 1100.49
   109.1 1063.96   158.2 1025.32   169.2 1025.34   278.8  970.79   294.5  968.21
   333.6  948.09     362  929.01   420.1  900.46   434.2  888.19   476.6  870.72
     567  861.49   673.9  858.97   698.5   854.2   708.5  854.14   718.5  857.29
   773.5  860.64   812.4   884.2  1040.8  971.11    1051  981.38  1121.1 1027.12
  1132.3 1042.99  1200.3 1091.76  1211.3 1105.37    1244 1125.18  1262.7 1132.24
#Mann= 3 , 0 , 0
       0     .08       0   698.5    .045       0   718.5     .06       0
Bank Sta=698.5,718.5
XS Rating Curve= 0 ,0
Exp/Cntr=0.3,0.1

Type RM Length L Ch R = 1 ,12229.4 ,122.9,122.3,121.8
XS GIS Cut Line= 4
     1665558.721       207403.49     1665138.772      207425.813
     1664706.266      207346.288     1664381.189      207266.763
#Sta/Elev= 30
       0 1091.69    11.8 1080.91    82.8 1042.72      93 1032.41   153.9  999.81
     164  989.81   235.1   958.7   245.2  949.61   306.1  922.86   316.3  913.93
   397.5  880.77   469.3  858.68   644.8  850.11   654.8   849.7   664.8  850.14
   706.3   854.9   799.1  854.28     830  858.47   855.1  868.83   860.9  872.33
   871.3  888.41   933.9  947.65   944.4   961.1  1017.4 1005.92  1027.9  1018.7
  1100.9 1064.61  1111.3 1077.63  1173.9 1117.72  1183.3 1129.74    1195 1138.33
#Mann= 3 , 0 , 0
       0     .08       0   644.8    .045       0   664.8     .06       0
Bank Sta=644.8,664.8
XS Rating Curve= 0 ,0
Exp/Cntr=0.3,0.1

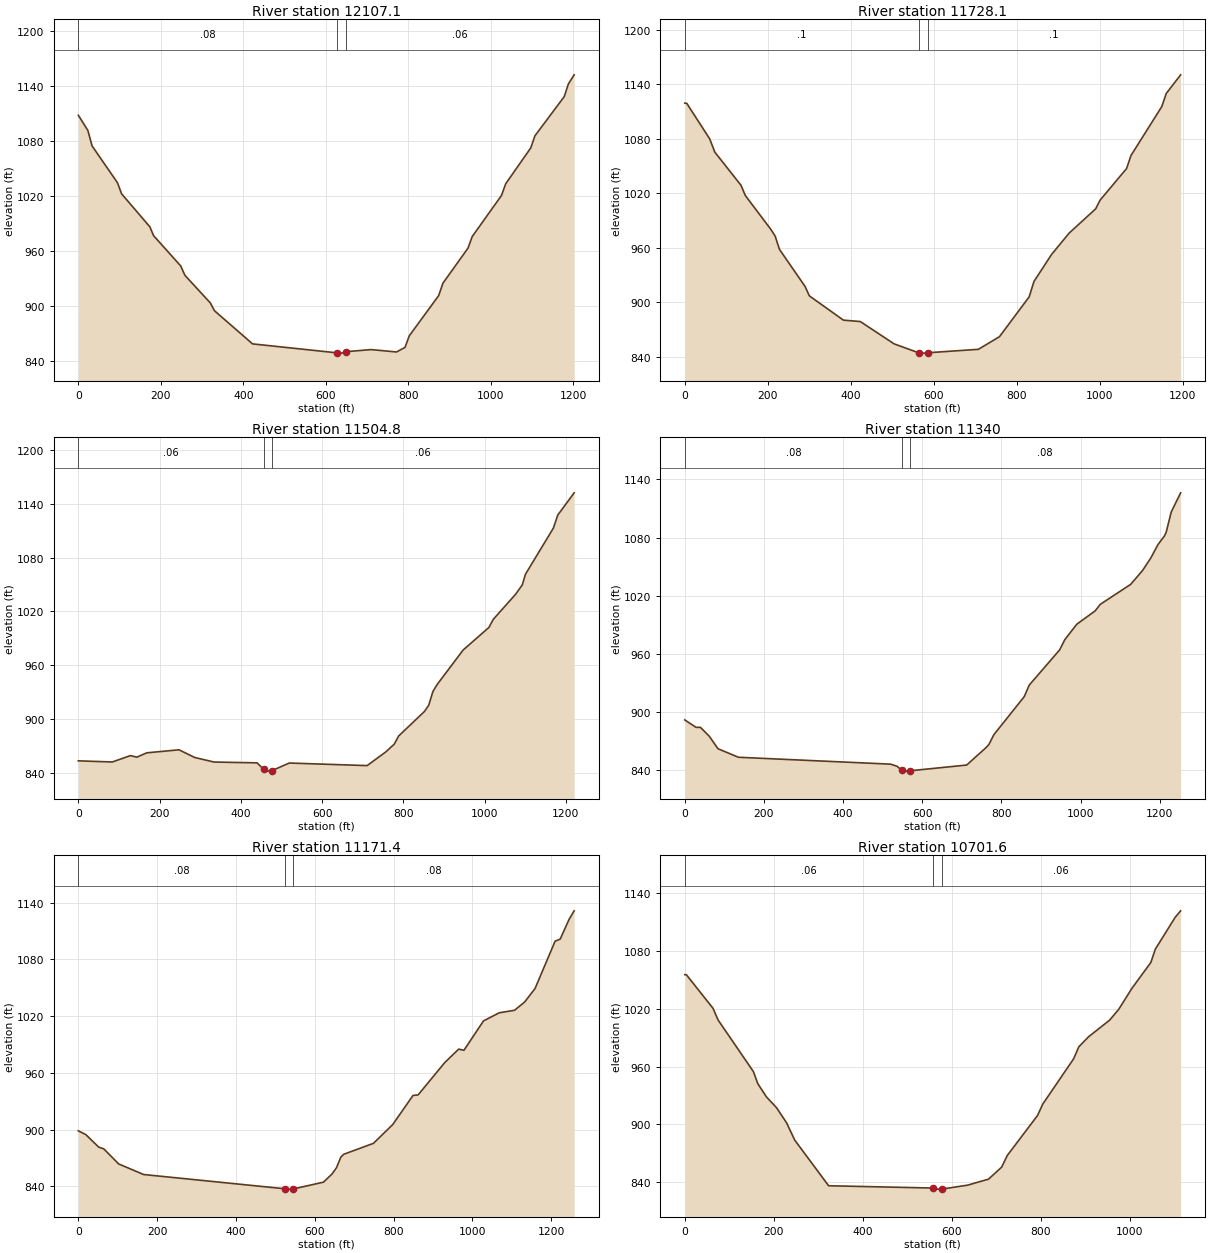
Type RM Length L Ch R = 1 ,12107.1 ,381.6,379,376.4
XS GIS Cut Line= 4
      1665559.73      207260.176     1665210.005      207308.543
     1664726.342      207230.412     1664367.316      207226.692
#Sta/Elev= 30
       0 1107.78    23.1 1091.23    33.4 1074.36    94.8 1034.38     105  1022.2
   173.4  986.34   182.4  976.74   248.2  943.78   258.5   933.5   319.9  903.57
   330.1     895   422.4  858.93     628  849.13     638  848.87     648  850.41
   709.9  852.71   771.5  850.12     792  855.16   802.3  867.72   873.7  911.58
   883.9  925.01   944.7  963.18   954.9  975.73  1025.8 1020.43    1036 1033.16
  1096.8 1072.21  1106.9 1085.37  1177.9 1128.02    1188 1141.82    1202 1151.76
#Mann= 3 , 0 , 0
       0     .08       0     628    .045       0     648     .06       0
Bank Sta=628,648
XS Rating Curve= 0 ,0
Exp/Cntr=0.3,0.1

Type RM Length L Ch R = 1 ,11728.1 ,242.6,223.3,199.2
XS GIS Cut Line= 4
     1665569.031      206969.979     1665189.542       206904.87
     1664776.569      206876.967      1664398.94      206996.022
#Sta/Elev= 30
       0 1119.13     4.6 1119.13      60 1079.94    72.4 1065.32   135.5 1028.88
   145.8 1017.68   207.5  980.29   217.8  972.93   228.1  958.43   289.8  917.69
   300.1  907.29   382.3  880.55     423     879   504.3  854.49   565.4  844.34
   575.4  844.27   585.4  844.67   707.5  848.46   758.3  862.33   829.9  906.15
   841.4  923.01   883.9   952.8   926.4  976.36   990.2 1002.98  1000.8 1012.53
  1064.6 1047.25  1075.2 1061.59  1149.6 1115.52  1160.2 1129.79  1194.9 1150.37
#Mann= 3 , 0 , 0
       0      .1       0   565.4    .045       0   585.4      .1       0
Bank Sta=565.4,585.4
XS Rating Curve= 0 ,0
Exp/Cntr=0.3,0.1

Type RM Length L Ch R = 1 ,11504.8 ,157.2,164.8,177.1
XS GIS Cut Line= 4
     1665438.814      206387.723     1664990.496      206761.632
     1664837.956      206841.622     1664393.359      206975.559
#Sta/Elev= 30
       0   853.1    83.6  851.82   128.2  858.95     144  857.23   168.6  862.05
   247.8  865.41   286.5  856.84   333.9  851.76   439.9  850.84   456.3   843.6
   466.3  841.61   476.3  842.08   519.1  850.65   710.8  847.78   756.6  862.99
   777.7   871.8   788.3  880.78   851.8  908.17   862.4  915.13   872.9  930.65
   883.6  938.59   947.1  976.82  1010.6 1002.05  1021.2 1011.01  1076.3  1039.1
  1092.6 1049.46  1100.7 1061.56  1169.4 1113.08    1180 1127.45  1220.4 1152.35
#Mann= 3 , 0 , 0
       0     .06       0   456.3    .045       0   476.3     .06       0
Bank Sta=456.3,476.3
XS Rating Curve= 0 ,0
Exp/Cntr=0.3,0.1

Type RM Length L Ch R = 1 ,11340   ,168.2,168.6,169.1
XS GIS Cut Line= 4
     1665304.799       206129.69     1665147.143      206482.671
     1664794.162      206636.141     1664413.278      206930.524
#Sta/Elev= 30
       0  892.12    28.4  884.49    39.5  884.47    61.7  875.39    83.9  862.41
   135.6  853.64   519.8  846.53   536.4  844.35   548.5  840.08   558.5  839.34
   568.5  839.67   712.3  845.61   761.1  863.56   768.5  866.83   780.8  876.81
   857.7  916.12   870.5   928.1   947.4  964.42   960.2  974.83   990.6  990.81
    1037 1004.54  1049.8 1011.25  1126.7 1031.87  1156.8  1046.2    1178 1059.35
  1195.7 1072.93  1212.2 1081.86  1216.4 1085.61  1229.2 1106.48  1252.9 1126.23
#Mann= 3 , 0 , 0
       0     .08       0   548.5    .045       0   568.5     .08       0
Bank Sta=548.5,568.5
XS Rating Curve= 0 ,0
Exp/Cntr=0.3,0.1

Type RM Length L Ch R = 1 ,11171.4 ,470.9,469.8,468.7
XS GIS Cut Line= 4
     1665304.877      206114.268     1665163.499      206302.152
      1664736.96      206482.671     1664391.499      206923.473
#Sta/Elev= 30
       0  898.64    18.8  894.77    51.8  881.44    64.5  879.64   102.5  863.63
   165.9  852.48   524.1  837.43   534.1  837.05   544.1  837.12   622.1  844.41
   644.1  853.19   655.1  859.67   666.1  870.86   673.6   873.9   748.9  885.45
   797.8   905.3   849.3  936.07   862.2  936.64   929.7  970.77   965.2  985.04
   978.5  983.81  1028.2 1014.89  1068.2 1023.46  1106.9  1026.1  1132.6 1034.84
    1159 1049.13  1209.9 1099.17  1222.8 1101.33  1245.6 1122.41  1258.2 1131.22
#Mann= 3 , 0 , 0
       0     .08       0   524.1    .045       0   544.1     .08       0
Bank Sta=524.1,544.1
XS Rating Curve= 0 ,0
Exp/Cntr=0.3,0.1

Type RM Length L Ch R = 1 ,10701.6 ,432.4,426.7,420.9
XS GIS Cut Line= 4
     1665228.607      205738.499     1665003.518      205851.974
     1664542.178      206064.041     1664231.518      206235.183
#Sta/Elev= 30
       0 1055.39     3.5 1055.39    63.5 1020.46    74.8 1008.37   154.3  954.69
   164.1  942.23   183.6  928.45   206.1  917.37   228.7  901.65   247.1  883.64
   323.3  836.22     558  833.85     568  832.72     578  832.79   635.6  836.83
   682.7  843.07   712.2  855.55   724.9  867.66     793  909.29   804.6     921
     874  968.05   885.6  980.46   907.6  990.94     955 1008.22   975.5  1019.5
  1005.3 1041.42  1047.6  1068.1  1057.6 1081.89  1102.3    1115  1114.5 1121.71
#Mann= 3 , 0 , 0
       0     .06       0     558    .045       0     578     .06       0
Bank Sta=558,578
XS Rating Curve= 0 ,0
Exp/Cntr=0.3,0.1