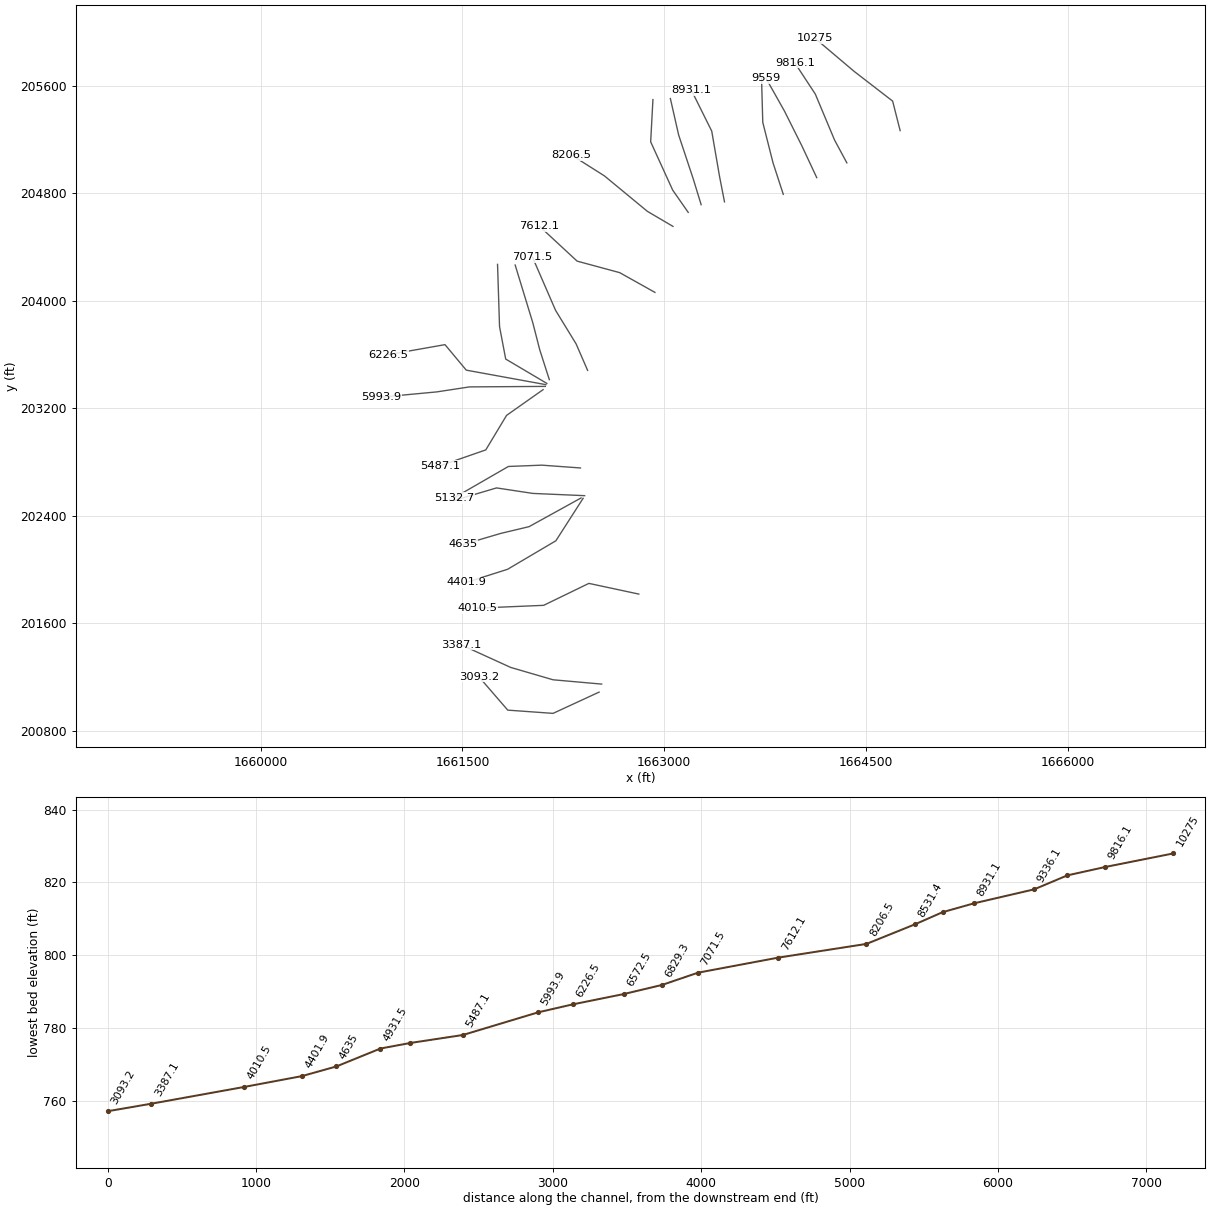
HEC-RAS study bchcrk.prj: bchcrk

--- bchcrk.g01 (geometry) --- (continued)

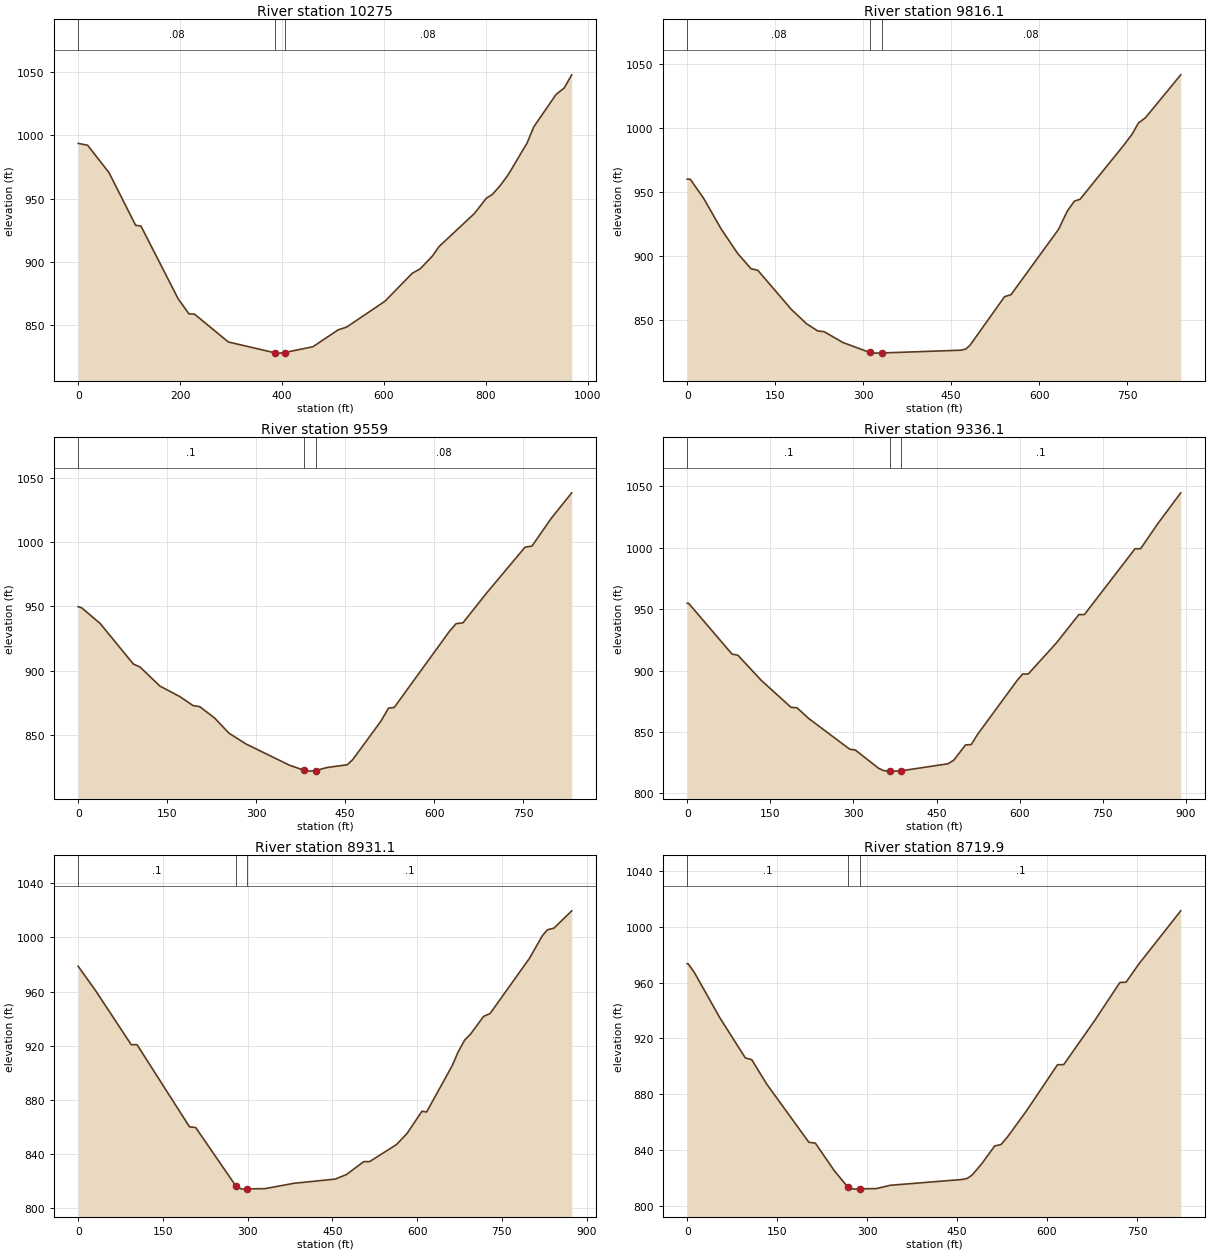
Type RM Length L Ch R = 1 ,10275   ,471.8,458.9,446
XS GIS Cut Line= 4
     1664754.246      205265.998     1664698.438      205485.506
     1664411.961      205706.875     1664121.764      205952.427
#Sta/Elev= 30
       0  993.54    18.5  992.03    60.4  970.46   112.7  928.86   123.1  928.27
   196.3  870.76   217.3  859.01   228.4  858.69   294.7  836.76   385.5  828.28
   395.5  827.97   405.5  828.46   460.7  833.03   510.2  846.34   526.7  848.51
     602  868.93   655.6  891.01   671.3  894.55     695   904.5   708.2  912.09
   777.6  938.19   801.2  950.29   812.5  953.11   828.2  960.18   843.9  968.74
   880.9  993.74   894.1 1006.55     938  1032.2   953.7 1037.17   968.6 1047.62
#Mann= 3 , 0 , 0
       0     .08       0   385.5    .045       0   405.5     .08       0
Bank Sta=385.5,405.5
XS Rating Curve= 0 ,0
Exp/Cntr=0.3,0.1

Type RM Length L Ch R = 1 ,9816.1  ,255.4,257,258.7
XS GIS Cut Line= 4
     1664358.014      205026.027     1664266.862      205195.309
     1664123.624      205537.593     1663971.084      205770.123
#Sta/Elev= 30
       0  960.01     5.2  960.01    28.2  944.95    57.7  921.31    85.8  902.18
   108.8  890.12   120.3  888.93   177.8  858.25   203.5  847.16   222.5  841.59
   233.4  840.99   265.5  832.53   311.3  824.77   321.3  824.25   331.3  824.37
   466.9  826.54   475.2  827.51   482.4  830.57   541.1  868.33   552.1  869.91
   625.9  916.36   633.2     921   647.8  934.96     660  942.87   669.8  944.38
   744.9  986.92   758.7  995.29   769.1 1003.77   781.2    1008   841.4 1041.49
#Mann= 3 , 0 , 0
       0     .08       0   311.3    .045       0   331.3     .08       0
Bank Sta=311.3,331.3
XS Rating Curve= 0 ,0
Exp/Cntr=0.3,0.1

Type RM Length L Ch R = 1 ,9559    ,228.3,222.9,217.4
XS GIS Cut Line= 4
     1664134.242      204915.883     1664024.022      205151.668
     1663894.271      205411.172     1663756.148      205656.724
#Sta/Elev= 30
       0   949.7     5.7  948.94    37.1  936.63      93  905.16   104.2  902.86
   137.8  888.02   171.4  879.85   193.7  872.85   204.9  872.03   230.3  863.08
   254.2  851.43   283.5  842.88     357  826.37   380.5   822.7   390.5  821.93
   400.5  822.38   419.5  824.74   453.5  826.86   462.7  830.78   510.2  860.65
   523.2  870.89   532.8   871.4   625.4  930.27   637.1  936.53   648.7  937.19
   687.3  959.63   753.3  995.96     765   996.8   797.4 1018.31   832.1 1038.22
#Mann= 3 , 0 , 0
       0      .1       0   380.5    .045       0   400.5     .08       0
Bank Sta=380.5,400.5
XS Rating Curve= 0 ,0
Exp/Cntr=0.3,0.1

Type RM Length L Ch R = 1 ,9336.1  ,406.9,405,403.2
XS GIS Cut Line= 4
     1663885.513      204791.636     1663809.243      205026.027
     1663732.973      205327.386     1663723.672      205660.369
#Sta/Elev= 30
       0  954.78     2.6  954.78    80.7   913.5    91.4  912.52   133.9  891.93
   187.3  870.08     198  869.74   219.3  860.97     293  836.03   303.5  835.27
   345.3  820.42     355  818.41   366.6  818.13   376.6  818.11   386.6   818.4
   470.7  824.12   481.2  827.14   502.1  839.44   512.6  839.75   523.5  847.79
     595   891.8   605.2  897.19   615.3  897.21     666  922.47   706.6  945.61
   716.7  945.63     808  999.27   818.1   999.3   848.5 1019.32   890.5 1044.81
#Mann= 3 , 0 , 0
       0      .1       0   366.6    .045       0   386.6      .1       0
Bank Sta=366.6,386.6
XS Rating Curve= 0 ,0
Exp/Cntr=0.3,0.1

Type RM Length L Ch R = 1 ,8931.1  ,207.4,211.2,215
XS GIS Cut Line= 4
     1663448.356      204735.829     1663411.152      204927.434
     1663353.484      205262.277     1663202.805      205565.497
#Sta/Elev= 30
       0  978.63    31.8  960.02    93.8  920.82   104.1  920.82     197  860.25
     208   859.7   279.6  816.27   289.6  814.28   299.6  814.46   330.7  814.64
   382.1   818.6   454.8  821.66   474.7  825.01   505.5  834.56   515.8  834.59
   563.2  847.09   581.8  855.19   608.5  871.71   616.7  871.16   662.3  905.56
   672.4  915.32   684.1  924.21     695  928.87   717.6  941.69     729  943.72
   798.9  984.56   821.7 1001.24   830.8  1005.6   842.1 1006.74   873.6 1019.52
#Mann= 3 , 0 , 0
       0      .1       0   279.6    .045       0   299.6      .1       0
Bank Sta=279.6,299.6
XS Rating Curve= 0 ,0
Exp/Cntr=0.3,0.1

Type RM Length L Ch R = 1 ,8719.9  ,185.8,188.5,191.2
XS GIS Cut Line= 4
      1663274.81      204714.977     1663216.213      204906.117
     1663107.389      205233.984     1663046.001      205504.649
#Sta/Elev= 30
       0  973.48     1.5  973.48    12.1  967.05    54.5  934.66    96.9  905.96
   107.5  904.71   132.4  887.29   202.9  845.43   213.6  844.87   245.6  824.85
   267.7  813.41   277.7  811.86   287.7  812.09   314.8  812.22   338.8  814.62
   458.8  818.79   467.1  819.59   475.2  822.02   491.4  830.23   512.6   842.8
   523.2  843.84     534  849.25   565.5  867.87   617.4  901.06   627.8  901.14
   679.8     933   721.4  960.02   731.7  960.24   752.5  972.99   822.9 1011.42
#Mann= 3 , 0 , 0
       0      .1       0   267.7    .045       0   287.7      .1       0
Bank Sta=267.7,287.7
XS Rating Curve= 0 ,0
Exp/Cntr=0.3,0.1

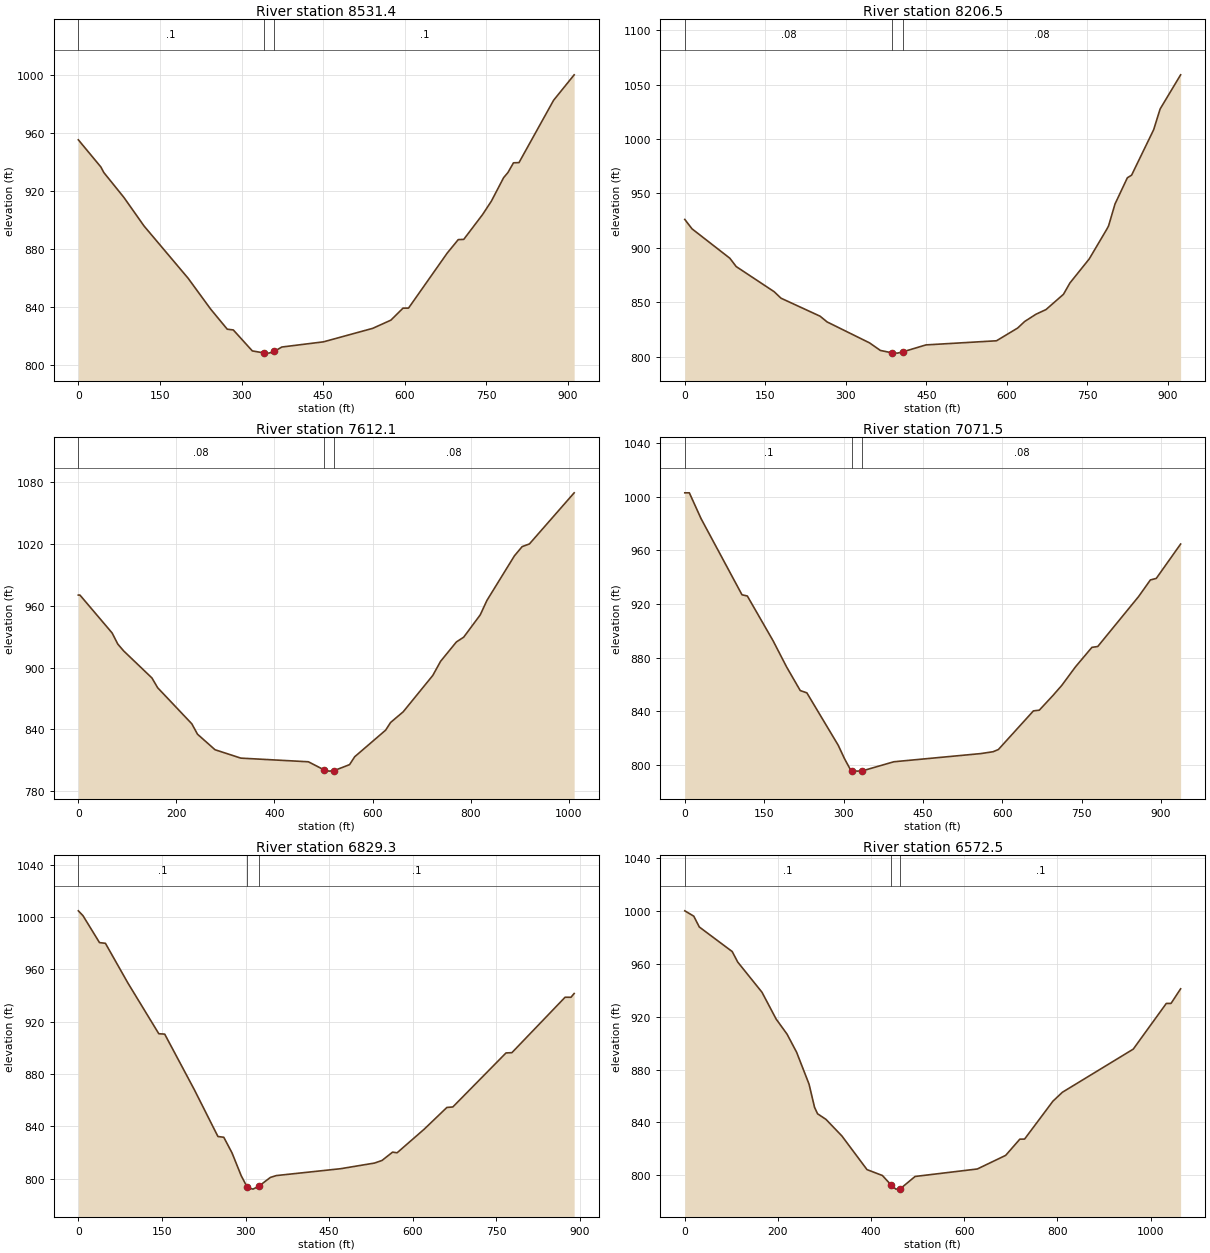
Type RM Length L Ch R = 1 ,8531.4  ,313.5,324.9,336.3
XS GIS Cut Line= 4
     1663178.621      204657.699     1663063.286       204823.26
     1662899.585      205182.287     1662916.327      205496.668
#Sta/Elev= 30
       0  955.62    41.5  936.83    46.8  933.07    83.9   915.8   120.9   896.1
   201.8  860.11   243.2  838.84   273.7  824.99   284.8  824.48   319.7  810.03
   340.3  808.67   350.3  808.49   360.3  809.68   373.9   812.7   450.6  816.28
     541  825.58   574.4  831.23   596.7  839.52   606.8  839.53   677.9  877.48
   698.2  886.78   708.3  886.94   743.1  904.17   759.1  913.34   781.6  929.52
   789.5  933.03   799.7  939.75   809.8  939.88   873.4  982.87   911.2 1000.43
#Mann= 3 , 0 , 0
       0      .1       0   340.3    .045       0   360.3      .1       0
Bank Sta=340.3,360.3
XS Rating Curve= 0 ,0
Exp/Cntr=0.3,0.1

Type RM Length L Ch R = 1 ,8206.5  ,583.9,594.5,605.1
XS GIS Cut Line= 4
     1663065.147      204553.525     1662875.402       204665.14
     1662555.441      204929.294     1662311.749      205083.694
#Sta/Elev= 30
       0  926.08    13.4  917.47      84  890.36    95.7  882.76   166.3  859.68
   179.2  853.65     252   837.1   265.1  831.82     344   812.6   364.3  805.62
   386.1  803.39   396.1  803.15   406.1  804.32   449.1   810.7   580.6  814.51
     620  826.23   633.1  832.26   653.9  838.86   672.8  843.21   705.3  857.25
   717.3  867.63   753.3  889.79   786.4  917.41   789.3  920.17   801.3  940.28
   824.3  964.38   832.2  966.79   873.3 1008.61   885.3 1027.61   923.5 1059.04
#Mann= 3 , 0 , 0
       0     .08       0   386.1    .045       0   406.1     .08       0
Bank Sta=386.1,406.1
XS Rating Curve= 0 ,0
Exp/Cntr=0.3,0.1

Type RM Length L Ch R = 1 ,7612.1  ,559.7,540.5,521.4
XS GIS Cut Line= 4
     1662931.209      204062.422     1662668.915      204209.381
     1662352.674      204294.952     1662071.778      204555.386
#Sta/Elev= 30
       0  970.46     3.3  970.46    68.9  933.65    80.5  922.83    92.7  916.08
   150.2  889.88   161.8  880.42   231.5  845.35   243.1  835.25   278.8  820.18
   331.5  812.02   469.2  808.47   501.2  800.63   511.2  799.39   521.2  799.78
   553.2   805.7   563.7  813.37   626.7  839.17   636.9  846.66   662.6  857.04
   722.9  892.33   738.9  906.12   771.1  924.92     786  929.56   819.7  951.19
   833.5  965.36   889.5 1008.61   905.2 1017.52   920.1 1020.17  1011.3 1069.82
#Mann= 3 , 0 , 0
       0     .08       0   501.2    .045       0   521.2     .08       0
Bank Sta=501.2,521.2
XS Rating Curve= 0 ,0
Exp/Cntr=0.3,0.1

Type RM Length L Ch R = 1 ,7071.5  ,249.7,242.3,234.8
XS GIS Cut Line= 4
     1662430.805      203482.027     1662345.233      203679.212
     1662192.694      203928.485     1662021.551      204322.856
#Sta/Elev= 30
       0 1003.05     8.6 1003.05    30.7  983.82   108.1  926.92   118.2  926.02
   166.9  892.57   192.4  873.05   218.2  855.41   230.7  853.71   290.1  814.48
     302  804.43   313.9  795.76   315.8  795.68   325.8  795.26   335.8  795.48
   395.1  802.25   559.5  808.36   582.7  809.75   592.7   811.4   658.9  840.24
     670  840.77   695.7  851.69   712.5  859.29     738  872.94   769.4  887.66
   780.5  888.32   857.8  925.67   879.9  937.99   891.1  939.17   937.1   964.8
#Mann= 3 , 0 , 0
       0      .1       0   315.8    .045       0   335.8     .08       0
Bank Sta=315.8,335.8
XS Rating Curve= 0 ,0
Exp/Cntr=0.3,0.1

Type RM Length L Ch R = 1 ,6829.3  ,258.4,256.8,255.2
XS GIS Cut Line= 4
     1662146.109      203413.273     1662074.955      203635.107
     1662023.333      203836.013     1661892.186      204265.728
#Sta/Elev= 30
       0 1004.73     8.3 1001.05      38  980.42    48.6   979.9    88.9  949.56
   144.4  910.74     155  910.44   208.3  867.83   250.5  832.14     261  831.56
   275.7  819.69   292.3  802.12   303.3  793.18   313.3   791.9   323.3  793.93
   344.7  800.87   355.2  802.26   470.7  807.52   531.4  811.83   544.9  813.81
   563.9   820.2     572  819.69   620.8  837.81   661.3  854.35     672  854.74
   767.4  896.04     778  896.26   873.4  938.64     884  938.62   889.7  941.51
#Mann= 3 , 0 , 0
       0      .1       0   303.3    .045       0   323.3      .1       0
Bank Sta=303.3,323.3
XS Rating Curve= 0 ,0
Exp/Cntr=0.3,0.1

Type RM Length L Ch R = 1 ,6572.5  ,333.1,346,358.8
XS GIS Cut Line= 4
     1662127.585      203385.294     1661821.808      203566.311
        1661776.      203807.569     1661761.118      204270.769
#Sta/Elev= 30
       0 1000.26    19.3   996.2    31.1  988.03   101.8  969.39   113.6  961.45
   165.7  938.57     196  918.31   219.6  906.77     240  893.12   266.7  868.97
   278.5  851.42     285  846.49   303.1  842.24   337.3  829.65   391.1   804.2
   424.2  799.72     443  792.51     453  789.41     463  789.82   494.3     799
   627.9  804.67   688.8  814.99   719.2  827.28   729.3  827.31   790.2  856.04
   810.5   862.8   962.6  895.47  1033.6  930.11  1043.7  930.11  1064.3  941.18
#Mann= 3 , 0 , 0
       0      .1       0     443    .045       0     463      .1       0
Bank Sta=443,463
XS Rating Curve= 0 ,0
Exp/Cntr=0.3,0.1

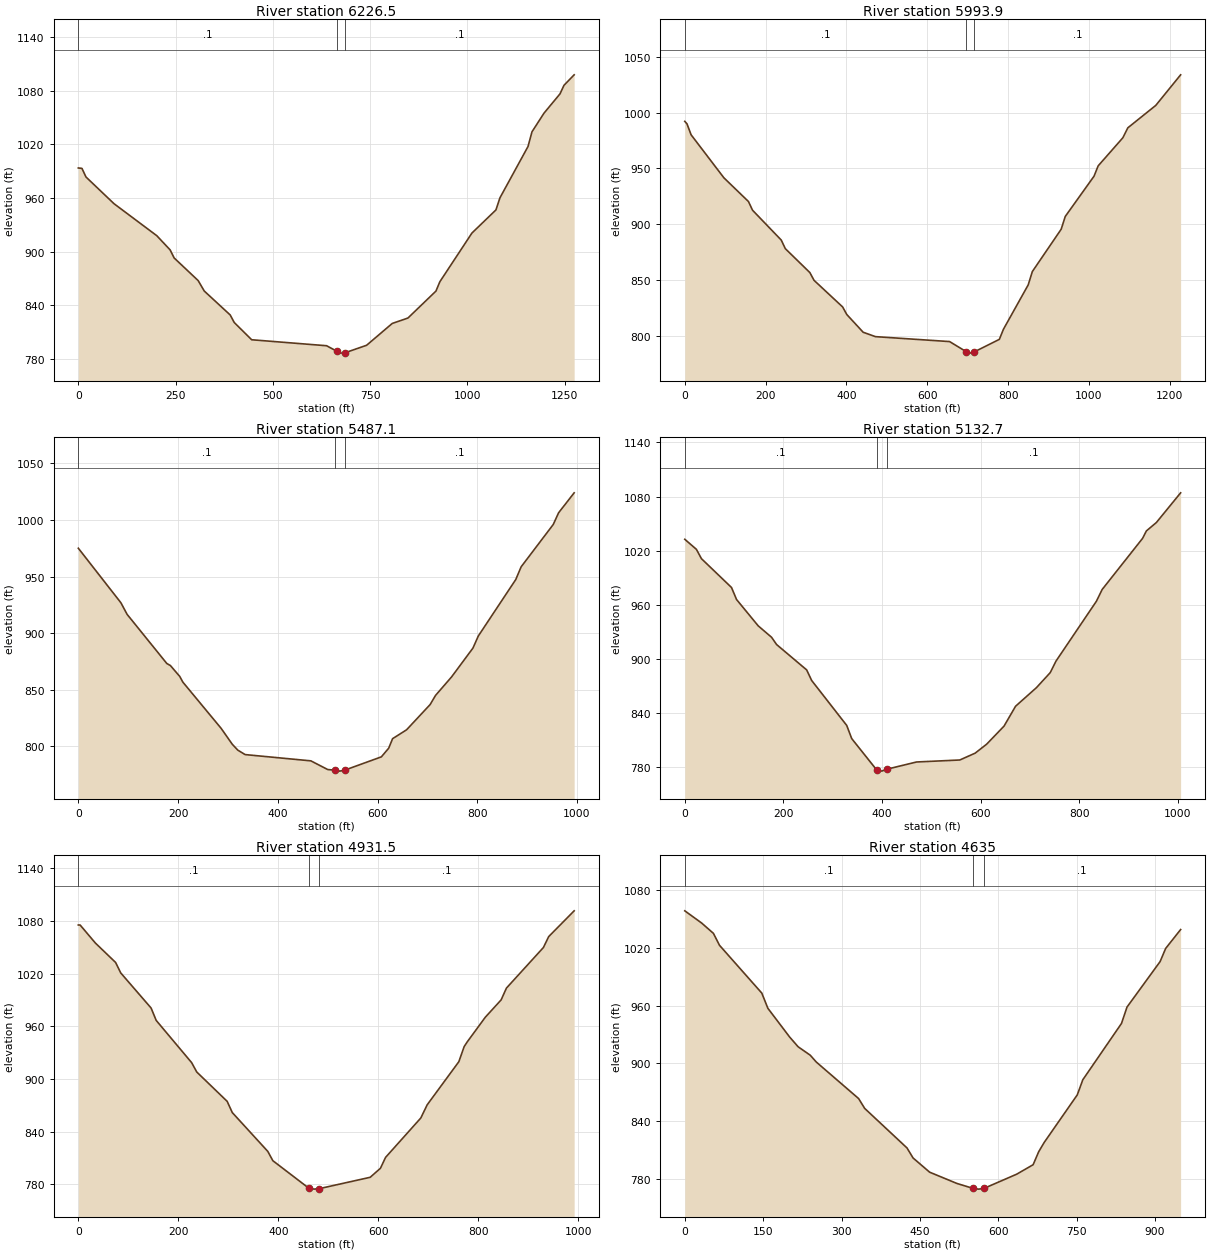
Type RM Length L Ch R = 1 ,6226.5  ,206.9,232.6,258.4
XS GIS Cut Line= 4
     1662120.144      203375.993     1661528.588      203483.887
     1661370.467      203673.631     1660950.053      203599.222
#Sta/Elev= 30
       0  993.65     9.3  993.22    19.6   983.6    91.8  953.67   201.7  917.92
     236  902.03   246.3  893.04   308.1   867.7   323.7  856.06   390.5  829.22
   400.9   820.8   445.7  801.51   638.3  794.83   665.2  788.55   675.2  786.56
   685.2  786.88   741.2  795.35   807.1  819.76   847.4  825.79   919.4  855.92
   929.6  866.47    1012  920.88  1073.7  946.73    1084  960.29  1156.1 1017.61
  1166.4 1034.12  1197.3 1054.99  1238.4 1076.54  1248.7 1086.16  1274.8 1097.84
#Mann= 3 , 0 , 0
       0      .1       0   665.2    .045       0   685.2      .1       0
Bank Sta=665.2,685.2
XS Rating Curve= 0 ,0
Exp/Cntr=0.3,0.1

Type RM Length L Ch R = 1 ,5993.9  ,484.7,506.7,528.7
XS GIS Cut Line= 4
     1662116.424      203362.971     1661552.771      203359.251
     1661309.079      203322.046     1660894.245      203282.981
#Sta/Elev= 30
       0  992.25     5.5  989.98    15.6  980.21    96.7  941.63   157.5  920.36
   167.6  912.56   238.6  885.79   248.7  878.09   309.5   856.6   319.7  849.71
   390.6  825.77   400.8  819.02   441.3  803.12   471.7  799.16   655.2  794.74
   696.3  785.69   706.3  784.38   716.3   785.5   778.3  796.74   788.5  805.85
   849.7  845.59   859.9  857.53   931.2  895.45   941.4  906.98  1012.6   943.1
  1022.8  952.34  1083.9  977.54  1096.2  986.46  1165.3 1006.55  1226.8 1033.98
#Mann= 3 , 0 , 0
       0      .1       0   696.3    .045       0   716.3      .1       0
Bank Sta=696.3,716.3
XS Rating Curve= 0 ,0
Exp/Cntr=0.3,0.1

Type RM Length L Ch R = 1 ,5487.1  ,379.5,354.4,329.4
XS GIS Cut Line= 4
     1662099.682      203338.788     1661828.086      203147.183
     1661673.686       202890.47     1661331.402      202771.414
#Sta/Elev= 30
       0  974.96    85.4   926.8    97.8   916.6   177.3  873.27   184.7  871.36
   203.4  861.77   209.5  856.82   286.5  815.87   308.7  801.91   319.8  796.71
   334.5  792.77   466.3  787.24   500.1  779.58   513.8  779.03   523.8  778.17
   533.8  778.97   607.7  790.77   622.4  798.42   630.2  806.82   658.3  814.67
   705.5  836.95   716.3     845   748.5  861.35   791.4  886.84   802.1  897.47
   877.2  947.32     888  958.56   952.4  995.94   963.1 1006.25   994.3 1023.88
#Mann= 3 , 0 , 0
       0      .1       0   513.8    .045       0   533.8      .1       0
Bank Sta=513.8,533.8
XS Rating Curve= 0 ,0
Exp/Cntr=0.3,0.1

Type RM Length L Ch R = 1 ,5132.7  ,205.8,201.2,196.5
XS GIS Cut Line= 4
     1662377.709      202756.143     1662090.302       202777.07
      1661841.96      202767.304     1661435.962      202532.914
#Sta/Elev= 30
       0 1032.77    23.6 1021.62    33.7 1011.35    94.7   979.4   104.9  966.12
   148.9  936.88     176  924.23   186.2  916.19   247.1  888.12   257.3  876.38
   328.4  826.58   338.5  812.02   389.4  777.13   399.4  775.98   409.4  778.07
     470  786.11   557.7  788.31   588.9  795.91   612.3  805.91   647.4  825.85
   670.8  847.87   713.1  868.43   741.1  885.09   752.8  897.89   834.7  964.14
   846.4  977.19   928.3 1033.76   936.1 1042.06   956.4 1051.39  1005.5 1084.25
#Mann= 3 , 0 , 0
       0      .1       0   389.4    .045       0   409.4      .1       0
Bank Sta=389.4,409.4
XS Rating Curve= 0 ,0
Exp/Cntr=0.3,0.1

Type RM Length L Ch R = 1 ,4931.5  ,287,296.5,306
XS GIS Cut Line= 4
     1662408.482      202550.046     1662023.412      202566.788
     1661753.677      202607.713     1661433.715      202512.841
#Sta/Elev= 30
       0 1075.44     3.6 1075.44      34 1054.97    74.6 1032.76    84.8 1020.88
   145.6  980.83   155.8  966.73   226.8  918.54   236.9  907.95   297.8  874.49
     308  861.72     379  817.51   389.2  806.85   461.2  775.52   471.2  774.46
   481.2  774.89   583.9  787.94   604.4   798.2   614.7  810.63   685.2  855.52
   697.9  870.49   761.3  919.69   771.9  936.85   778.2  942.34   814.2  970.33
   845.9  990.11   856.5 1003.53   930.5 1049.82   941.1 1062.27     992 1091.61
#Mann= 3 , 0 , 0
       0      .1       0   461.2    .045       0   481.2      .1       0
Bank Sta=461.2,481.2
XS Rating Curve= 0 ,0
Exp/Cntr=0.3,0.1

Type RM Length L Ch R = 1 ,4635    ,225.7,233.2,240.7
XS GIS Cut Line= 4
     1662381.894      202532.914     1661995.429      202319.451
     1661784.757      202269.225     1661505.721      202186.909
#Sta/Elev= 30
       0 1058.27    32.1 1045.67    54.8 1034.88    66.4 1022.53   147.4   972.9
     159  957.17   200.7  927.32   216.9  917.25   240.1  908.48   251.6  901.44
   332.7   863.5   344.3   853.3   425.3  812.27   436.9  801.87   468.6  787.14
   520.7  775.46   552.4  770.21   562.4  769.55   572.4  770.26   635.3  785.06
   666.7  794.88   677.3  808.29   687.8  817.91   751.2  867.33   761.8  883.01
   835.8  941.41   846.4  958.43   909.8 1005.66   920.3 1019.21     949 1038.82
#Mann= 3 , 0 , 0
       0      .1       0   552.4    .045       0   572.4      .1       0
Bank Sta=552.4,572.4
XS Rating Curve= 0 ,0
Exp/Cntr=0.3,0.1

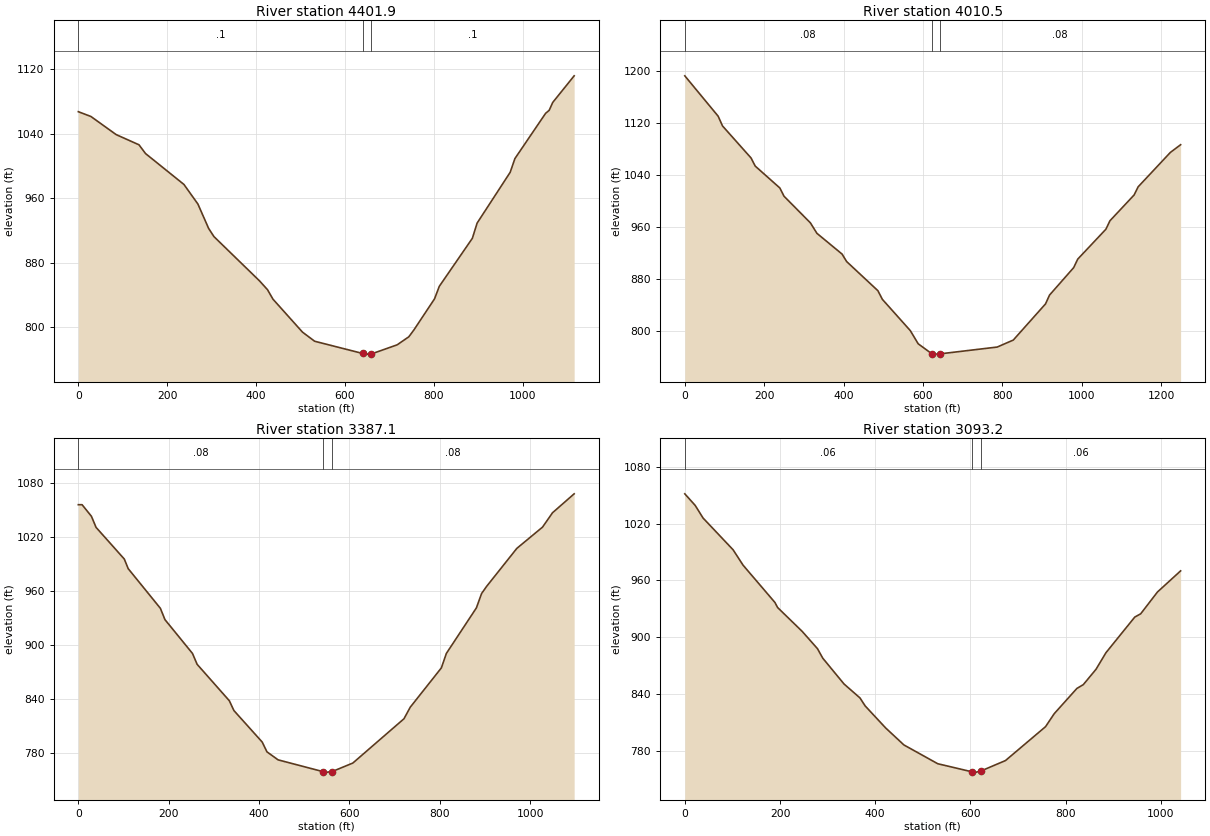
Type RM Length L Ch R = 1 ,4401.9  ,393.5,391.4,388.8
XS GIS Cut Line= 4
     1662397.458      202530.616     1662194.692      202214.376
     1661835.665      202002.308     1661527.795      201904.413
#Sta/Elev= 30
       0 1067.41    28.3 1061.48    85.2 1038.99   136.5 1026.38   151.2 1015.54
   237.7  977.19   269.1  952.95   293.2  922.73   305.2  912.56   407.7  857.71
   425.8  846.69   437.9  835.07   504.5  794.11   531.8  782.85   639.5  767.75
   649.5  766.89   659.5  767.13   717.4  778.41   743.7  788.39   755.4   797.1
   801.6   835.5   812.2  850.89   886.7  910.52   897.3  929.28   971.7  992.24
   982.4 1009.31  1051.4 1065.35  1059.5 1069.12  1067.5 1078.89  1115.7 1111.88
#Mann= 3 , 0 , 0
       0      .1       0   639.5    .045       0   659.5      .1       0
Bank Sta=639.5,659.5
XS Rating Curve= 0 ,0
Exp/Cntr=0.3,0.1

Type RM Length L Ch R = 1 ,4010.5  ,641.9,623.4,605.4
XS GIS Cut Line= 4
     1662811.362      201817.912     1662440.244      201897.437
     1662104.005      201734.201     1661608.716      201713.273
#Sta/Elev= 30
       0 1193.01      84 1130.79    95.1 1115.69   166.9 1066.35   177.3  1053.9
   239.5 1020.04   249.9 1007.41   316.5  966.22   332.8  950.19   396.3   918.1
   407.6  906.67   486.4  861.72   497.7  848.36   568.1  800.13   587.9  779.84
     622   764.6     632   763.9     642  764.25   786.9   774.8   827.5  785.59
   908.7  841.36   918.8  854.96   979.7  897.34   989.8  910.35  1060.8  956.51
    1071  969.54  1131.9 1009.35    1142 1021.86  1223.2 1074.92    1249 1086.78
#Mann= 3 , 0 , 0
       0     .08       0     622    .045       0     642     .08       0
Bank Sta=622,642
XS Rating Curve= 0 ,0
Exp/Cntr=0.3,0.1

Type RM Length L Ch R = 1 ,3387.1  ,288.7,293.9,299.1
XS GIS Cut Line= 4
     1662535.116      201148.225     1662173.764      201180.314
     1661858.453      201272.396      1661488.73      201441.213
#Sta/Elev= 30
       0  1055.9     8.3  1055.9      29 1043.04    39.2 1030.79   101.8  995.61
   110.4  984.98   181.6  941.04   191.8  928.43   252.8  890.89     263  878.89
   334.3  838.49   344.4  827.63   407.1  792.64   417.6  781.81   442.2  772.94
   541.3  759.92   551.3  759.32   561.3  759.82   607.7  769.38   720.9  818.48
   734.9  831.37   803.7   874.9   814.8  890.96   881.3  941.49   892.8  957.44
   903.9  965.31   970.8 1007.46  1027.7 1031.05  1049.8 1046.96  1097.7 1067.96
#Mann= 3 , 0 , 0
       0     .08       0   541.3    .045       0   561.3     .08       0
Bank Sta=541.3,561.3
XS Rating Curve= 0 ,0
Exp/Cntr=0.3,0.1

Type RM Length L Ch R = 1 ,3093.2  ,262.9,251.6,240.3
XS GIS Cut Line= 4
     1662515.987      201088.514     1662173.702      200930.394
     1661836.999      200954.577     1661623.071      201201.989
#Sta/Elev= 30
       0 1051.64    21.9 1039.34    38.4 1026.02   101.5  992.43   122.4  976.18
   189.4   936.7     195  931.37   246.8  906.03   278.7  887.86   289.9  877.75
   334.5  850.49     368  835.75     379  827.24   421.8  804.07   460.3  786.01
   531.4  766.14   602.7  757.66   612.7  757.26   622.7  758.59   673.7   769.5
   757.9  805.36   776.1  819.09   823.7   845.8   837.1  849.78   863.9  866.06
   884.6  883.49   945.3  921.27   957.7  924.73     993  947.82  1041.6  970.15
#Mann= 3 , 0 , 0
       0     .06       0   602.7    .045       0   622.7     .06       0
Bank Sta=602.7,622.7
XS Rating Curve= 0 ,0
Exp/Cntr=0.3,0.1