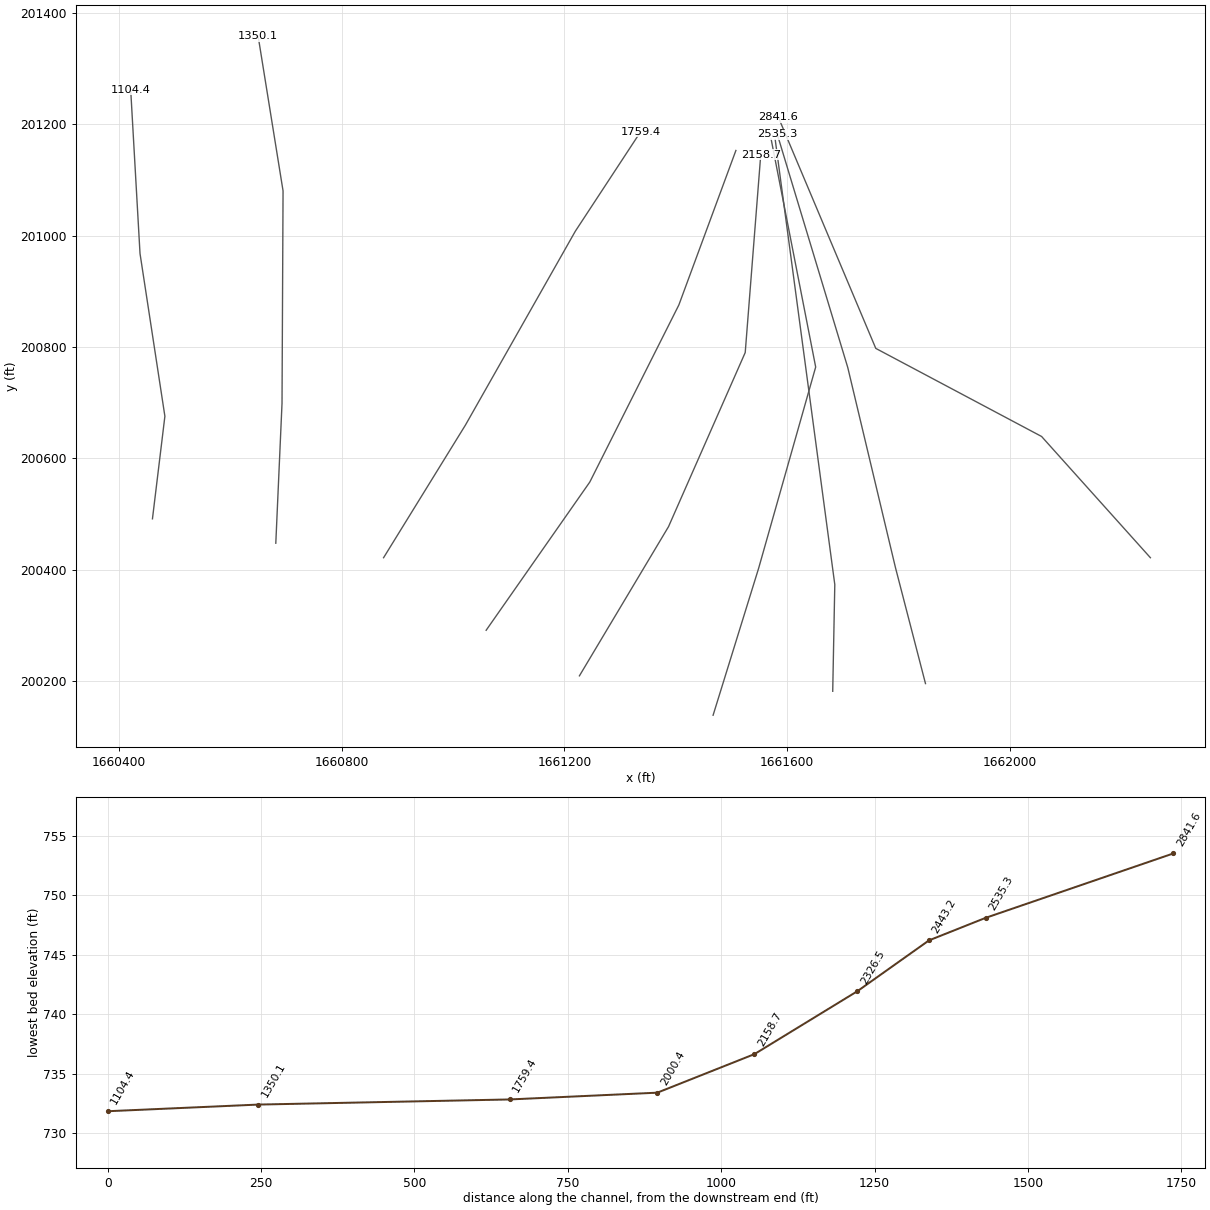
HEC-RAS study bchcrk.prj: bchcrk

--- bchcrk.g01 (geometry) --- (continued)

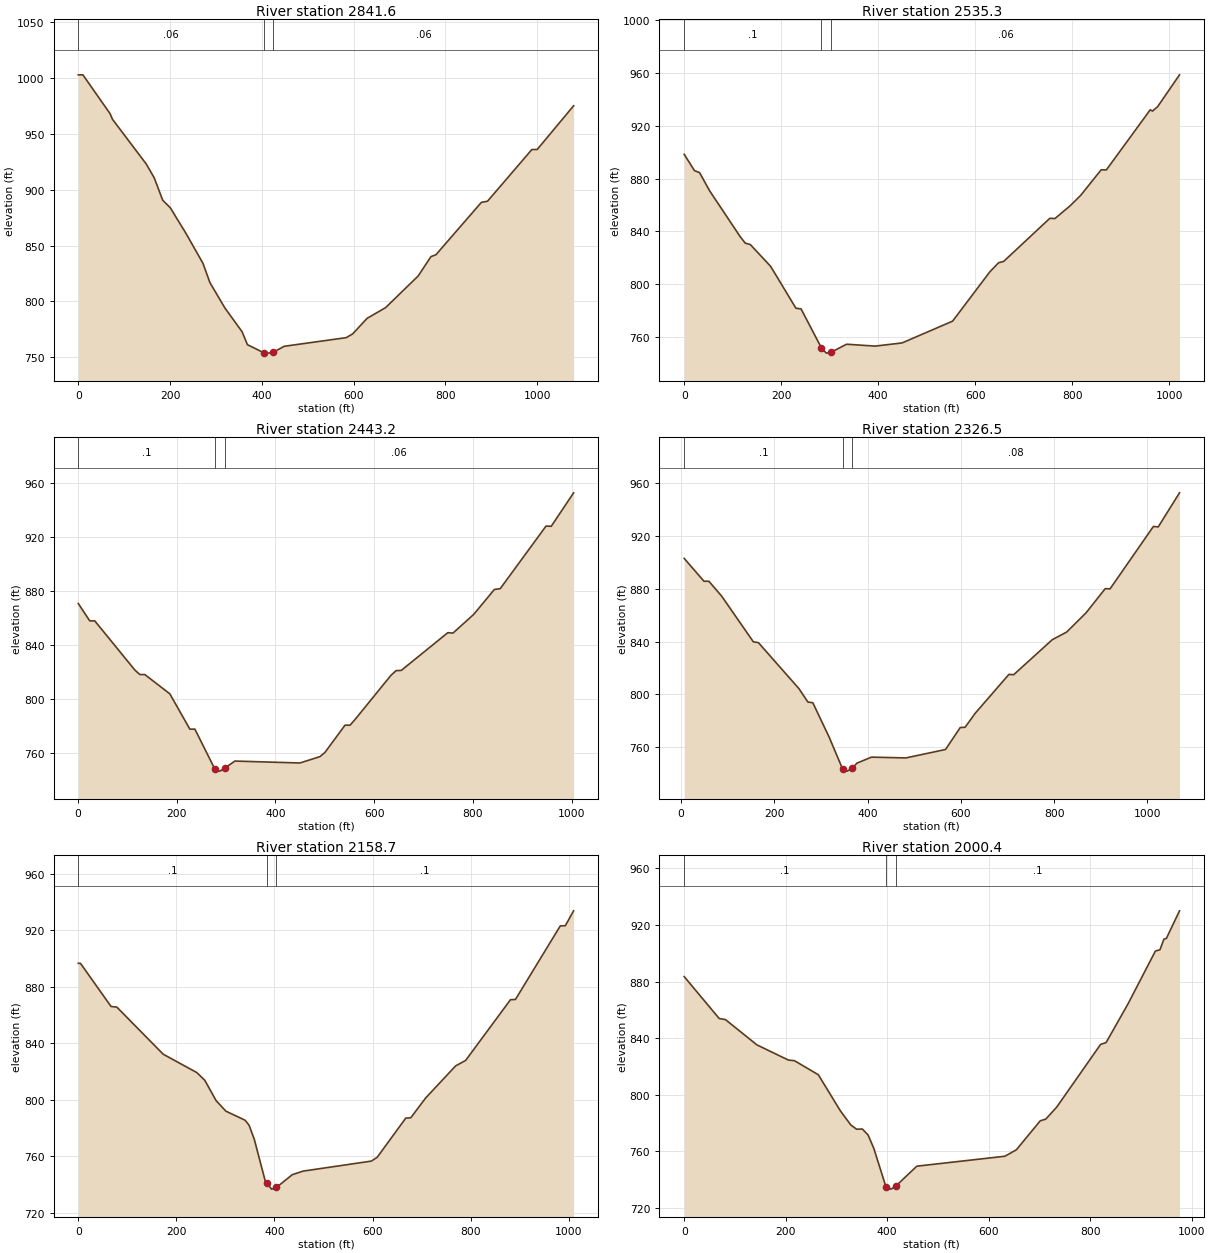
Type RM Length L Ch R = 1 ,2841.6  ,326.6,306.3,285.9
XS GIS Cut Line= 4
     1662251.894      200421.568     1662056.569      200639.216
      1661758.93      200797.337     1661584.068      201212.171
#Sta/Elev= 30
       0 1003.04      10 1003.04    69.2  968.25    74.4  963.22   148.1  923.11
   165.5   910.7     184  890.64   200.6  883.81   234.3  861.16   271.7  834.07
   286.9  816.78   319.6  793.98   357.1  772.66   368.6  761.12   404.5  753.83
   414.5  753.52   424.5  754.19   448.9  759.65     584  767.39   598.1  770.76
   629.5   784.7   669.7  794.27   740.9   822.7   768.7  840.03   779.7  841.78
   878.7  888.72     892  889.71   988.7  936.06  1000.3  936.09  1079.7  975.28
#Mann= 3 , 0 , 0
       0     .06       0   404.5    .045       0   424.5     .06       0
Bank Sta=404.5,424.5
XS Rating Curve= 0 ,0
Exp/Cntr=0.3,0.1

Type RM Length L Ch R = 1 ,2535.3  ,97.9,92.1,86.2
XS GIS Cut Line= 4
      1661848.16      200195.598     1661794.213      200403.945
     1661708.642      200762.972     1661582.146      201181.526
#Sta/Elev= 30
       0  898.31    21.2  885.96    31.7  884.47    52.6  870.64   115.5  836.08
   125.9  831.19   136.4  830.11   178.3  813.65   230.5     782     241  781.54
   283.1     752   293.1   748.1   303.1  748.79   334.9  754.82   393.8  753.41
   449.4   755.8   553.6  772.26   630.1  809.37   648.4   816.4   658.9  817.38
   754.2  849.96   764.8  849.79   796.6   859.6   817.8   867.3   860.1  886.63
   870.7   886.5   961.2  931.91     966  930.97   976.6  934.35  1021.6  958.34
#Mann= 3 , 0 , 0
       0      .1       0   283.1    .045       0   303.1     .06       0
Bank Sta=283.1,303.1
XS Rating Curve= 0 ,0
Exp/Cntr=0.3,0.1

Type RM Length L Ch R = 1 ,2443.2  ,123.6,116.7,109.8
XS GIS Cut Line= 3
     1661681.617      200181.819     1661685.338      200373.424
     1661578.374      201172.223
#Sta/Elev= 30
       1  870.53    24.2  857.66    34.3  857.67   115.4  821.25   125.6  817.86
   135.7  817.86   186.4  803.54   226.9  777.35   237.1  777.35   277.8  747.51
   287.8  746.21   297.8  748.47   318.1  753.68   449.9  752.25   490.4  756.97
   500.6  760.12   541.1  780.28   551.3  780.28   561.3  784.43   634.1  817.24
   644.6  820.74   655.1  820.92   749.3  848.89   759.8  848.61   801.7  862.43
   843.6  880.96   855.5  881.56   948.3  928.01   958.8  927.82  1004.1  952.64
#Mann= 3 , 0 , 0
       1      .1       0   277.8    .045       0   297.8     .06       0
#XS Ineff= 2 , 0
       0                     338       0
Permanent Ineff=
       F       F
Bank Sta=277.8,297.8
XS Rating Curve= 0 ,0
Exp/Cntr=0.3,0.1

Type RM Length L Ch R = 1 ,2326.5  ,171.3,167.8,164.4
XS GIS Cut Line= 4
     1661466.872      200138.812     1661548.723      200402.966
     1661651.036      200763.853     1661571.046      201173.106
#Sta/Elev= 30
     6.7  902.87    49.1  885.59    59.7  885.56    87.2  874.25     155  839.75
   165.8  839.14   252.6   804.4     272  794.19   282.5  793.68   317.9  767.34
   346.3  743.56   356.3  741.94   366.3  744.08   377.3  748.01   408.2  752.52
   482.1  751.93     567  758.31   598.6  774.92   609.1  775.14   630.2   785.5
   702.9  815.11   713.2  814.88   795.8  841.34   826.8  847.17   868.1  861.59
   909.4  879.97   919.8  879.82  1012.7  927.02  1023.1  926.68  1068.7  952.47
#Mann= 3 , 0 , 0
     6.7      .1       0   346.3    .045       0   366.3     .08       0
#XS Ineff= 2 , 0
       0                     408       0
Permanent Ineff=
       F       F
Bank Sta=346.3,366.3
XS Rating Curve= 0 ,0
Exp/Cntr=0.3,0.1

Type RM Length L Ch R = 1 ,2158.7  ,159.6,158.3,157
XS GIS Cut Line= 4
     1661226.901      200209.501     1661386.882      200477.375
      1661524.54      200789.896     1661552.444      201145.202
#Sta/Elev= 30
       0   896.7     4.4   896.7    66.8  866.08    78.6  865.65     173   832.3
   241.6  819.27   257.8  813.84   281.1  799.31   300.9  791.92   340.2  785.46
   348.2  781.93   358.8  772.02     381  742.59     384  741.23     394  736.65
     404  737.87   436.3  746.89   458.5  749.42   597.4  756.51   609.3  759.16
   667.7  786.99   677.8   787.2   708.3  801.27   769.3  823.98   789.7  827.85
   881.2  870.91   891.3  871.07   982.8  923.24     993  923.33  1009.9  933.89
#Mann= 3 , 0 , 0
       0      .1       0     384    .045       0     404      .1       0
Bank Sta=384,404
XS Rating Curve= 0 ,0
Exp/Cntr=0.3,0.1

Type RM Length L Ch R = 1 ,2000.4  ,242.2,240.9,239.7
XS GIS Cut Line= 4
      1661059.48      200291.351     1661245.504      200557.366
     1661405.484      200875.467     1661507.798      201152.643
#Sta/Elev= 30
       0  883.58      69  853.96    81.4  853.19   143.2  835.36   205.1  824.64
   217.4  824.14   264.3  814.25     308  788.61   328.4  778.74   339.7  775.76
   351.1  775.88   362.4  771.67   373.8  762.08   397.8  734.79   407.8  733.41
   417.8  735.82   458.4  749.62     632  756.65   654.6   761.2   701.7   781.7
   712.5  782.86   734.2   791.4   820.6  835.68   831.4  836.95   874.6   864.3
   928.6  901.64   937.6  902.55   945.4  910.08   950.2  910.55   976.1  930.06
#Mann= 3 , 0 , 0
       0      .1       0   397.8    .045       0   417.8      .1       0
Bank Sta=397.8,417.8
XS Rating Curve= 0 ,0
Exp/Cntr=0.3,0.1

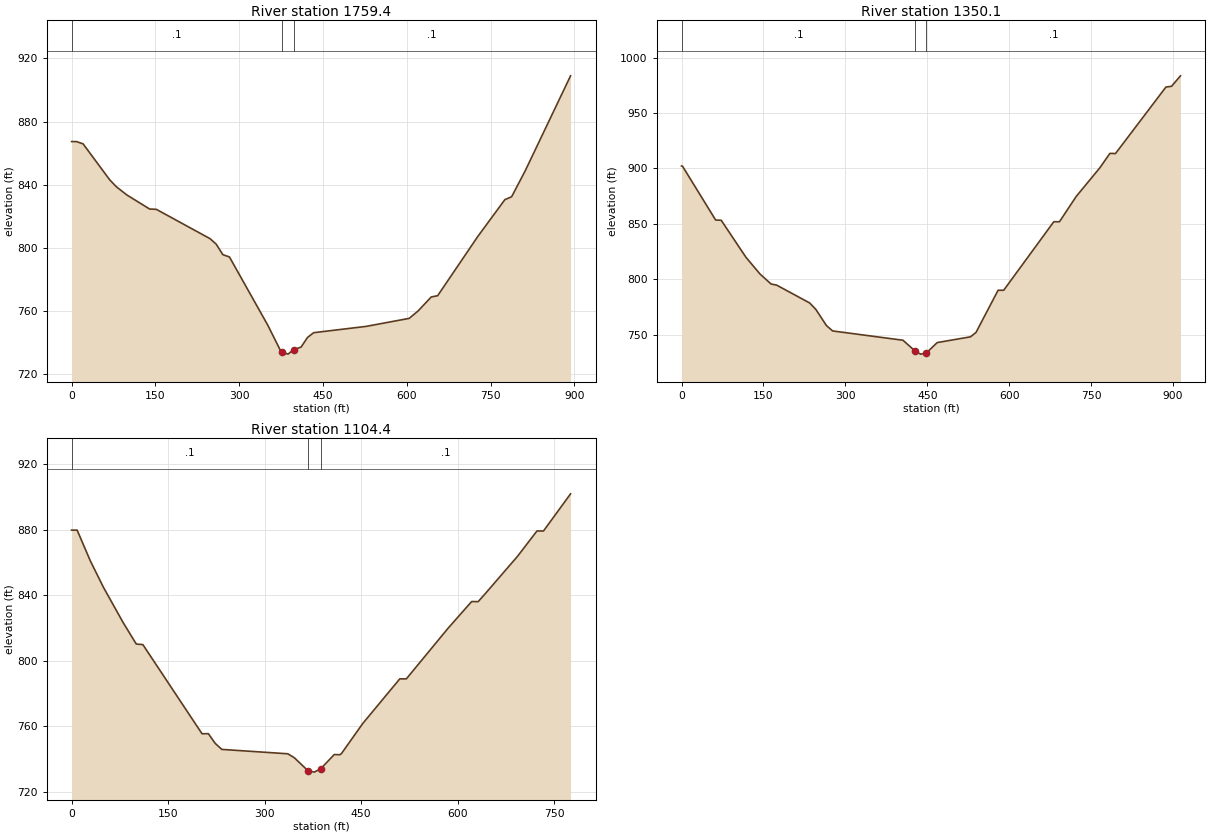
Type RM Length L Ch R = 1 ,1759.4  ,396.5,409.3,422.1
XS GIS Cut Line= 4
     1660875.316      200421.568     1661022.275      200659.679
      1661219.46      201007.544     1661336.656      201186.127
#Sta/Elev= 30
       0   867.3     8.7   867.3    20.6  865.85    68.3  843.07    80.2  838.69
    98.9  833.54   139.7  824.63   151.7  824.44   247.8  805.89   258.8  802.45
   270.8  795.76   282.6   794.3   351.6  750.91   373.9  735.12   377.5  734.11
   387.5  732.84   397.5   735.7   410.8  737.28   422.4  743.42   433.4   746.4
   527.3  750.39   604.4  755.46   620.5   760.2   643.8  768.98   655.4  769.82
   727.2  807.27   775.7  830.57   787.8  832.41   812.1   848.8   893.3   908.9
#Mann= 3 , 0 , 0
       0      .1       0   377.5    .045       0   397.5      .1       0
Bank Sta=377.5,397.5
XS Rating Curve= 0 ,0
Exp/Cntr=0.3,0.1

Type RM Length L Ch R = 1 ,1350.1  ,241.8,245.7,249.6
XS GIS Cut Line= 4
     1660681.851      200447.612     1660693.012      200698.744
     1660694.872      201080.093     1660650.227      201357.269
#Sta/Elev= 30
       0  902.16     1.8  902.01    62.5  853.41    72.7   853.2   118.1  819.71
   143.7  804.71     164  795.67   174.1   794.7   234.7  778.56     246  772.72
   265.4  758.15   276.7  753.33   405.5  744.94   427.7  735.14   437.7  732.41
   447.7  733.16   468.1  742.83     529  748.01   539.1  751.94   579.6  790.04
   589.8  790.02   681.6  851.89   691.9  851.84   722.7  874.73   765.8  900.47
   784.3  913.56   794.5  913.37   886.9  973.41   897.2   974.1   913.5  983.53
#Mann= 3 , 0 , 0
       0      .1       0   427.7    .045       0   447.7      .1       0
Bank Sta=427.7,447.7
XS Rating Curve= 0 ,0
Exp/Cntr=0.3,0.1

Type RM Length L Ch R = 1 ,1104.4  ,1110.1,1104.4,1098.7
XS GIS Cut Line= 4
     1660460.421      200491.377     1660482.743      200675.541
     1660438.098      200967.599     1660421.355      201261.517
#Sta/Elev= 30
       0  879.77     8.6  879.77      29  861.05    49.5  844.79    80.1  823.26
   100.5  810.14   110.7  809.81   202.7   755.3   212.5  755.36   223.2  749.42
   233.4  745.74     336  743.06   346.2  740.62     367  732.83     377  731.85
     387  733.85   408.2   742.6     417  742.49   419.3  743.17   452.6  761.65
     510  788.86   520.2  788.86   584.8  819.69   621.7  836.12   631.8  836.06
     642  840.55   692.7  863.63   723.2  879.26   733.3  879.23   775.4  901.96
#Mann= 3 , 0 , 0
       0      .1       0     367    .045       0     387      .1       0
Bank Sta=367,387
XS Rating Curve= 0 ,0
Exp/Cntr=0.3,0.1

Chan Stop Cuts=-1
Use User Specified Reach Order=0